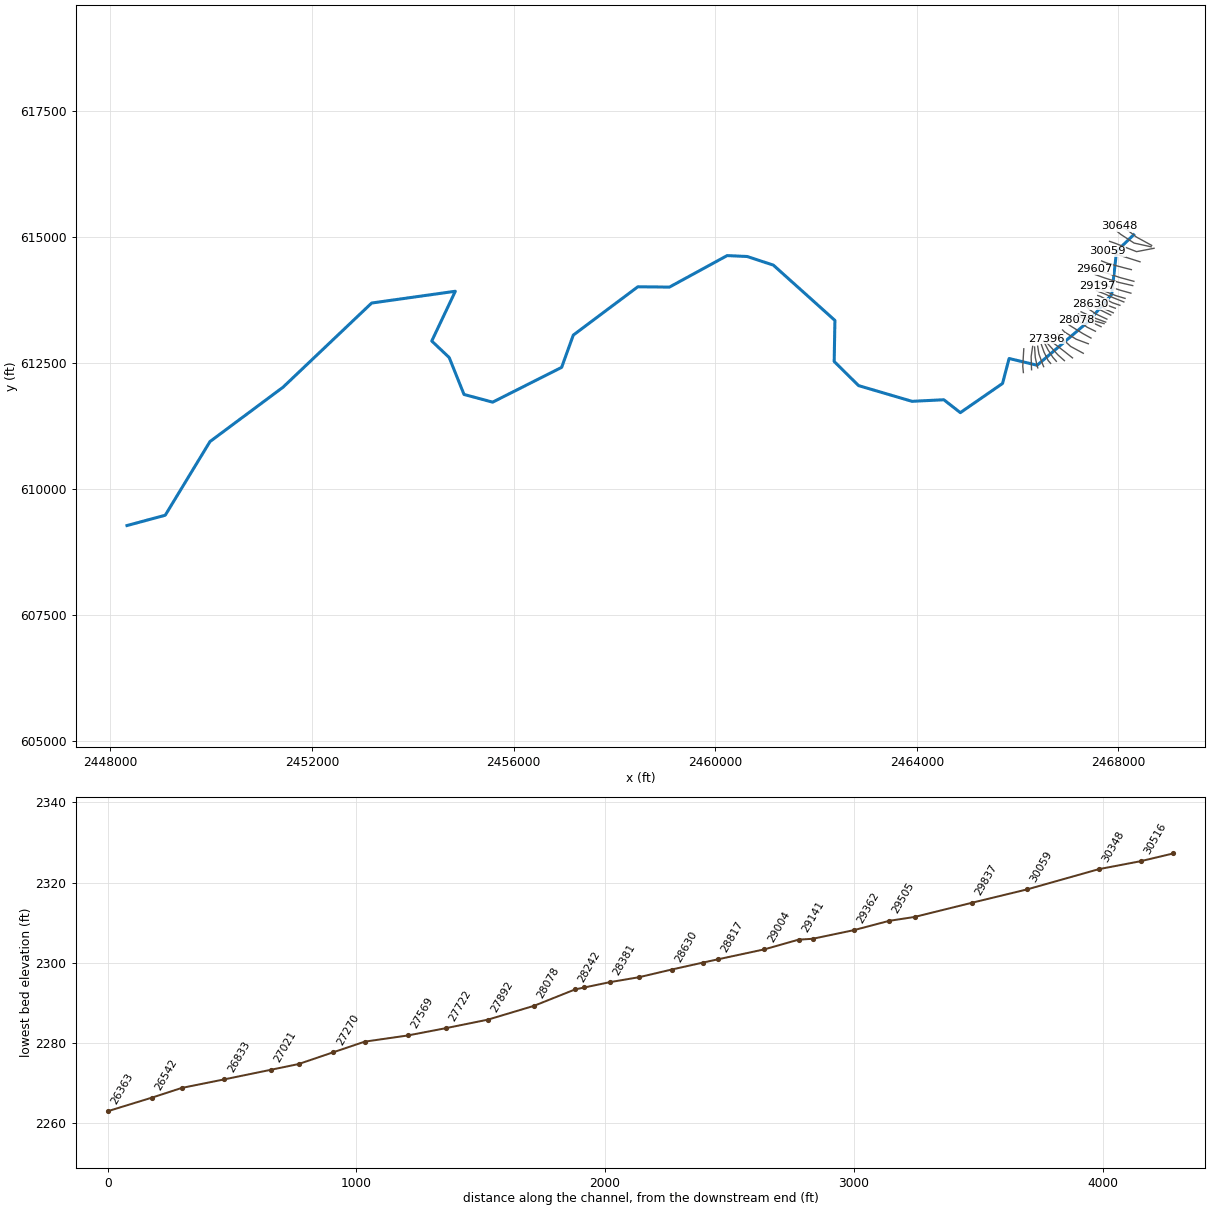
--- TROUTRN.prj (project) ---

Proj Title=TROUTRN
Current Plan=p01
Default Exp/Contr=0,0
English Units
Geom File=g01
Flow File=f01
Plan File=p01
Background Map Layer=QC
BEGIN DESCRIPTION:
Stream Name:Trout Run
Flood Zone: Zone A
Pendleton County, WV
WVDHSEM Flood Warning & Analysis Mapping
HEC-RAS Version: 5.0.7
Hydrology Method:
Regression
Model Notes:
Tie in with SBPOTOMC1 at the downstream end.
END DESCRIPTION:
DSS Export Rating Curves= 0
DSS Export Rating Curve Sorted= 0
DSS Export Volume Flow Curves= 0
DXF OffsetX= 0
DXF OffsetY= 0
DXF ScaleX= 0
DXF ScaleY= 0

--- TROUTRN.p01 (plan) ---

Plan Title=Floodplain
Program Version=5.07
Short Identifier=Floodplain
Geom File=g01
Flow File=f01
Subcritical Flow
K Sum by GR= 0
Std Step Tol= 0.01
Critical Tol= 0.01
Num of Std Step Trials= 20
Max Error Tol= 0.3
Flow Tol Ratio= 0.001
Split Flow NTrial= 30
Split Flow Tol= 0.02
Split Flow Ratio= 0.02
Log Output Level= 0
Friction Slope Method= 1
Unsteady Friction Slope Method= 2
Unsteady Bridges Friction Slope Method= 1
Parabolic Critical Depth
Global Vel Dist= 0 , 0 , 0
Global Log Level= 0
CheckData=True
Encroach Param=-1 ,0,0, 0
Mapping Interval=1HOUR
Computation Time Step Use Courant=        0
Computation Time Step Use Time Series=    0
Computation Time Step Count To Double=0
Computation Time Step Max Doubling=0
Computation Time Step Max Halving=0
Computation Time Step Residence Courant=0
Run HTab= 0
Run UNet= 0
Run Sediment= 0
Run PostProcess= 0
Run WQNet= 0
Run RASMapper= 0
UNET Theta= 0
UNET Theta Warmup= 0
UNET ZTol= 0
UNET ZSATol= 0
UNET MxIter= 0
UNET Max Iter WO Improvement= 0
UNET MaxInSteps= 0
UNET DtIC= 0
UNET DtMin= 0
UNET MaxCRTS= 0
UNET WFStab= 0
UNET SFStab= 0
UNET WFX= 1
UNET SFX= 1
UNET 1D Methodology=Finite Difference
UNET DSS MLevel= 1
UNET Pardiso=0
UNET DZMax Abort= 0
UNET Use Existing IB Tables= 0
UNET Froude Reduction=False
UNET Froude Limit= 0
UNET Froude Power= 0
UNET D1 Cores= 0
UNET D2 Coriolis=0
UNET D2 Cores= 0
UNET D2 Theta= 1
UNET D2 Theta Warmup= 1
UNET D2 Z Tol= 0.01
UNET D2 Volume Tol= 0.01
UNET D2 Max Iterations= 20
UNET D2 Equation= 0
UNET D2 RampUpFraction=0.1
UNET D2 TimeSlices= 1
UNET D2 BCVolumeCheck=0
UNET D1D2 MaxIter= 0
UNET D1D2 ZTol=0.01
UNET D1D2 QTol=0.1
UNET D1D2 MinQTol=1
Write IC File= 0
Write IC File at Fixed DateTime=0
Write IC File at Sim End=0
Echo Input=False
Echo Parameters=False
Echo Output=False
Write Detailed= 0
HDF Write Warmup=0
HDF Write Time Slices=0
HDF Flush=0
HDF Face Node Velocities=0
HDF Compression= 1
HDF Chunk Size= 1
HDF Spatial Parts= 1
HDF Use Max Rows=0
HDF Fixed Rows= 1
Calibration Method= 0
Calibration Iterations= 20
Calibration Max Change=0.05
Calibration Tolerance=0.2
Calibration Maximum=1.5
Calibration Minimum=0.5
Calibration Optimization Method= 1
WQ AD Non Conservative
WQ ULTIMATE=-1
WQ Max Comp Step=1HOUR
WQ Output Interval=15MIN
WQ Output Selected Increments= 0
WQ Output face flow=0
WQ Output face velocity=0
WQ Output face area=0
WQ Output face dispersion=0
WQ Output cell volume=0
WQ Output cell surface area=0
WQ Output cell continuity=0
WQ Output cumulative cell continuity=0
WQ Output face conc=0
WQ Output face dconc_dx=0
WQ Output face courant=0
WQ Output face peclet=0
WQ Output face adv mass=0
WQ Output face disp mass=0
WQ Output cell mass=0
WQ Output cell source sink temp=0
WQ Output nsm pathways=0
WQ Output nsm derived pathways=0
WQ Output MaxMinRange=-1
WQ Daily Max Min Mean=-1
WQ Daily Range=0
WQ Daily Time=0
WQ Create Restart=0
WQ Fixed Restart=0
WQ System Summary=0
WQ Write To DSS=0
WQ Use Fixed Temperature=0
Sorting and Armoring Iterations= 10
XS Update Threshold= 0.02
Bed Roughness Predictor= 0
Hydraulics Update Threshold= 0.02
Energy Slope Method= 1
Volume Change Method= 1
Sediment Retention Method= 0
XS Weighting Method= 0
Number of US Weighted Cross Sections= 1
Number of DS Weighted Cross Sections= 1
Upstream XS Weight=0
Main XS Weight=1
Downstream XS Weight=0
Number of DS XS's Weighted with US Boundary= 1
Upstream Boundary Weight= 1
Weight of XSs Associated with US Boundary= 0
Number of US XS's Weighted with DS Boundary= 1
Downstream Boundary Weight= 0.5
Weight of XSs Associated with DS Boundary= 0.5
Percentile Method= 0
Sediment Output Level= 3
Mass or Volume Output= 0
Output Increment Type= 1
Profile and TS Output Increment= 1
XS Output Flag= 0
XS Output Increment= 10
Write Gradation File= 0
Read Gradation Hotstart= 0
Write HDF5 File= 1
Write Binary Output= 1
Write DSS Sediment File= 0
SV Curve= 0
Specific Gage Flag= 0

--- TROUTRN.f01 (steady flow) ---

Flow Title=Flows
Program Version=5.07
Number of Profiles= 6
Profile Names=P100yr,P10yr,P25yr,P50yr,P500yr,P101yr
River Rch & RM=TROUTRN,Main            ,30648
     526     246     348     434     770     640
River Rch & RM=TROUTRN,Main            ,30348
     585     273     386     483     857     711
River Rch & RM=TROUTRN,Main            ,28817
     679     317     448     560     997     826
River Rch & RM=TROUTRN,Main            ,24960
     861     400     567     709    1267    1047
River Rch & RM=TROUTRN,Main            ,21676
    1570     724    1030    1292    2326    1911
River Rch & RM=TROUTRN,Main            ,19018
    1888     867    1236    1552    2802    2298
River Rch & RM=TROUTRN,Main            ,13232
    2322    1064    1518    1908    3454    2826
River Rch & RM=TROUTRN,Main            ,7371
    3544    1613    2309    2907    5295    4314
Boundary for River Rch & Prof#=TROUTRN,Main            , 1
Up Type= 0
Dn Type= 3
Dn Slope=0.015673
Boundary for River Rch & Prof#=TROUTRN,Main            , 2
Up Type= 0
Dn Type= 3
Dn Slope=0.015673
Boundary for River Rch & Prof#=TROUTRN,Main            , 3
Up Type= 0
Dn Type= 3
Dn Slope=0.015673
Boundary for River Rch & Prof#=TROUTRN,Main            , 4
Up Type= 0
Dn Type= 3
Dn Slope=0.015673
Boundary for River Rch & Prof#=TROUTRN,Main            , 5
Up Type= 0
Dn Type= 3
Dn Slope=0.015673
Boundary for River Rch & Prof#=TROUTRN,Main            , 6
Up Type= 0
Dn Type= 3
Dn Slope=0.015673
DSS Import GetInterval= 0
DSS Import GetPeak= 0
DSS Import FillOption= 0

--- TROUTRN.g01 (geometry) ---

Geom Title=Geometry
Program Version=5.07

River Reach=TROUTRN         ,Main
Reach XY= 30
     2468302.102      615043.544      2467963.12      614717.549
     2467866.269      613861.792     2467408.245      613327.998
     2466387.694       612456.97     2465830.629      612590.878
     2465700.244      612095.606     2464863.108      611516.997
     2464535.933      611772.497     2463903.902      611741.666
     2462844.522       612052.84     2462360.468       612531.83
     2462374.675      613346.162     2461153.615      614442.532
     2460633.997      614613.485     2460235.789       614631.48
     2459092.546      614006.842     2458464.466      614012.979
     2457183.509       613054.59     2456952.861      612415.014
     2455583.608      611725.149     2455016.043      611877.463
     2454721.238      612610.568     2454375.688      612937.468
     2454843.299      613924.185     2453183.462      613690.838
     2451424.325      612020.873     2449974.626      610942.892
     2449087.574      609482.396     2448329.227      609278.186

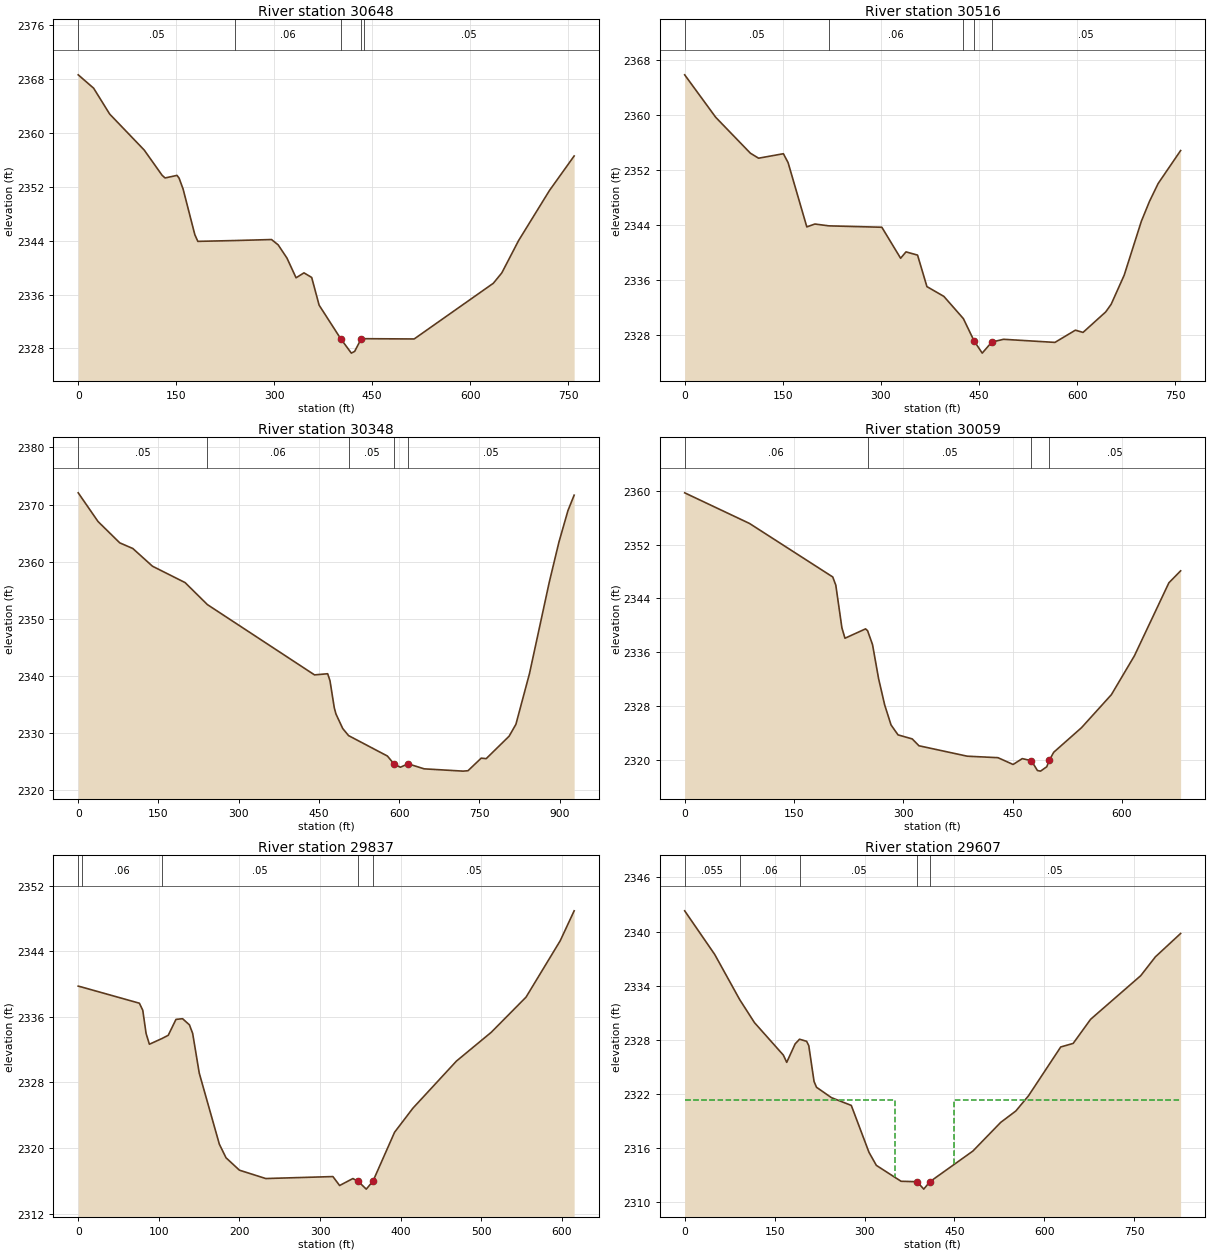
Type RM Length L Ch R = 1 ,30648   ,130.6,131.9,133
XS GIS Cut Line= 4
2468659.48632643614834.1804669792468356.05379965614999.689117951
2468150.55384504615158.8938202542468007.57671426615214.998770304
#Sta/Elev= 30
       0 2368.57    23.6 2366.59    48.2 2362.75   101.1 2357.41   128.4 2353.68
     133 2353.28   151.2 2353.66   154.4 2353.26   160.5 2351.66   178.5 2344.88
   183.1 2343.88  239.29    2344   295.9 2344.15   306.1 2343.36   319.5 2341.41
   333.5 2338.48   345.6 2339.21   357.4 2338.53   368.8 2334.42  401.862329.441
   418.1 2327.31   423.2 2327.57   433.3 2329.45  437.59 2329.45   514.3 2329.41
   635.5 2337.67   648.4  2339.2   674.1 2343.99   721.4 2351.42759.1819 2356.54
#Mann= 5 ,-1 , 0
       0     .05       0  239.29     .06       0  401.86    .045       0
   433.3     .06       0  437.59     .05       0
Bank Sta=401.86,433.3
XS Rating Curve= 0 ,0
Exp/Cntr(USF)=0,0
Exp/Cntr=0.3,0.1

Type RM Length L Ch R = 1 ,30516   ,165.8,168.3,171
XS GIS Cut Line= 4
2468649.16087082614805.5901088682468310.72133342614879.793429901
2468046.48511706615051.7279542472467972.28179602615113.262415591
#Sta/Elev= 30
       0 2365.83    47.5 2359.65   100.5 2354.43     113 2353.71   150.9 2354.36
   158.1 2353.06   186.7 2343.72     199 2344.14  220.422343.872   301.4 2343.67
   330.1 2339.16   338.3 2340.09     356 2339.62   370.3 2335.04   396.2 2333.62
  426.042330.384   442.22327.186   454.8 2325.37   469.5 2326.98   487.5 2327.38
     566 2326.93   597.3 2328.71   608.9 2328.38   643.6 2331.36   651.9 2332.47
   671.8 2336.69     698 2344.52   710.5 2347.43   723.7 2350.02   758.1 2354.82
#Mann= 5 ,-1 , 0
       0     .05       0  220.42     .06       0  426.04     .05       0
   442.2    .045       0   469.5     .05       0
Bank Sta=442.2,469.5
XS Rating Curve= 0 ,0
Exp/Cntr(USF)=0,0
Exp/Cntr=0.3,0.1

Type RM Length L Ch R = 1 ,30348   ,283.7,288.8,283.8
XS GIS Cut Line= 4
2468707.07565796614776.6327152942468359.58693508614709.668742654
2467948.75391375614870.7442444092467823.87515396 614914.18033477
#Sta/Elev= 30
       0 2372.05      37 2367.04    77.7  2363.3   102.2 2362.31   138.8 2359.22
   199.9 2356.35  241.532352.506   441.9 2340.21   466.5 2340.41   470.8  2339.2
   478.9 2334.44     482 2333.37   494.6 2330.84  505.542329.595   578.2 2326.02
  590.772324.606   602.4 2324.06   616.9 2324.66   646.9 2323.78   719.7 2323.38
   728.9 2323.45   753.6 2325.65   762.9 2325.56   805.8 2329.49   818.5 2331.57
   843.9 2340.45   880.8 2356.39   898.9 2363.42   915.9 2368.97   927.4 2371.64
#Mann= 5 ,-1 , 0
       0     .05       0  241.53     .06       0  505.54     .05       0
  590.77    .045       0   616.9     .05       0
Bank Sta=590.77,616.9
XS Rating Curve= 0 ,0
Exp/Cntr(USF)=0,0
Exp/Cntr=0.3,0.1

Type RM Length L Ch R = 1 ,30059   ,221,221.8,222.1
XS GIS Cut Line= 4
2468428.36074481614508.7768247352468189.46224783614584.789982866
2467919.79652017 614669.85232649 2467780.4390636614716.908091048
#Sta/Elev= 30
       0 2359.71    88.9 2355.16   203.2  2347.2   207.4 2345.98   215.8 2339.62
     220 2338.09   248.2 2339.48  250.992339.214   257.8 2337.14   266.1 2332.09
   274.5 2328.16   283.2  2325.2   292.8 2323.72   312.3 2323.12   321.5  2322.1
   387.8 2320.55   429.9 2320.33   450.7 2319.32   463.3 2320.19   475.8 2319.88
   484.1 2318.42   488.4 2318.33   496.9 2318.98  500.442319.949   506.4 2321.13
   544.6 2324.79   585.6  2329.7   617.2 2335.48   664.5 2346.33   680.6 2348.11
#Mann= 4 ,-1 , 0
       0     .06       0  250.99     .05       0   475.8    .045       0
  500.44     .05       0
Bank Sta=475.8,500.44
XS Rating Curve= 0 ,0
Exp/Cntr(USF)=0,0
Exp/Cntr=0.3,0.1

Type RM Length L Ch R = 1 ,29837   ,230.4,230.2,228
XS GIS Cut Line= 4
2468256.42622047614353.1308342752468126.11794939614385.707902045
2467784.05873779614478.009594062 2467666.4193264 614525.06535862
#Sta/Elev= 30
       0 2339.74    4.162339.636    75.9 2337.66    80.1  2336.8    84.2 2333.98
    88.3 2332.66  103.832333.352   111.7 2333.75   121.3 2335.69   129.5 2335.77
     138 2335.02     142 2333.98   150.2 2329.13   175.1 2320.48   183.4 2318.82
     200 2317.31   232.7 2316.29     316 2316.53   324.3 2315.44   340.8 2316.29
   347.4 2315.94   357.4    2315   365.7 2315.97   392.5 2321.93   415.2 2324.86
   469.3 2330.61   512.5 2334.12   555.6  2338.4     598 2345.27   615.3 2348.92
#Mann= 5 ,-1 , 0
       0     .05       0    4.16     .06       0  103.83     .05       0
   347.4    .045       0   365.7     .05       0
Bank Sta=347.4,365.7
XS Rating Curve= 0 ,0
Exp/Cntr(USF)=0,0
Exp/Cntr=0.5,0.3

Type RM Length L Ch R = 1 ,29607   ,102.3,102.1,102.1
XS GIS Cut Line= 4
2468307.10165922614121.4716856832468032.00642027614195.675006716
2467787.67841199614278.9275132412467514.39301014614356.750508471
#Sta/Elev= 30
       0 2342.29    50.1 2337.46   91.732332.463   116.4 2329.91   164.6 2326.31
   170.2 2325.51   184.2 2327.55  191.572328.071   203.4 2327.84     207 2327.36
   215.8 2323.39   219.9 2322.75   244.8  2321.6   277.9 2320.74   307.4 2315.55
   319.7  2314.1   360.9 2312.34   387.7 2312.29   398.8 2311.47   408.8 2312.28
   480.6 2315.68   527.1 2318.86   552.3 2320.12   573.5 2321.81   627.2 2327.21
     648 2327.61   677.1 2330.28   760.7 2335.11   785.2  2337.2   827.2 2339.78
#Mann= 5 ,-1 , 0
       0    .055       0   91.73     .06       0  191.57     .05       0
   387.7    .045       0   408.8     .05       0
#XS Ineff= 2 , 0
             350  2321.3     450          2321.3
Permanent Ineff=
       F       F
Bank Sta=387.7,408.8
XS Rating Curve= 0 ,0
Exp/Cntr(USF)=0,0
Exp/Cntr=0.5,0.3

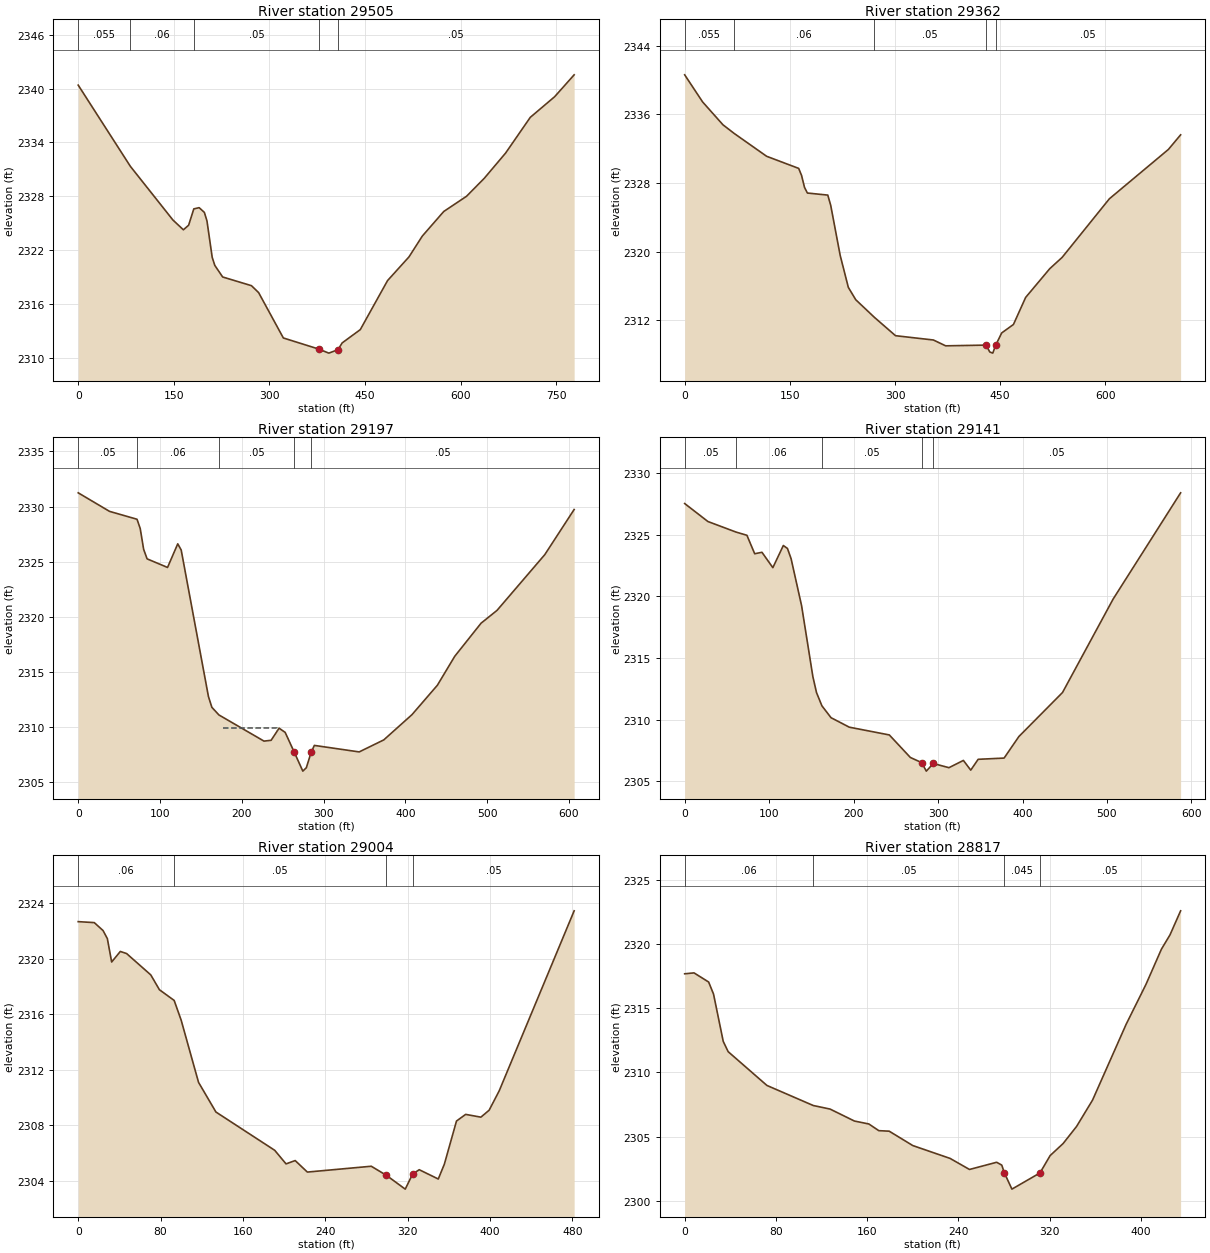
Type RM Length L Ch R = 1 ,29505   ,145,142.6,140.8
XS GIS Cut Line= 4
2468283.57377694614036.4093420592468008.47853799614099.753640502
2467731.57346194614186.6258212242467537.92089242614255.399630963
#Sta/Elev= 30
       0 2340.38   81.812331.328   148.6 2325.34     165 2324.25   173.2 2324.76
  181.342326.581   189.7 2326.72   197.9 2326.19     202 2325.24   210.2 2321.18
   214.3 2320.28   226.6 2318.99   271.8 2318.02     283 2317.25   321.8 2312.19
   377.9 2310.94   393.1  2310.5   407.4 2310.88   414.1 2311.64   442.5 2313.12
   485.3 2318.59   518.9 2321.23   539.8 2323.55   573.4 2326.29   609.2 2327.99
   637.1    2330   670.5 2332.81   709.2 2336.79   747.4 2339.09     778 2341.53
#Mann= 5 ,-1 , 0
       0    .055       0   81.81     .06       0  181.34     .05       0
   377.9    .045       0   407.4     .05       0
Bank Sta=377.9,407.4
XS Rating Curve= 0 ,0
Exp/Cntr(USF)=0,0
Exp/Cntr=0.5,0.3

Type RM Length L Ch R = 1 ,29362   ,167.7,165.2,161.8
XS GIS Cut Line= 4
2468247.37703498613886.1928628942468039.24576866613944.107650042
 2467771.3898781614030.9798307642467583.16681987614123.281522781
#Sta/Elev= 30
       0 2340.59    25.6 2337.43    54.6 2334.77   70.382333.775   116.9  2331.1
   162.6 2329.69   166.7 2328.87   170.9 2327.48     175 2326.82   204.1 2326.58
   208.3 2325.38   221.8 2319.55   233.4 2315.83     244 2314.39  270.532312.342
   300.7  2310.2   354.7  2309.7   372.2 2309.02   429.72309.104   435.2  2308.3
   439.4 2308.17   443.6  2309.1   452.1 2310.52   468.9 2311.51   486.3 2314.66
   520.6    2318   538.4 2319.33   605.7 2326.15   689.9  2331.9   707.3  2333.6
#Mann= 5 ,-1 , 0
       0    .055       0   70.38     .06       0  270.53     .05       0
   429.7    .045       0   443.6     .05       0
Bank Sta=429.7,443.6
XS Rating Curve= 0 ,0
Exp/Cntr(USF)=0,0
Exp/Cntr=0.5,0.3

Type RM Length L Ch R = 1 ,29197   ,57.4,56.3,55.6
XS GIS Cut Line= 4
2468131.49772636613783.3589143752467952.06323708613836.133764164
2467723.81201174613927.1703800492467581.31991731614026.123223403
#Sta/Elev= 30
       0 2331.24    38.3 2329.56    71.92328.846    75.8 2328.01      80 2326.12
    84.2 2325.26   109.2 2324.48   121.7 2326.62   125.9 2326.06   159.2 2312.79
   163.4 2311.81     172 2311.12   227.1 2308.75   235.8 2308.82   245.6 2309.92
     253 2309.54   264.1 2307.75   274.6 2306.03   278.9 2306.34   284.7 2307.72
   288.7 2308.36   343.5 2307.77   373.6 2308.86   408.1 2311.15   439.1 2313.81
   460.3 2316.43   492.5 2319.43     512 2320.59   570.4 2325.64   606.3 2329.73
#Mann= 5 ,-1 , 0
       0     .05       0    71.9     .06       0     172     .05       0
   264.1    .045       0   284.7     .05       0
#XS Ineff= 3 ,-1
  176.41  243.49 2309.95  244.28  247.72 2308.13     300   606.3  2308.1
Permanent Ineff=
       F       F       F
Bank Sta=264.1,284.7
XS Rating Curve= 0 ,0
Exp/Cntr(USF)=0,0
Exp/Cntr=0.5,0.3

Type RM Length L Ch R = 1 ,29141   ,128.2,137.3,137.2
XS GIS Cut Line= 4
2468107.74904395613712.1128671612467886.09467484613800.510740557
2467733.04761045613869.1180452822467564.16809113613933.767236273
#Sta/Elev= 30
       0 2327.55    27.5 2326.09   60.742325.233    73.7 2324.97    82.9 2323.47
    91.5 2323.59   104.4 2322.34   116.8 2324.14   121.7  2323.9     126 2323.07
   138.4 2319.26   151.8 2313.48   156.1 2312.19  162.482311.117   173.3 2310.15
   194.9 2309.38   242.3 2308.75   267.2 2306.92   280.62306.501   286.1 2305.81
   294.4 2306.43   312.9 2306.09     330 2306.68   338.7 2305.89   347.5 2306.77
   378.2 2306.87   395.7 2308.62   447.4  2312.2   507.3 2319.79   587.2 2328.42
#Mann= 5 ,-1 , 0
       0     .05       0   60.74     .06       0  162.48     .05       0
   280.6    .045       0   294.4     .05       0
Bank Sta=280.6,294.4
XS Rating Curve= 0 ,0
Exp/Cntr(USF)=0,0
Exp/Cntr=0.5,0.3

Type RM Length L Ch R = 1 ,29004   ,181.8,186.4,184.7
XS GIS Cut Line= 4
2468029.55004059 613646.167809282467880.46108993613696.303916579
2467644.29363713613821.644184827 2467590.1994161613840.115382252
#Sta/Elev= 30
       0 2322.69    15.6 2322.62    24.1 2322.05    28.3 2321.47    32.5 2319.78
    40.9 2320.54      47 2320.39    70.5 2318.85    78.9 2317.78   93.222317.008
     100 2315.59   116.9  2311.1   133.8 2308.96   190.9  2306.2   201.9 2305.22
   210.8 2305.46   222.6 2304.63   284.7 2305.05   299.3  2304.4   317.7  2303.4
   324.9 2304.49   331.3  2304.8   349.8 2304.13   355.7  2305.2   367.5 2308.31
   376.4 2308.79   391.2 2308.59   399.2 2309.09     409 2310.49   481.8 2323.47
#Mann= 4 ,-1 , 0
       0     .06       0   93.22     .05       0   299.3    .045       0
   324.9     .05       0
Bank Sta=299.3,324.9
XS Rating Curve= 0 ,0
Exp/Cntr(USF)=0,0
Exp/Cntr=0.3,0.1

Type RM Length L Ch R = 1 ,28817   ,63.1,61.3,54.5
XS GIS Cut Line= 4
 2467938.5134247613588.1154745122467782.82761783613644.848438035
2467616.58684099613729.2881976972467544.02142253613768.869335038
#Sta/Elev= 30
       0 2317.68     8.2 2317.75      21 2317.04    25.3  2316.1    33.8 2312.42
    38.1 2311.62    72.1 2308.99  112.722307.428   127.5 2307.15   148.8 2306.22
   161.5 2305.99   170.2 2305.47   179.3 2305.43     200 2304.31   232.7 2303.31
   249.7 2302.45   273.5 2303.01     278 2302.79   280.3 2302.18   286.9 2300.92
   311.5 2302.18   320.4 2303.53   331.8 2304.47   343.6  2305.8   357.6 2307.85
   387.1 2313.76   404.4 2316.85     418  2319.6   425.5 2320.71   434.8 2322.58
#Mann= 4 ,-1 , 0
       0     .06       0  112.72     .05       0   280.3    .045       0
   311.5     .05       0
Bank Sta=280.3,311.5
XS Rating Curve= 0 ,0
Exp/Cntr(USF)=0,0
Exp/Cntr=0.3,0.1

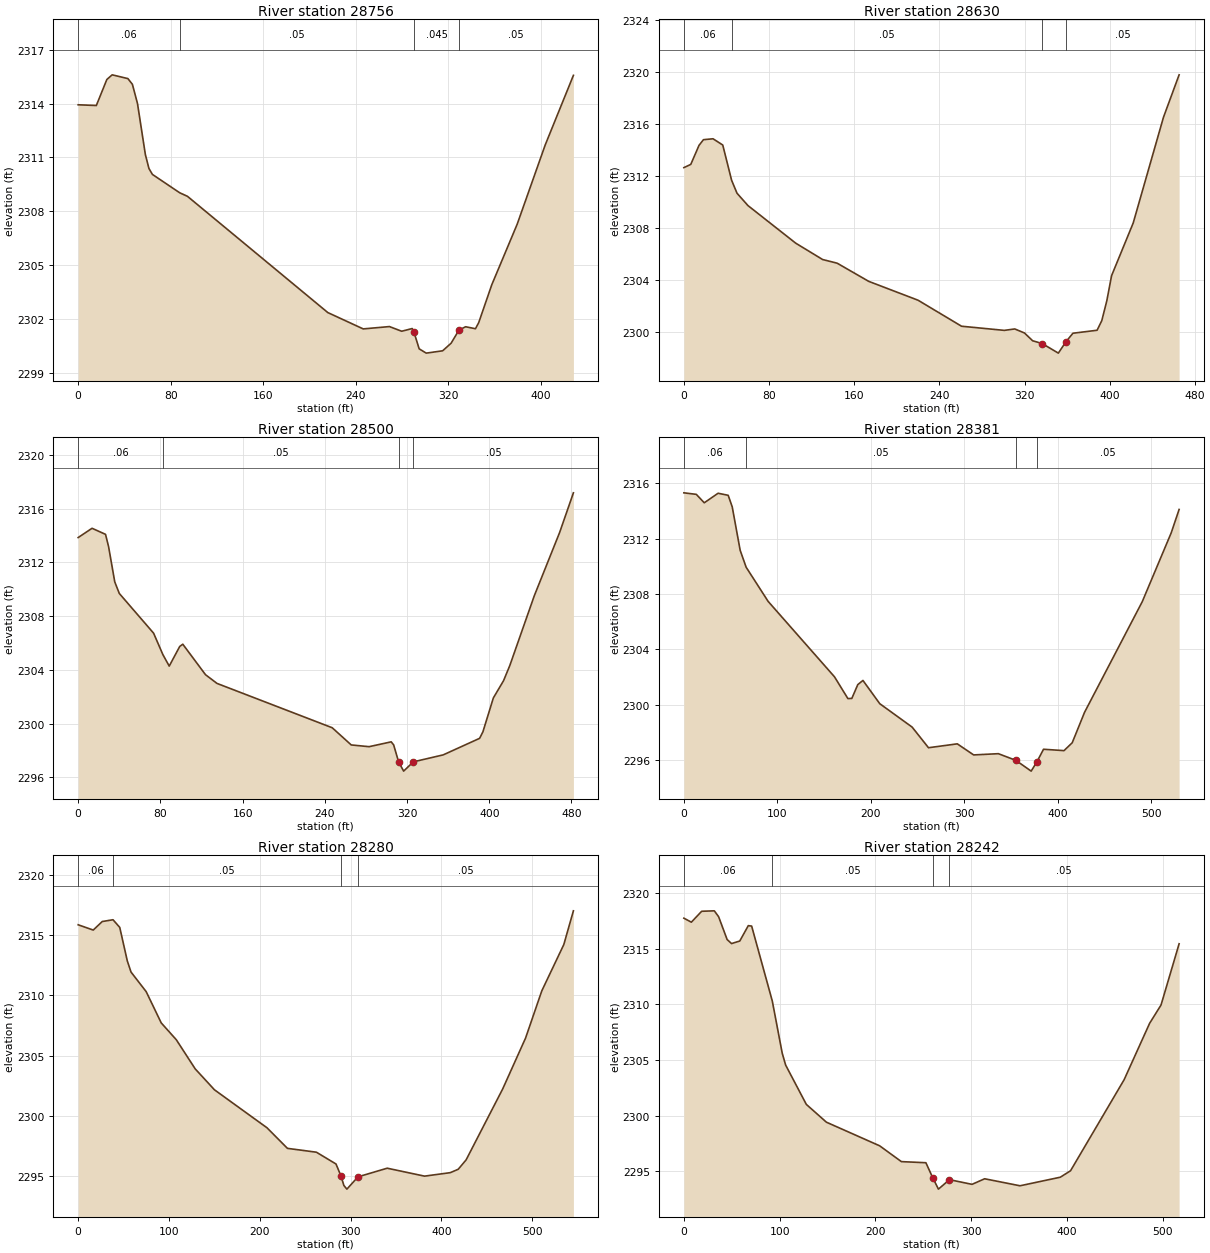
Type RM Length L Ch R = 1 ,28756   ,120.7,125.6,116.7
XS GIS Cut Line= 4
2467897.61291612613497.0788586272467736.64962426613568.324905841
2467582.28318863613704.2201440472467541.38268004613726.649455207
#Sta/Elev= 30
       0 2313.93    15.7 2313.89    24.8 2315.34    29.4  2315.6      43 2315.39
    46.9 2315.07    51.3    2314    58.1 2311.16    61.2 2310.38    64.2 2310.05
   87.772309.028    94.5 2308.83   215.9 2302.35   246.5 2301.44   269.2 2301.57
   279.8 2301.31   288.9 2301.46   290.5 2301.24   294.9 2300.33     301 2300.09
   315.2 2300.22   322.5 2300.64   329.4 2301.38   335.1 2301.56   343.6 2301.45
   346.4 2301.79   357.7  2303.9   379.7 2307.28   403.9 2311.69   428.3 2315.57
#Mann= 4 ,-1 , 0
       0     .06       0   87.77     .05       0   290.5    .045       0
   329.4     .05       0
Bank Sta=290.5,329.4
XS Rating Curve= 0 ,0
Exp/Cntr(USF)=0,0
Exp/Cntr=0.3,0.1

Type RM Length L Ch R = 1 ,28630   ,126.3,130.4,125.9
XS GIS Cut Line= 4
2467847.47680882613450.9008650622467661.44546331613543.256852192
2467475.41411781 613643.52906679 2467439.7910942613672.555234174
#Sta/Elev= 30
       0 2312.63     6.5 2312.88    14.2 2314.34    18.4 2314.78    27.4 2314.85
    36.5 2314.37   44.822311.662    49.9 2310.66    60.2 2309.71     105 2306.82
   130.3 2305.56   143.9 2305.28   173.6 2303.88   219.9 2302.43   260.7 2300.43
   300.9 2300.11   310.7 2300.22   319.8 2299.91   327.5 2299.31   336.4  2299.1
   351.6 2298.36   358.7 2299.23   365.3 2299.89     388 2300.12   392.4 2300.86
   397.1 2302.38   401.6 2304.32   421.9 2308.37   450.3  2316.5     465 2319.77
#Mann= 4 ,-1 , 0
       0     .06       0   44.82     .05       0   336.4    .045       0
   358.7     .05       0
Bank Sta=336.4,358.7
XS Rating Curve= 0 ,0
Exp/Cntr(USF)=0,0
Exp/Cntr=0.3,0.1

Type RM Length L Ch R = 1 ,28500   ,110.6,118.5,117.5
XS GIS Cut Line= 4
2467770.95327662613371.7385903792467562.49261996613469.372062488
2467413.40366931613569.644277086 2467365.9063045613623.738498119
#Sta/Elev= 30
       0 2313.85    13.5 2314.54    26.6 2314.09    29.6 2313.17    35.6 2310.55
      40 2309.69    73.4 2306.73   82.412305.138    88.6 2304.28    98.8 2305.74
   101.8 2305.91   123.9 2303.64   135.1 2302.99   247.2 2299.69   265.7 2298.41
   283.1 2298.28   304.6 2298.64     307 2298.41   311.8 2297.15   316.7 2296.46
   326.1 2297.15   355.2 2297.67   390.6  2298.9   393.8 2299.38     404 2301.91
   413.9 2303.19     420 2304.32   443.8 2309.51   468.5 2314.23   481.9 2317.18
#Mann= 4 ,-1 , 0
       0     .06       0   82.41     .05       0   311.8    .045       0
   326.1     .05       0
Bank Sta=311.8,326.1
XS Rating Curve= 0 ,0
Exp/Cntr(USF)=0,0
Exp/Cntr=0.3,0.1

Type RM Length L Ch R = 1 ,28381   ,90.4,101.4,95
XS GIS Cut Line= 4
2467747.20459422613312.3668843672467533.46645257 613391.52915905
2467338.19950836613479.9270324462467259.03723367613516.869427298
#Sta/Elev= 30
       0 2315.31    13.3  2315.2    21.8 2314.59    36.6 2315.28    47.4 2315.13
    51.7  2314.3    60.2 2311.16   66.57 2309.94    90.1 2307.47   161.1 2302.02
   175.4 2300.45   179.6 2300.46     186 2301.46   191.5 2301.76   209.5 2300.08
   244.1 2298.39   261.6  2296.9   292.4 2297.18   309.9 2296.38   336.3 2296.47
     355 2295.99   371.4 2295.21   377.6 2295.89   384.6 2296.79   406.5 2296.69
   415.3 2297.26   428.5 2299.46   490.2 2307.45   521.1 2312.41   529.6 2314.11
#Mann= 4 ,-1 , 0
       0     .06       0   66.57     .05       0     355    .045       0
   377.6     .05       0
Bank Sta=355,377.6
XS Rating Curve= 0 ,0
Exp/Cntr(USF)=0,0
Exp/Cntr=0.3,0.1

Type RM Length L Ch R = 1 ,28280   ,37.9,37.7,37.4
XS GIS Cut Line= 4
2467714.75418348613282.1346533412467468.56631717613352.251450707
2467309.63490981613419.2519459682467205.23878929613472.229081756
#Sta/Elev= 30
       0 2315.88    16.6 2315.44    26.5 2316.15   38.392316.299    45.8 2315.66
    54.1 2312.88    58.2 2311.95    74.9 2310.32    91.5 2307.72   108.1 2306.32
   128.9  2303.9   150.1 2302.16     208    2299   230.5 2297.29   262.4 2296.97
     284 2295.99   289.52294.987   292.7  2294.2     296  2293.9   308.2 2294.92
   340.4 2295.64   381.5 2294.98   409.9 2295.27   418.6 2295.55   427.3 2296.33
   467.6 2302.23   492.8 2306.46   510.7 2310.39   534.9 2314.23   545.5 2317.04
#Mann= 4 ,-1 , 0
       0     .06       0   38.39     .05       0   289.5    .045       0
   308.2     .05       0
Bank Sta=289.5,308.2
XS Rating Curve= 0 ,0
Exp/Cntr(USF)=0,0
Exp/Cntr=0.3,0.1

Type RM Length L Ch R = 1 ,28242   ,153.4,164.7,163.3
XS GIS Cut Line= 4
2467655.54444348 613221.366762292467474.79892138613307.065070182
2467243.41349007613411.4611907052467187.32005218613441.066060704
#Sta/Elev= 30
       0 2317.74     7.8 2317.38    18.6 2318.36    31.8  2318.4    36.3 2317.87
    45.2 2315.82    49.8 2315.46    58.4 2315.69    67.3 2317.07    70.8 2317.03
   92.372310.299   102.7 2305.63   106.3 2304.55   127.9 2301.02   148.9 2299.42
   204.5  2297.3   227.2 2295.88   252.8 2295.78   259.92294.441   265.9 2293.41
   277.4 2294.26     301 2293.84   314.2 2294.34   351.1 2293.71   393.2 2294.48
   403.9 2295.06   459.9 2303.24   486.5  2308.3   498.4 2309.94   517.3 2315.44
#Mann= 4 ,-1 , 0
       0     .06       0   92.37     .05       0   259.9    .045       0
   277.4     .05       0
Bank Sta=259.9,277.4
XS Rating Curve= 0 ,0
Exp/Cntr(USF)=0,0
Exp/Cntr=0.3,0.1

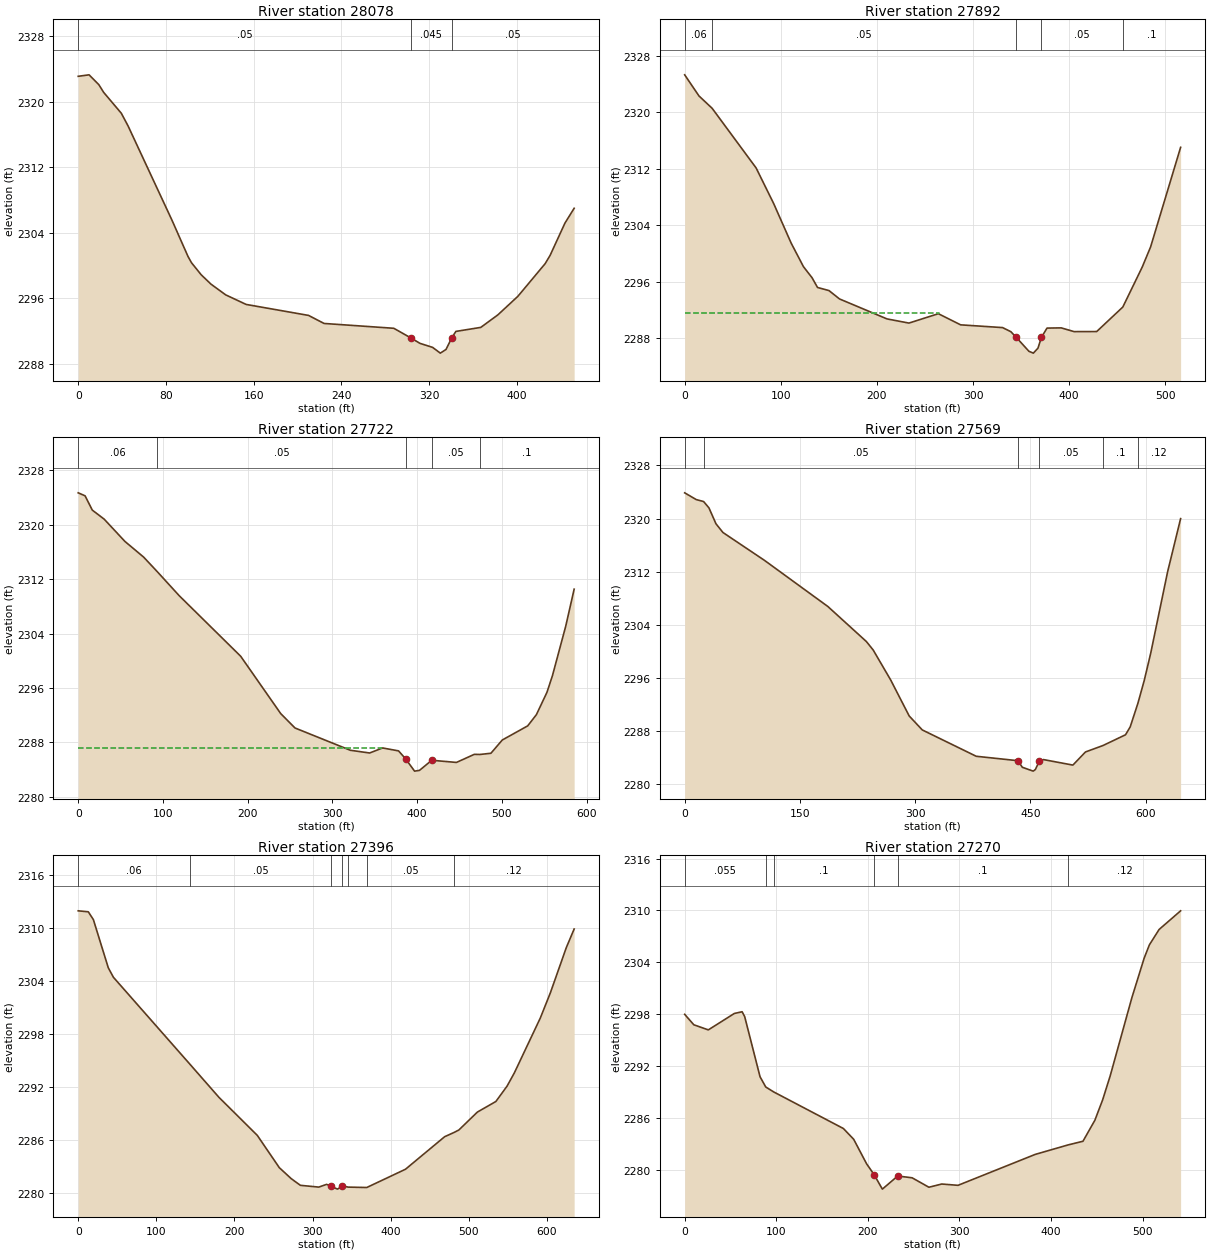
Type RM Length L Ch R = 1 ,28078   ,181.5,185.6,182.9
XS GIS Cut Line= 4
2467543.62105933613131.2495370632467382.13001897613209.620188999
2467185.01595501613344.9876787072467155.33010201 613360.42432227
#Sta/Elev= 30
       0  2323.1     9.9 2323.28    18.8 2322.08    23.2 2321.14    39.3 2318.59
    45.4 2317.06    85.5 2305.54     100 2301.15   103.2 2300.37   112.1 2298.89
     121 2297.75   134.4 2296.44   153.1 2295.27     210 2293.93   224.1 2292.95
   287.7 2292.36  302.942291.205   311.6 2290.52   323.1 2290.03   330.1 2289.33
   335.3 2289.78  340.572291.206   344.3 2291.98     367 2292.47   382.6    2294
   400.8 2296.26   425.7 2300.25   430.2 2301.26   443.7 2305.19   452.1    2307
#Mann= 3 ,-1 , 0
       0     .05       0  302.94    .045       0  340.57     .05       0
Bank Sta=302.94,340.57
XS Rating Curve= 0 ,0
Exp/Cntr(USF)=0,0
Exp/Cntr=0.3,0.1

Type RM Length L Ch R = 1 ,27892   ,169.8,169.5,170.8
XS GIS Cut Line= 4
2467455.75093443612995.8820473552467296.63476232613083.752172253
 2467037.7741241613244.055778486 2467014.0254417 613261.86729029
#Sta/Elev= 30
       0 2325.34    14.9 2322.34   28.582320.592    74.3 2312.14    92.5 2307.11
   110.8 2301.47   123.6 2298.13   132.5 2296.57   138.2 2295.19   150.1 2294.75
   161.1 2293.56   210.5 2290.73   233.3 2290.14   263.9 2291.47   287.1 2289.89
   330.7  2289.5   339.3 2288.92     3452288.107   358.1 2286.14   362.7 2285.88
   367.5 2286.58  371.082288.105   376.9 2289.43   391.7 2289.46   405.1 2288.93
   428.6 2288.94  455.782292.416     476 2298.09   484.7 2300.95   515.9 2315.06
#Mann= 5 ,-1 , 0
       0     .06       0   28.58     .05       0     345    .045       0
  371.08     .05       0  455.78      .1       0
#XS Ineff= 2 , 0
          264.52 2291.59
Permanent Ineff=
       F       F
Bank Sta=345,371.08
XS Rating Curve= 0 ,0
Exp/Cntr(USF)=0,0
Exp/Cntr=0.3,0.1

Type RM Length L Ch R = 1 ,27722   ,155.5,153.2,149.7
XS GIS Cut Line= 4
2467402.31639902612883.0758059322467161.26727261612973.320799071
2466933.27992152 613114.625459382466891.71972731613157.373087708
#Sta/Elev= 30
       0 2324.71     8.1 2324.27    16.6 2322.17    30.6 2320.84    55.1 2317.56
    77.2 2315.25   93.35  2313.1   119.1 2309.58   191.7 2300.66     239 2292.21
   255.8  2290.1   321.1 2286.82   343.9 2286.42   359.2 2287.16     378 2286.73
  386.312285.561   396.9 2283.75   402.7 2283.86   417.2 2285.35   446.3 2285.03
   467.4 2286.22  473.982286.202     487 2286.38   500.4 2288.33   530.4 2290.41
   540.7 2292.07   553.1 2295.35   559.5 2297.76   575.2 2305.05   585.2 2310.53
#Mann= 5 ,-1 , 0
       0     .06       0   93.35     .05       0  386.31    .045       0
   417.2     .05       0  473.98      .1       0
#XS Ineff= 2 , 0
          358.06 2287.18
Permanent Ineff=
       F       F
Bank Sta=386.31,417.2
XS Rating Curve= 0 ,0
Exp/Cntr(USF)=0,0
Exp/Cntr=0.3,0.1

Type RM Length L Ch R = 1 ,27569   ,170.5,172.8,173.5
XS GIS Cut Line= 4
2467302.57193292612694.2737808142467052.02333355612829.641270521
2466862.03387431613006.5689544382466795.53756358613082.564738133
#Sta/Elev= 30
       0 2323.88    15.1 2322.86   24.662322.565    31.6 2321.61    40.7 2319.22
    49.8  2317.9   103.6 2313.72   186.3 2306.75   236.5 2301.46   245.3 2300.19
     268 2295.69   292.2 2290.24   309.2 2288.14   379.4 2284.17   433.7  2283.5
   439.4 2282.51   453.6 2281.93   456.4 2282.18   461.4 2283.41   466.9 2283.67
   505.2 2282.84   521.6 2284.82  544.442285.792   573.7 2287.41   579.8  2288.6
  589.862292.174     598 2295.57   606.5 2299.71   628.4 2311.94   645.4 2319.99
#Mann= 6 ,-1 , 0
       0    .055       0   24.66     .05       0   433.7    .045       0
   461.4     .05       0  544.44      .1       0  589.86     .12       0
Bank Sta=433.7,461.4
XS Rating Curve= 0 ,0
Exp/Cntr(USF)=0,0
Exp/Cntr=0.3,0.1

Type RM Length L Ch R = 1 ,27396   ,129.5,126.3,122.9
XS GIS Cut Line= 4
2467088.83379128612602.8413535552466921.40558032612735.833975022
2466731.41612108612881.8883718122466578.23711957612979.257969672
#Sta/Elev= 30
       0 2311.92    12.9 2311.81    19.4 2310.93    38.5 2305.47    45.1 2304.39
  143.142294.531   180.1  2290.8   229.3 2286.48   257.5 2282.82   272.7 2281.58
   284.5 2280.82     308 2280.62   318.1 2280.93   323.8 2280.71     332 2280.39
   338.3 2280.75  345.712280.618  369.442280.573     419 2282.64   469.2 2286.33
  481.072286.802   487.4 2287.09   511.1 2289.12   534.8 2290.32   549.1 2292.06
   558.5 2293.57   591.7 2299.78   604.5 2302.62   624.9 2307.74     635 2309.86
#Mann= 7 ,-1 , 0
       0     .06       0  143.14     .05       0   323.8    .045       0
   338.3     .05       0  345.71      .1       0  369.44     .05       0
  481.07     .12       0
Bank Sta=323.8,338.3
XS Rating Curve= 0 ,0
Exp/Cntr(USF)=0,0
Exp/Cntr=0.3,0.1

Type RM Length L Ch R = 1 ,27270   ,137.1,139.6,133.9
XS GIS Cut Line= 4
2466928.53018504612548.2193840242466801.47473418612661.025625447
2466648.29573266612828.453836401 2466550.9261348612935.322907223
#Sta/Elev= 30
       0 2297.98      10 2296.77    25.8 2296.18    54.2 2298.08    62.7 2298.28
    65.5 2297.72    82.3 2290.75   88.482289.574   97.212288.998   173.2 2284.77
   184.5 2283.52   198.6 2280.68  206.71 2279.44   215.8 2277.75   232.6 2279.27
   248.3 2279.06   266.6 2277.97   280.6 2278.34   298.4 2278.19   382.7 2281.77
   418.82282.874   434.8 2283.29   447.8 2285.72   456.3 2288.09   464.5 2290.85
   488.2 2299.91   501.6 2304.48   507.3 2306.02   517.9  2307.8   541.4 2309.96
#Mann= 6 ,-1 , 0
       0    .055       0   88.48     .06       0   97.21      .1       0
  206.71    .045       0   232.6      .1       0   418.8     .12       0
Bank Sta=206.71,232.6
XS Rating Curve= 0 ,0
Exp/Cntr(USF)=0,0
Exp/Cntr=0.3,0.1

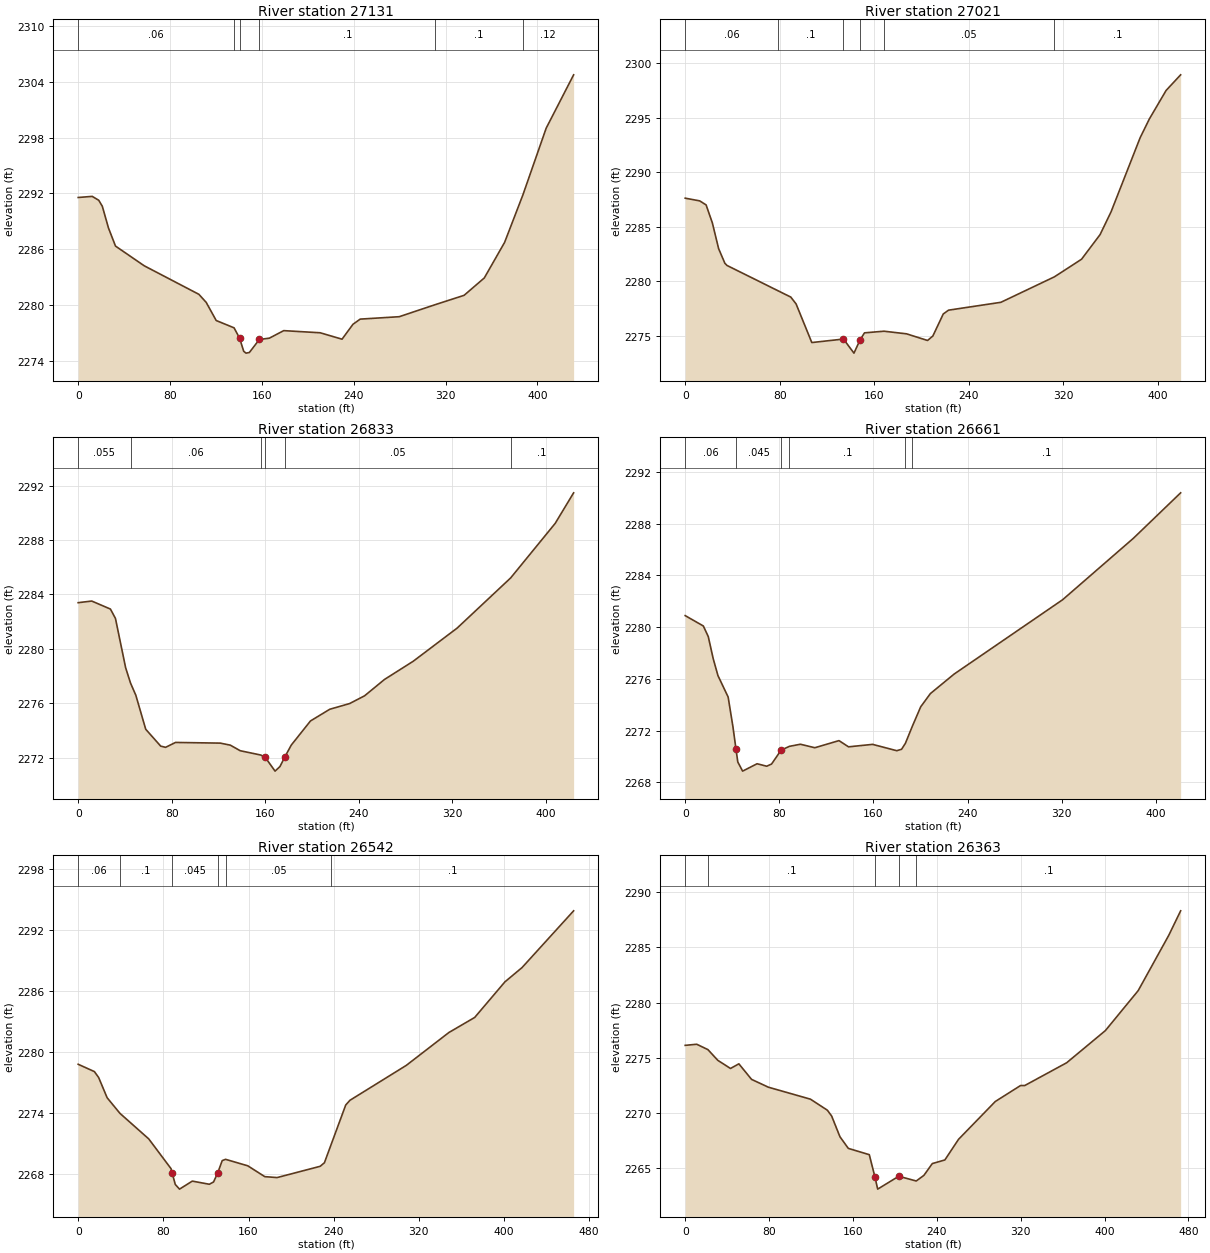
Type RM Length L Ch R = 1 ,27131   ,110.4,109.9,108.8
XS GIS Cut Line= 4
2466768.22657881612535.1576087012466698.16796571612614.715694757
2466604.36067022612760.7700915472466535.48949124612896.137581255
#Sta/Elev= 30
       0 2291.56    12.2 2291.68    17.9 2291.26      21 2290.62    26.4 2288.27
    32.5 2286.33    57.5 2284.21   105.1 2281.14   111.5 2280.27   120.2 2278.32
  135.752277.532   140.5 2276.44   144.2    2275   146.2 2274.81   149.1 2274.88
   157.8 2276.28   166.5 2276.42     179 2277.23   210.8    2277   229.8 2276.31
   239.3 2277.91   245.6 2278.47   279.6 2278.73  311.192280.036   336.1 2281.03
   353.7  2282.9   371.4 2286.73  387.342291.846   407.6 2299.02   431.5 2304.76
#Mann= 6 ,-1 , 0
       0     .06       0  135.75      .1       0   140.5    .045       0
   157.8      .1       0  311.19      .1       0  387.34     .12       0
Bank Sta=140.5,157.8
XS Rating Curve= 0 ,0
Exp/Cntr(USF)=0,0
Exp/Cntr=0.3,0.1

Type RM Length L Ch R = 1 ,27021   ,185.7,188.1,185.5
XS GIS Cut Line= 4
2466655.42033739612493.5974144922466605.54810434612550.594252264
2466523.61515004612718.0224632182466471.36804875612866.451728249
#Sta/Elev= 30
       0 2287.61    12.3 2287.36    17.7 2286.99      23 2285.34    28.3 2282.98
    33.6 2281.64    35.4 2281.44   78.552279.121    89.4 2278.54    93.9 2277.91
   107.2 2274.37     134 2274.69   142.9  2273.4     1482274.601   151.8 2275.26
  168.29 2275.41   187.4 2275.17   205.2 2274.56   209.7 2274.97   218.5 2276.99
     223 2277.34   267.3 2278.06  312.642280.397   335.6 2282.01   351.3 2284.27
   360.6 2286.36   385.2 2293.15     393 2294.87   407.2 2297.49   419.5 2298.92
#Mann= 6 ,-1 , 0
       0     .06       0   78.55      .1       0     134    .045       0
     148      .1       0  168.29     .05       0  312.64      .1       0
Bank Sta=134,148
XS Rating Curve= 0 ,0
Exp/Cntr(USF)=0,0
Exp/Cntr=0.3,0.1

Type RM Length L Ch R = 1 ,26833   ,172.6,171.7,149.3
XS GIS Cut Line= 4
2466516.49054532612429.4759719992466497.49159939612474.598468568
2466422.68324982 612680.024571372466397.74713329612834.391007002
#Sta/Elev= 30
       0 2283.39    11.6 2283.51    27.6 2282.92    31.9 2282.23    40.6 2278.61
   44.792277.478    49.3 2276.59    57.8 2274.08    70.6 2272.84    74.8 2272.75
    83.3 2273.11   121.6 2273.06   130.2 2272.91   138.7  2272.5  156.252272.184
     160 2272.02   168.5    2271   172.7 2271.34     177 2272.07   182.4 2272.92
   198.8 2274.69   215.3 2275.55   232.3 2275.97   245.1 2276.54   262.1 2277.74
   286.7 2279.08   324.3 2281.52  370.142285.213   408.2 2289.22     424 2291.47
#Mann= 6 ,-1 , 0
       0    .055       0   44.79     .06       0  156.25     .05       0
     160    .045       0     177     .05       0  370.14      .1       0
Bank Sta=160,177
XS Rating Curve= 0 ,0
Exp/Cntr(USF)=0,0
Exp/Cntr=0.3,0.1

Type RM Length L Ch R = 1 ,26661   ,120,118.9,110.1
XS GIS Cut Line= 4
2466400.12200153612404.5398554742466388.24766033612436.600576721
2466350.24976848612612.3408265172466336.00055904612818.954363439
#Sta/Elev= 30
       0 2280.89    15.4 2280.09    19.6 2279.27    23.8 2277.56    27.8 2276.26
    36.5 2274.59    40.6 2272.28   43.122270.595    44.7 2269.57    48.8 2268.86
    61.1 2269.43    69.3 2269.24    73.4 2269.41    81.5 2270.48   88.582270.777
    97.9 2270.94   110.2 2270.67   130.7 2271.22   138.8 2270.74   159.3 2270.93
   179.8 2270.44   183.9 2270.55  187.152271.011  193.072272.333   200.2 2273.84
   208.4 2274.86   228.6 2276.37   320.8 2282.12   380.9 2286.87   421.1 2290.39
#Mann= 6 ,-1 , 0
       0     .06       0   43.12    .045       0    81.5     .06       0
   88.58      .1       0  187.15     .05       0  193.07      .1       0
Bank Sta=43.12,81.5
XS Rating Curve= 0 ,0
Exp/Cntr(USF)=0,0
Exp/Cntr=0.3,0.1

Type RM Length L Ch R = 1 ,26542   ,179.4,179.1,169.8
XS GIS Cut Line= 4
2466276.62885303612367.7293977472466274.25398479612417.601630797
2466268.31681419  612628.96490422466298.00266719612830.828704641
#Sta/Elev= 30
       0 2278.77    15.2 2278.05    19.2 2277.47    27.2 2275.47   39.212273.934
    66.3 2271.41    87.2 2268.48   88.232268.087    91.2 2266.92    95.2 2266.46
   107.2 2267.25   123.2 2266.94   127.2 2267.17  131.05 2268.06   135.3 2269.27
  138.432269.398   159.3 2268.76   175.3 2267.69   186.9  2267.6   227.3 2268.71
   231.3 2269.06   237.62270.855   251.3 2274.75   255.3 2275.22   308.2 2278.66
   348.2  2281.9   372.5 2283.39   400.8 2286.89     417 2288.31   465.4  2293.9
#Mann= 6 ,-1 , 0
       0     .06       0   39.21      .1       0   88.23    .045       0
  131.05      .1       0  138.43     .05       0   237.6      .1       0
Bank Sta=88.23,131.05
XS Rating Curve= 0 ,0
Exp/Cntr(USF)=0,0
Exp/Cntr=0.3,0.1

Type RM Length L Ch R = 1 ,26363   ,186,185.9,181.1
XS GIS Cut Line= 4
2466113.95037856612311.9199940952466102.07603735612436.600576721
2466111.57551032612604.028787675 2466122.2624174612783.331339832
#Sta/Elev= 30
       0 2276.11      11 2276.21   21.672275.723    31.1 2274.75    43.2 2274.01
    51.2 2274.43    63.3 2273.02    79.3 2272.31   119.5 2271.22   135.6 2270.22
   139.7 2269.69   147.6 2267.81   155.6 2266.75   175.6 2266.18   181.1 2264.11
   183.6 2263.05   203.7 2264.22  220.382263.789   227.7  2264.3   235.7 2265.37
   247.7  2265.7   260.7 2267.57   295.8 2271.01   319.9 2272.46   323.9 2272.46
   363.9 2274.53   400.8 2277.45   432.1 2281.08   461.3 2286.11   472.6 2288.33
#Mann= 5 ,-1 , 0
       0    .055       0   21.67      .1       0   181.1    .045       0
   203.7      .1       0  220.38      .1       0
Bank Sta=181.1,203.7
XS Rating Curve= 0 ,0
Exp/Cntr(USF)=0,0
Exp/Cntr=0.3,0.1