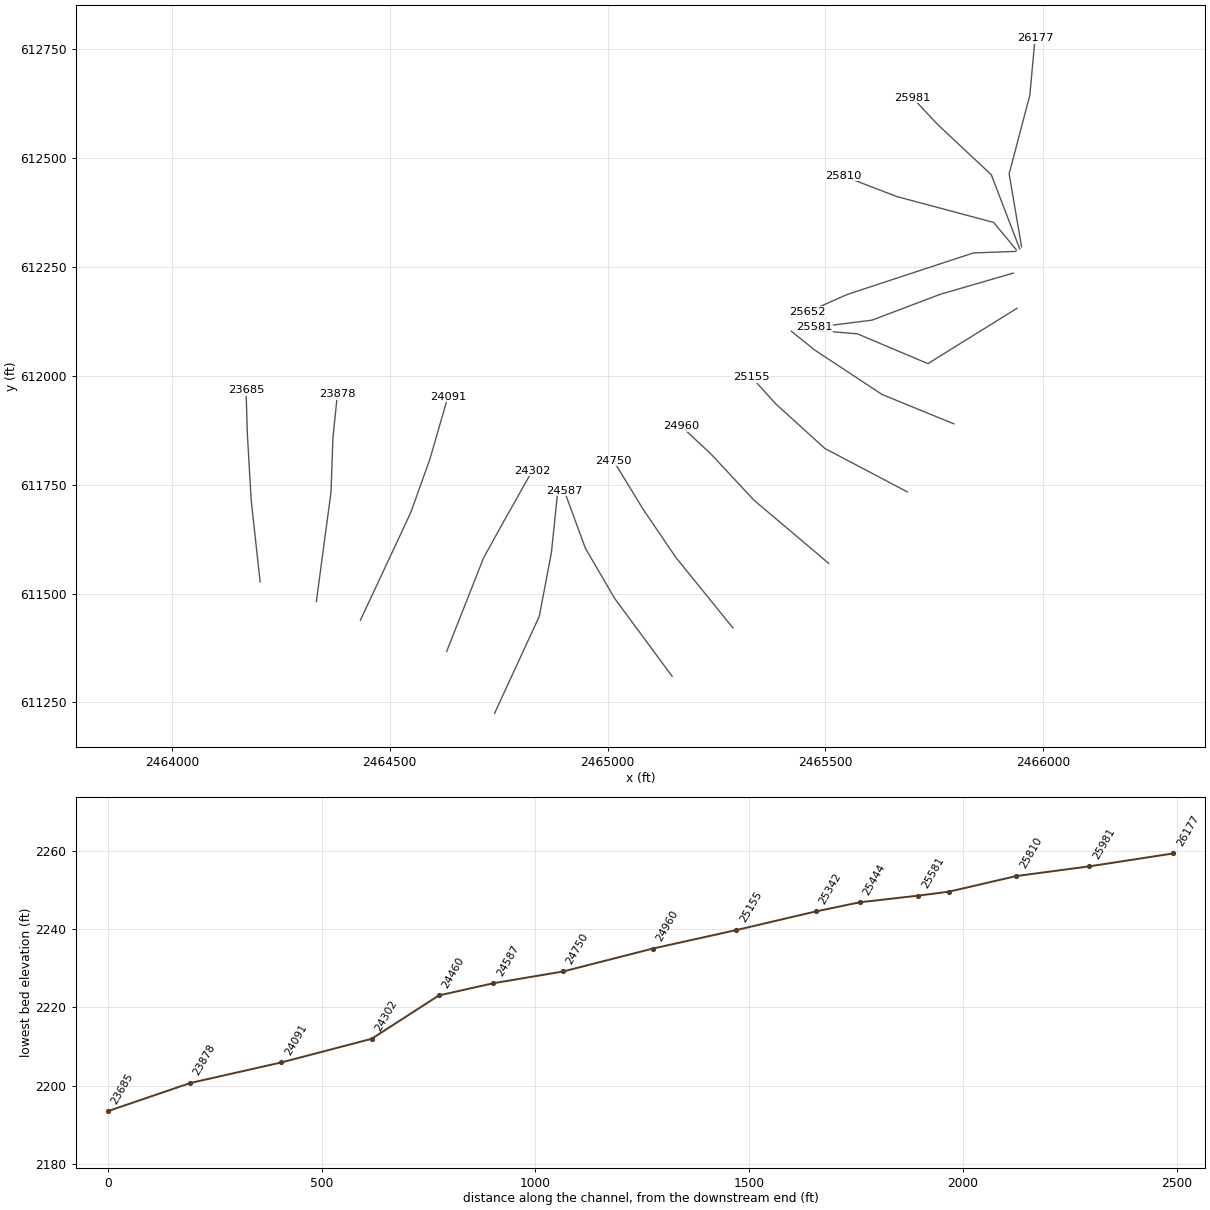
HEC-RAS study TROUTRN.prj: TROUTRN

--- TROUTRN.g01 (geometry) --- (continued)

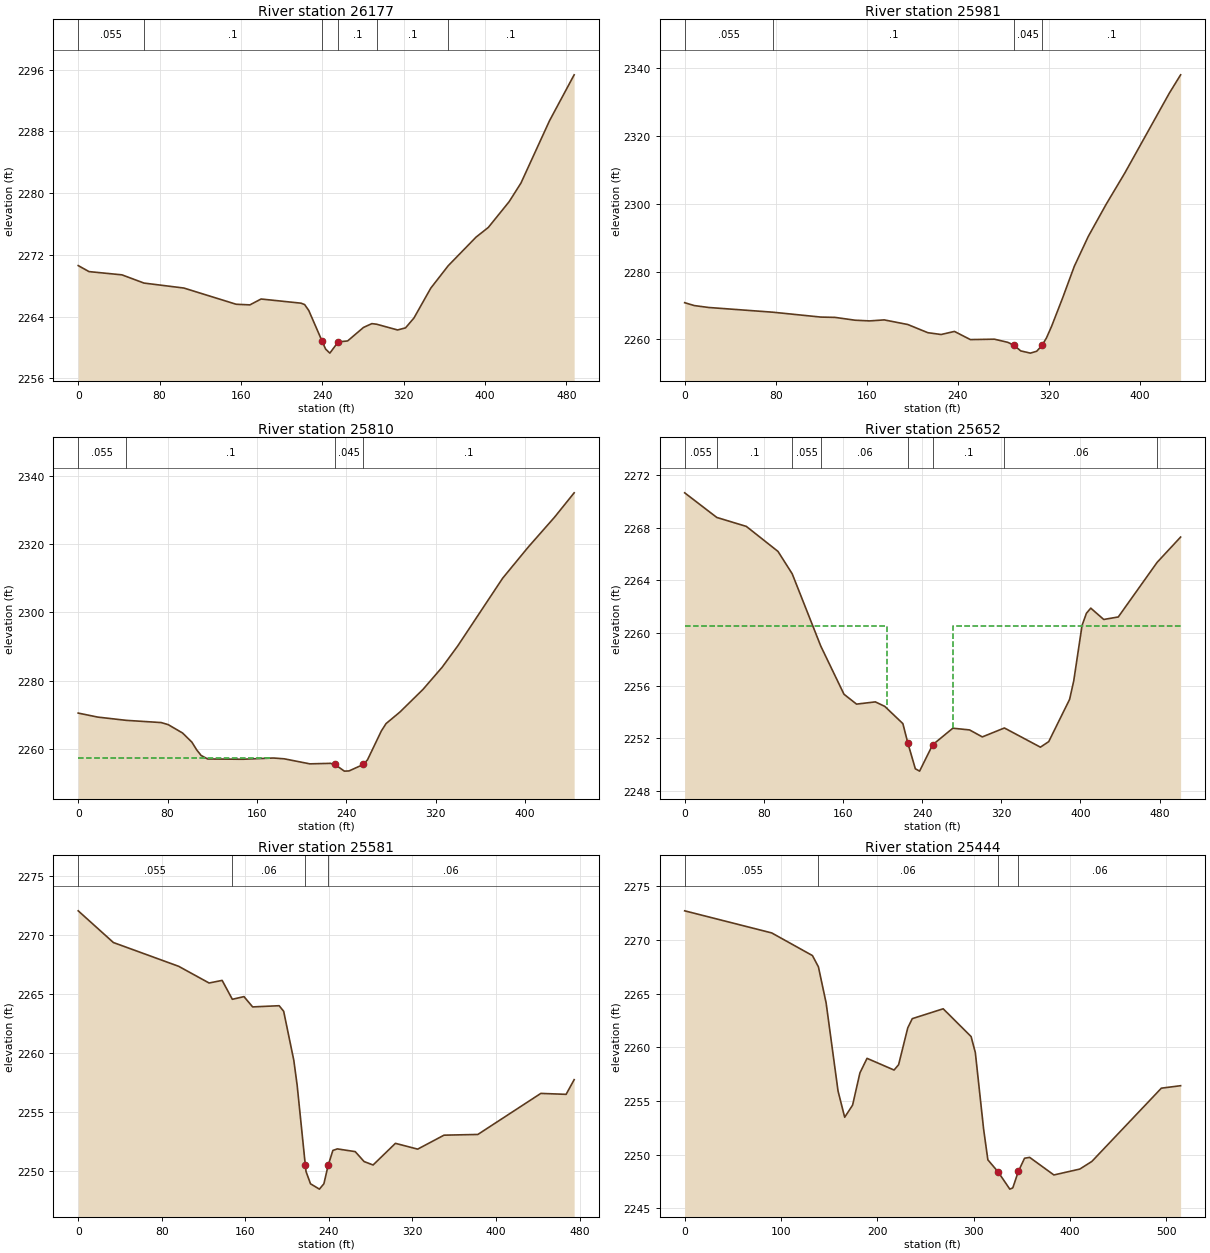
Type RM Length L Ch R = 1 ,26177   ,181,196.3,205.9
XS GIS Cut Line= 4
2465950.08446996612296.4833505322465921.58605108612463.911561486
2465969.08341589612644.4015477632465980.95775709 612775.01930099
#Sta/Elev= 30
       0 2270.61    10.6 2269.83      43 2269.41   64.742268.343   103.9  2267.7
   155.3  2265.6   168.8 2265.52   179.8 2266.28   219.1 2265.74   222.6 2265.56
   226.7 2264.79   239.8 2260.82   243.2  2259.8   247.4 2259.27   255.6 2260.72
   264.9 2260.85   280.5  2262.6   288.7 2263.09  293.392263.014     314 2262.27
   321.8 2262.54   330.1 2263.82   346.6 2267.68  363.77 2270.59   391.1 2274.29
   403.2 2275.55   423.7 2278.89   435.3  2281.3   463.4 2289.38   487.6 2295.32
#Mann= 6 ,-1 , 0
       0    .055       0   64.74      .1       0   239.8    .045       0
   255.6      .1       0  293.39      .1       0  363.77      .1       0
Bank Sta=239.8,255.6
XS Rating Curve= 0 ,0
Exp/Cntr(USF)=0,0
Exp/Cntr=0.3,0.1

Type RM Length L Ch R = 1 ,25981   ,163.8,171,176
XS GIS Cut Line= 4
2465946.04992505612291.2123304722465880.60758084 612461.82987073
2465758.29272322612576.3539730952465699.86205874612638.680015198
#Sta/Elev= 30
       0 2270.84     8.5 2269.99    21.1 2269.43   77.482268.037   119.6  2266.6
   132.1 2266.51   149.6 2265.68   162.5 2265.47   175.3 2265.77     196 2264.41
   213.6    2262   225.3 2261.46     237 2262.37     251 2259.96   272.1 2260.08
   283.9 2259.15  289.462258.262   295.2 2256.63   303.7 2255.97   309.3 2256.53
  313.962258.261   317.8 2260.43   322.3 2263.84     332 2272.21   342.3 2281.57
   354.6  2290.4   370.2 2299.82   386.7  2309.1   425.7 2332.59   435.7 2338.04
#Mann= 4 ,-1 , 0
       0    .055       0   77.48      .1       0  289.46    .045       0
  313.96      .1       0
Bank Sta=289.46,313.96
XS Rating Curve= 0 ,0
Exp/Cntr(USF)=0,0
Exp/Cntr=0.3,0.1

Type RM Length L Ch R = 1 ,25810   ,151.5,157.6,165.6
XS GIS Cut Line= 4
2465938.21012876 612289.358745812465885.96302747612352.292754183
2465663.91284698612411.6644601962465540.41969848612459.161825005
#Sta/Elev= 30
       0  2270.5    17.6 2269.32   43.032268.371    74.3 2267.72    80.6 2267.11
    93.4 2264.67   101.7 2262.01   106.1 2259.71     110 2258.09   115.9 2257.05
   147.2 2256.97   174.8 2257.33   184.4  2257.1   207.4 2255.62   225.9 2255.77
  229.742255.439   238.3 2253.49   242.5 2253.55  255.252255.441     259 2256.81
   271.4 2265.27   275.6 2267.42     288  2270.8   308.7 2277.45   325.8 2283.93
   339.8 2290.19     380 2310.03   402.9 2319.15   426.5 2327.93     444 2335.05
#Mann= 4 ,-1 , 0
       0    .055       0   43.03      .1       0  229.74    .045       0
  255.25      .1       0
#XS Ineff= 2 , 0
          172.04 2257.47
Permanent Ineff=
       F       F
Bank Sta=229.74,255.25
XS Rating Curve= 0 ,0
Exp/Cntr(USF)=0,0
Exp/Cntr=0.5,0.3

Type RM Length L Ch R = 1 ,25652   ,70.4,71.2,70.7
XS GIS Cut Line= 4
2465937.02269464 612285.796443452465839.65309678612282.234141089
2465551.10660556 612187.23941147 2465459.6741783612146.866651381
#Sta/Elev= 30
       0 2270.64   32.46 2268.77    62.3 2268.09    94.3 2266.19  108.662264.491
  137.552258.997     161 2255.34   173.7 2254.59   192.7 2254.76   202.2 2254.42
   220.5 2253.11  225.632251.608   233.1 2249.68   237.4  2249.5   250.6  2251.5
     271 2252.76   287.9 2252.63   300.8  2252.1  323.122252.777   359.5 2251.32
   367.9 2251.74     389 2254.95   393.2 2256.36   401.6 2260.57     406 2261.49
   410.4 2261.88   423.5 2261.02   438.2 2261.21  477.47 2265.36   501.2 2267.28
#Mann= 8 ,-1 , 0
       0    .055       0   32.46      .1       0  108.66    .055       0
  137.55     .06       0  225.63    .045       0   250.6      .1       0
  323.12     .06       0  477.47      .1       0
#XS Ineff= 2 , 0
             204  2260.5     271          2260.5
Permanent Ineff=
       F       F
Bank Sta=225.63,250.6
XS Rating Curve= 0 ,0
Exp/Cntr(USF)=0,0
Exp/Cntr=0.5,0.3

Type RM Length L Ch R = 1 ,25581   ,180.2,137.6,163.7
XS GIS Cut Line= 4
2465931.08552404  612235.92421042465763.65731308 612187.23941147
2465606.91600921612127.8677054572465475.11082187612111.243627774
#Sta/Elev= 30
       0 2272.02    33.7 2269.34    96.2 2267.33   125.3 2265.92   137.8 2266.14
  147.552264.543   158.7 2264.77     167  2263.9   192.4    2264   196.7 2263.53
   206.4 2259.39   209.6 2257.29  217.452250.506   218.1 2249.99   222.4 2248.95
   230.9  2248.5   235.2 2248.95  239.282250.505   243.8 2251.77   248.1  2251.9
   265.2 2251.67   273.7 2250.83   282.3 2250.54   303.7 2252.37     325 2251.88
   350.2 2253.06   382.6 2253.12   442.9 2256.59   467.1 2256.51   474.8 2257.75
#Mann= 4 ,-1 , 0
       0    .055       0  147.55     .06       0  217.45    .045       0
  239.28     .06       0
Bank Sta=217.45,239.28
XS Rating Curve= 0 ,0
Exp/Cntr(USF)=0,0
Exp/Cntr=0.5,0.3

Type RM Length L Ch R = 1 ,25444   ,93.2,101.7,87.1
XS GIS Cut Line= 4
2465939.46704543612155.0240204092465735.20695502612027.984208082
2465573.29346872 612096.486067672465474.89988859612104.581741985
#Sta/Elev= 30
       0 2272.72    90.4 2270.66   132.7 2268.55   138.9  2267.5   146.9 2264.14
   159.3 2255.92   166.2 2253.48   174.4 2254.61     182 2257.61   189.4 2258.97
   217.5 2257.88   222.2 2258.38   231.7 2261.81   236.4 2262.67   268.5 2263.59
   297.5    2261   301.9  2259.5   310.5 2252.36   314.9 2249.51   325.5 2248.39
   337.7 2246.78   340.8  2246.9   346.62248.438     353 2249.66   358.3 2249.74
   383.5  2248.1   410.4 2248.65   422.9 2249.36   495.1 2256.19   515.1 2256.42
#Mann= 4 ,-1 , 0
       0    .055       0   138.9     .06       0   325.5    .045       0
   346.6     .06       0
Bank Sta=325.5,346.6
XS Rating Curve= 0 ,0
Exp/Cntr(USF)=0,0
Exp/Cntr=0.3,0.1

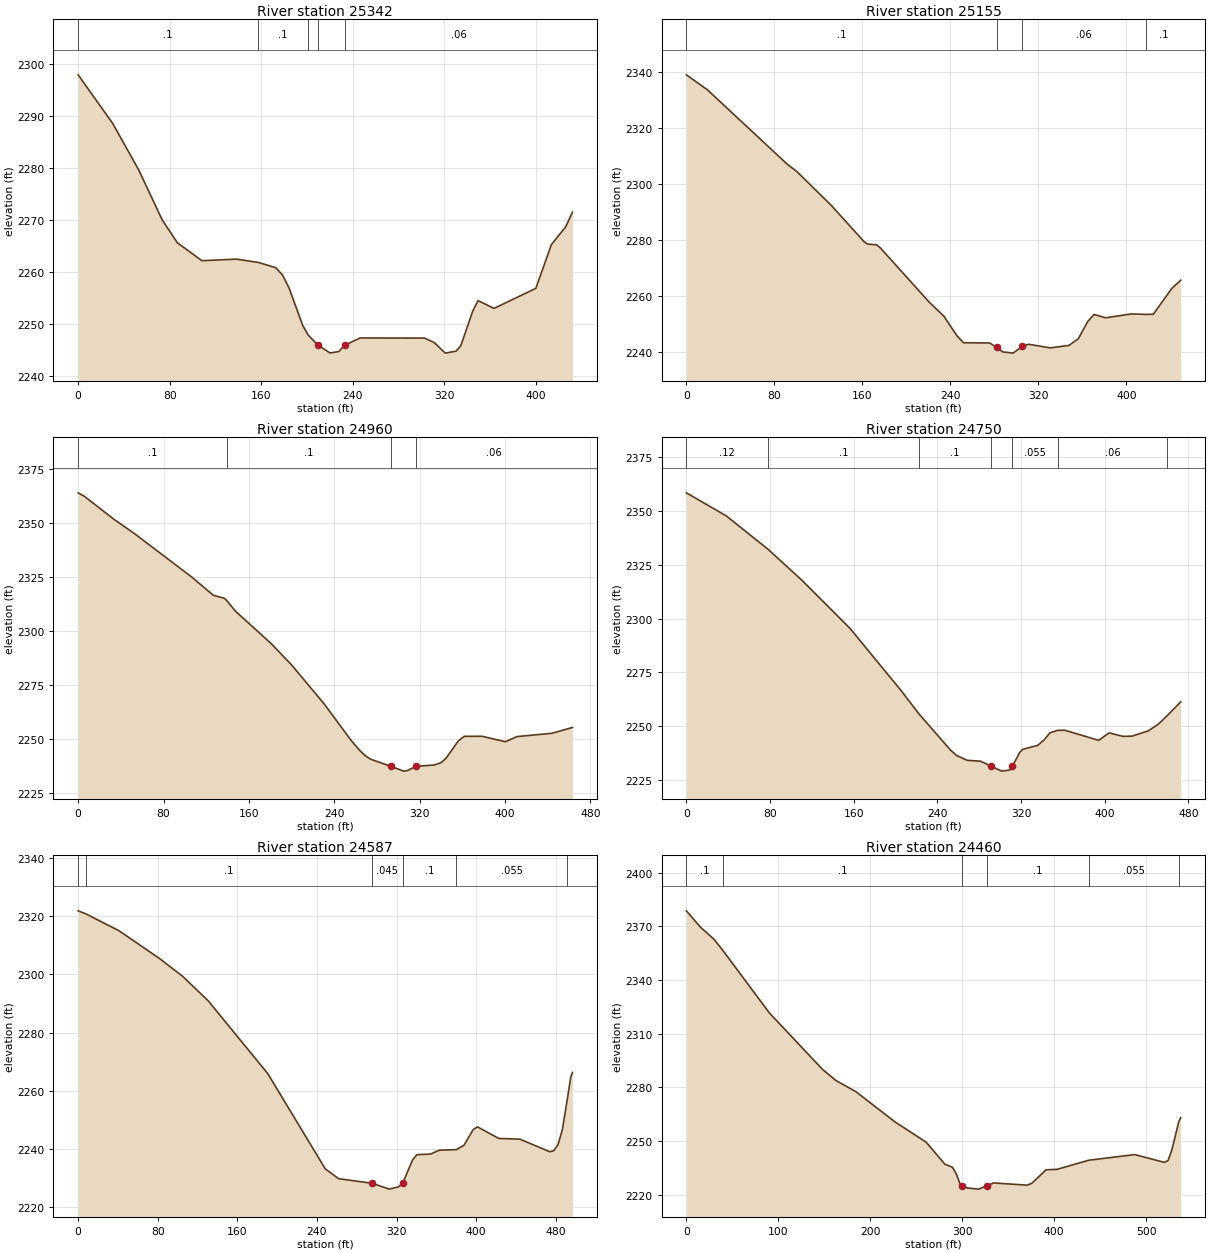
Type RM Length L Ch R = 1 ,25342   ,171.6,186.4,166.5
XS GIS Cut Line= 4
2465794.72973291611889.7522537862465630.15136385611957.079768403
2465476.25990186612058.6053856842465421.75667574612102.421704721
#Sta/Elev= 30
       0    2298    30.2 2288.66      53 2279.69    73.5 2270.09    86.7 2265.71
   108.2 2262.25   138.3 2262.55  157.452261.915   172.6 2260.92   178.7 2259.49
   184.5 2256.93   196.3  2249.8   201.1 2247.94  209.49 2246.04   220.2  2244.5
   227.8 2244.77  232.88 2245.96   246.5 2247.39   302.8 2247.36   311.3  2246.5
   320.9 2244.47   330.5 2244.86   334.6 2245.95   344.8 2252.48   349.6 2254.57
   363.5 2253.07   400.1 2256.93   413.7 2265.35   426.1 2268.74   432.1 2271.59
#Mann= 5 ,-1 , 0
       0      .1       0  157.45      .1       0   201.1     .06       0
  209.49    .045       0  232.88     .06       0
Bank Sta=209.49,232.88
XS Rating Curve= 0 ,0
Exp/Cntr(USF)=0,0
Exp/Cntr=0.3,0.1

Type RM Length L Ch R = 1 ,25155   ,196,194.7,194.2
XS GIS Cut Line= 4
2465687.74924852611733.5606879322465498.63937011 611833.24651531
2465385.75983028611935.864278788 2465330.0530444611997.434936875
#Sta/Elev= 30
       0 2338.97    19.2 2333.61    91.6 2307.13   100.6 2304.42     132 2292.29
   161.6 2279.43   164.6 2278.62     173 2278.32   176.4 2277.22   220.5    2258
   234.1 2252.88     246 2245.89   251.9 2243.41   275.7 2243.32  282.032241.747
   287.6 2240.14     297  2239.7   305.4  2242.1   311.1 2242.86     331 2241.57
     348 2242.48   356.4 2244.88   364.9    2251   370.6  2253.5   381.2  2252.3
   404.6 2253.69  417.882253.516   424.5 2253.56   441.4 2262.81   449.4 2265.71
#Mann= 4 ,-1 , 0
       0      .1       0  282.03    .045       0   305.4     .06       0
  417.88      .1       0
Bank Sta=282.03,305.4
XS Rating Curve= 0 ,0
Exp/Cntr(USF)=0,0
Exp/Cntr=0.3,0.1

Type RM Length L Ch R = 1 ,24960   ,212.6,210.6,208.9
XS GIS Cut Line= 4
2465507.43517841611569.3722663672465335.91691659611714.503103286
2465237.69705727611820.0528028632465168.79655893611884.555397049
#Sta/Elev= 30
       0  2363.9     6.1 2362.21    33.3 2351.72    52.7 2345.05   106.6 2324.83
   126.7 2316.44   137.1 2315.04  139.692313.739   147.6 2308.99   180.4  2294.3
     200  2284.2   230.7 2266.03   255.8 2249.23   263.5 2244.76   268.9 2242.18
   274.4 2240.44  293.032237.217     305 2234.99   308.6 2235.24  316.682237.216
   333.3 2237.81     340 2238.87   344.7 2240.93   356.3 2249.02   361.8 2251.11
   378.4 2251.14   400.3 2248.62   411.3    2251   444.1 2252.52   463.2 2255.23
#Mann= 4 ,-1 , 0
       0      .1       0  139.69      .1       0  293.03    .045       0
  316.68     .06       0
Bank Sta=293.03,316.68
XS Rating Curve= 0 ,0
Exp/Cntr(USF)=0,0
Exp/Cntr=0.3,0.1

Type RM Length L Ch R = 1 ,24750   ,164.4,163,162
XS GIS Cut Line= 4
2465287.53997095611421.3094933492465157.06881453611582.565978815
  2465082.304444611692.5135825412465013.40394566611805.393122366
#Sta/Elev= 30
       0 2358.49    38.1 2347.79   78.262332.177   110.1 2318.02   156.4  2295.5
   204.8 2266.86  222.172255.832   252.5 2238.92   258.3 2236.41   268.5 2234.13
   281.3 2233.75  291.312231.375   301.5 2229.12   309.4 2229.65  311.672231.374
   318.7 2237.82   321.6 2239.27   335.9  2241.1   341.8 2243.52   347.6 2246.91
  354.972248.102   361.9 2248.12   394.2 2243.43   404.1  2246.9   417.5 2245.28
   426.2 2245.39   441.6 2247.83     451 2250.87  459.62 2254.86   472.6 2261.33
#Mann= 7 ,-1 , 0
       0     .12       0   78.26      .1       0  222.17      .1       0
  291.31    .045       0  311.67    .055       0  354.97     .06       0
  459.62      .1       0
Bank Sta=291.31,311.67
XS Rating Curve= 0 ,0
Exp/Cntr(USF)=0,0
Exp/Cntr=0.3,0.1

Type RM Length L Ch R = 1 ,24587   ,139,127.2,120.8
XS GIS Cut Line= 4
2465148.27300623611309.8959215732465016.33588176611488.744023635
2464948.90135148 611604.555499562464900.52440584611736.492624031
#Sta/Elev= 30
       0 2321.86    7.462320.876      41 2315.03    81.9 2305.43   104.8  2299.4
   130.6 2290.95   190.6 2265.85   248.4 2233.07   261.8 2229.71  295.412228.135
   312.7 2226.12   321.9 2226.89  326.212228.136   336.1 2236.17   340.4 2237.97
   354.3 2238.19     363 2239.52  380.252239.706   387.8 2241.22   397.1 2246.64
   401.4 2247.53   422.7 2243.56     444 2243.31   473.8    2239     478  2239.3
   482.3 2241.46   486.6 2246.53  491.722257.232   495.1 2264.67   496.8 2266.24
#Mann= 6 ,-1 , 0
       0     .12       0    7.46      .1       0  295.41    .045       0
  326.21      .1       0  380.25    .055       0  491.72      .1       0
Bank Sta=295.41,326.21
XS Rating Curve= 0 ,0
Exp/Cntr(USF)=0,0
Exp/Cntr=0.3,0.1

Type RM Length L Ch R = 1 ,24460   ,165.4,157.3,156.7
XS GIS Cut Line= 4
2464740.73388842611224.869774692 2464843.3516519611447.696918244
2464871.20504484611594.2937232122464885.86472534611736.492624031
#Sta/Elev= 30
       0 2378.62    15.4 2369.46    30.2 2362.65   39.512356.592    90.3  2321.5
   148.2 2289.88   162.8 2283.67     184 2277.63   226.8 2260.63   260.8 2249.24
   281.1 2236.96   289.3 2235.26   293.4 2231.64   297.4  2226.2  299.782225.022
   305.4 2223.65   317.8 2223.01  327.392225.024   334.1 2226.48   370.7 2225.22
   375.8 2226.34   391.1 2233.81   403.2  2234.1  437.65 2239.18   487.6 2242.31
   519.8 2237.97   523.8 2239.03   527.8 2244.79  535.312260.474   537.5 2262.96
#Mann= 6 ,-1 , 0
       0      .1       0   39.51      .1       0  299.78    .045       0
  327.39      .1       0  437.65    .055       0  535.31      .1       0
Bank Sta=299.78,327.39
XS Rating Curve= 0 ,0
Exp/Cntr(USF)=0,0
Exp/Cntr=0.3,0.1

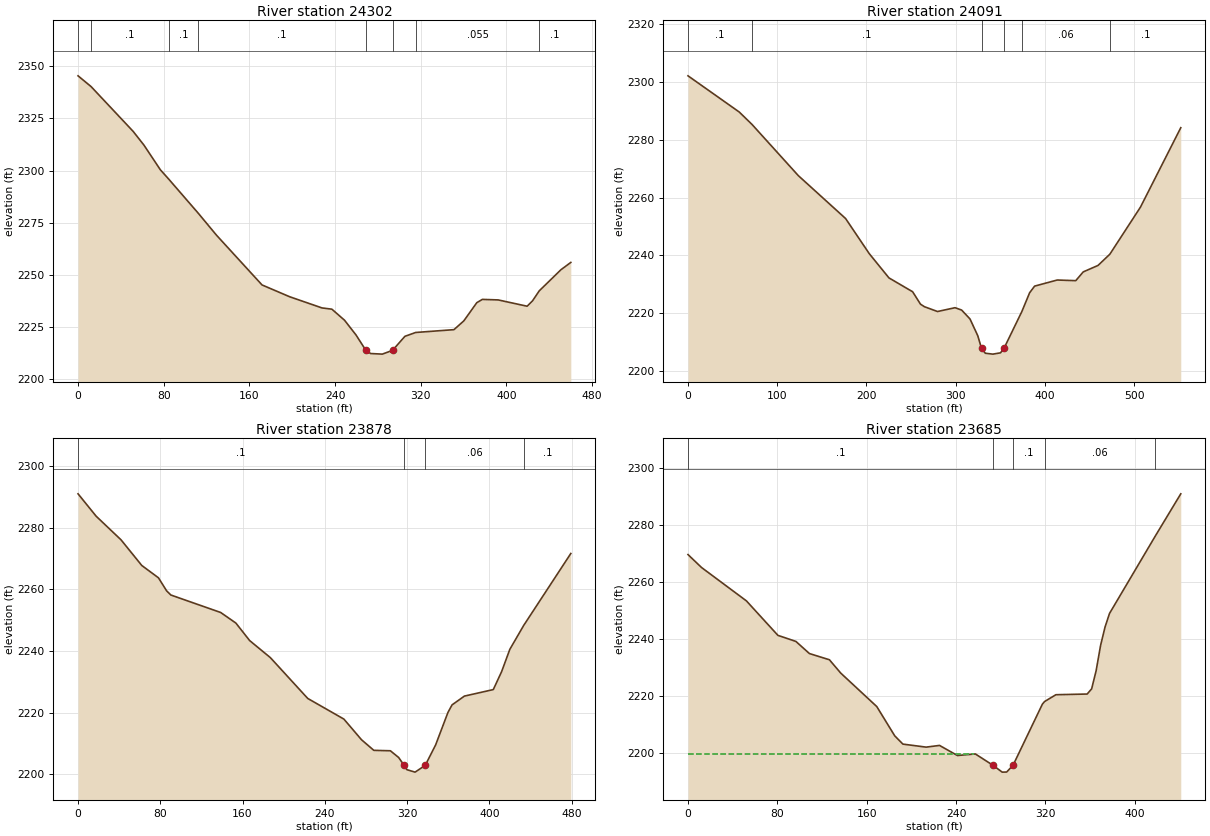
Type RM Length L Ch R = 1 ,24302   ,207.9,211.1,211.9
XS GIS Cut Line= 4
 2464630.7862847611367.0686755112464715.81243158611582.565978815
2464761.25744112611664.6601895972464827.22600335611781.937633571
#Sta/Elev= 30
       0 2345.42   12.182340.252    51.4  2318.8    61.5 2312.21    76.9 2300.32
   84.592295.916  112.162279.562   129.3 2268.96   171.8 2245.11   197.6 2239.45
   227.7  2234.1     237 2233.49   248.8  2228.2   259.5 2221.15  268.762213.736
   273.2 2212.22   284.1 2211.93  293.66 2213.74   305.2 2220.47  315.262222.316
     351 2223.67   360.2 2227.88   372.3  2236.6   377.5 2238.18   392.3 2237.93
   419.3 2234.91   424.4 2237.52  430.622242.284   450.9 2252.42   460.1 2255.92
#Mann= 8 ,-1 , 0
       0      .1       0   12.18      .1       0   84.59      .1       0
  112.16      .1       0  268.76    .045       0  293.66      .1       0
  315.26    .055       0  430.62      .1       0
Bank Sta=268.76,293.66
XS Rating Curve= 0 ,0
Exp/Cntr(USF)=0,0
Exp/Cntr=0.3,0.1

Type RM Length L Ch R = 1 ,24091   ,208.9,213,215.6
XS GIS Cut Line= 4
2464432.88059799611438.9011099452464548.69207391611686.649710342
 2464592.6711154611809.791026515 2464633.7182208611951.989927335
#Sta/Elev= 30
       0 2302.12    57.4 2289.61   71.662285.333   123.6 2267.62   176.6 2252.78
   203.1 2240.64   225.2 2232.25   251.7 2227.47   260.5 2223.18   264.9  2222.3
   279.6 2220.63   299.2 2221.95   306.6 2221.14     316 2218.06   324.7 2212.28
  328.952207.856   333.2  2206.2   341.7  2205.9   350.2 2206.35  354.022207.851
  374.092220.609   382.8  2227.1   388.4 2229.41   413.7 2231.52   434.5  2231.3
   442.9 2234.33   459.5 2236.57  472.712240.444     507 2256.71   552.2 2284.18
#Mann= 6 ,-1 , 0
       0      .1       0   71.66      .1       0  328.95    .045       0
  354.02      .1       0  374.09     .06       0  472.71      .1       0
Bank Sta=328.95,354.02
XS Rating Curve= 0 ,0
Exp/Cntr(USF)=0,0
Exp/Cntr=0.3,0.1

Type RM Length L Ch R = 1 ,23878   ,191.9,193.1,193.7
XS GIS Cut Line= 4
2464331.72880256611481.414183386 2464365.4460677611733.560687932
2464369.84397185611858.167972155 2464380.1057482611957.853799533
#Sta/Elev= 30
       0 2291.09    17.6 2283.82    41.8 2276.14      62  2267.8    78.2  2263.8
    86.2 2259.54    90.3  2258.2   138.7 2252.53   153.5 2249.09   166.9  2243.4
   187.1 2237.84   223.4 2224.59   258.6 2217.87   275.7 2211.17   287.7 2207.72
   303.8 2207.58   311.8 2205.41  317.162202.842   319.8 2201.44   327.8 2200.64
   337.72202.839   347.8 2209.48   359.8 2220.05   363.8  2222.5   375.8 2225.35
   403.9 2227.47     412 2233.31     420 2240.56  433.462248.315   479.3  2271.7
#Mann= 4 ,-1 , 0
       0      .1       0  317.16    .045       0   337.7     .06       0
  433.46      .1       0
Bank Sta=317.16,337.7
XS Rating Curve= 0 ,0
Exp/Cntr(USF)=0,0
Exp/Cntr=0.3,0.1

Type RM Length L Ch R = 1 ,23685   ,148.9,150.2,150.9
XS GIS Cut Line= 4
2464202.72361419611526.8591929262464182.20006149611714.503103286
 2464173.4042532611866.963780453 2464170.4723171611966.649607831
#Sta/Elev= 30
       0  2269.6    12.1 2265.08    52.3 2253.39    80.5 2241.32    96.6  2239.2
   108.7 2234.95   126.6 2232.78   136.8 2228.09     169  2216.4   185.1 2206.14
   192.4 2203.25   213.2 2202.19   225.2 2202.79   241.2 2199.26   257.3  2199.8
  273.052195.834   281.3 2193.44   285.3 2193.47  291.022195.835   317.3 2217.24
  319.212218.141   329.4 2220.54   357.4 2220.78   361.4  2222.6   365.4 2228.92
   369.4 2237.81   373.4 2244.25   377.4 2248.99  418.532276.185   441.2 2290.87
#Mann= 5 ,-1 , 0
       0      .1       0  273.05    .045       0  291.02      .1       0
  319.21     .06       0  418.53     .12       0
#XS Ineff= 2 , 0
          256.47 2199.81
Permanent Ineff=
       F       F
Bank Sta=273.05,291.02
XS Rating Curve= 0 ,0
Exp/Cntr(USF)=0,0
Exp/Cntr=0.3,0.1