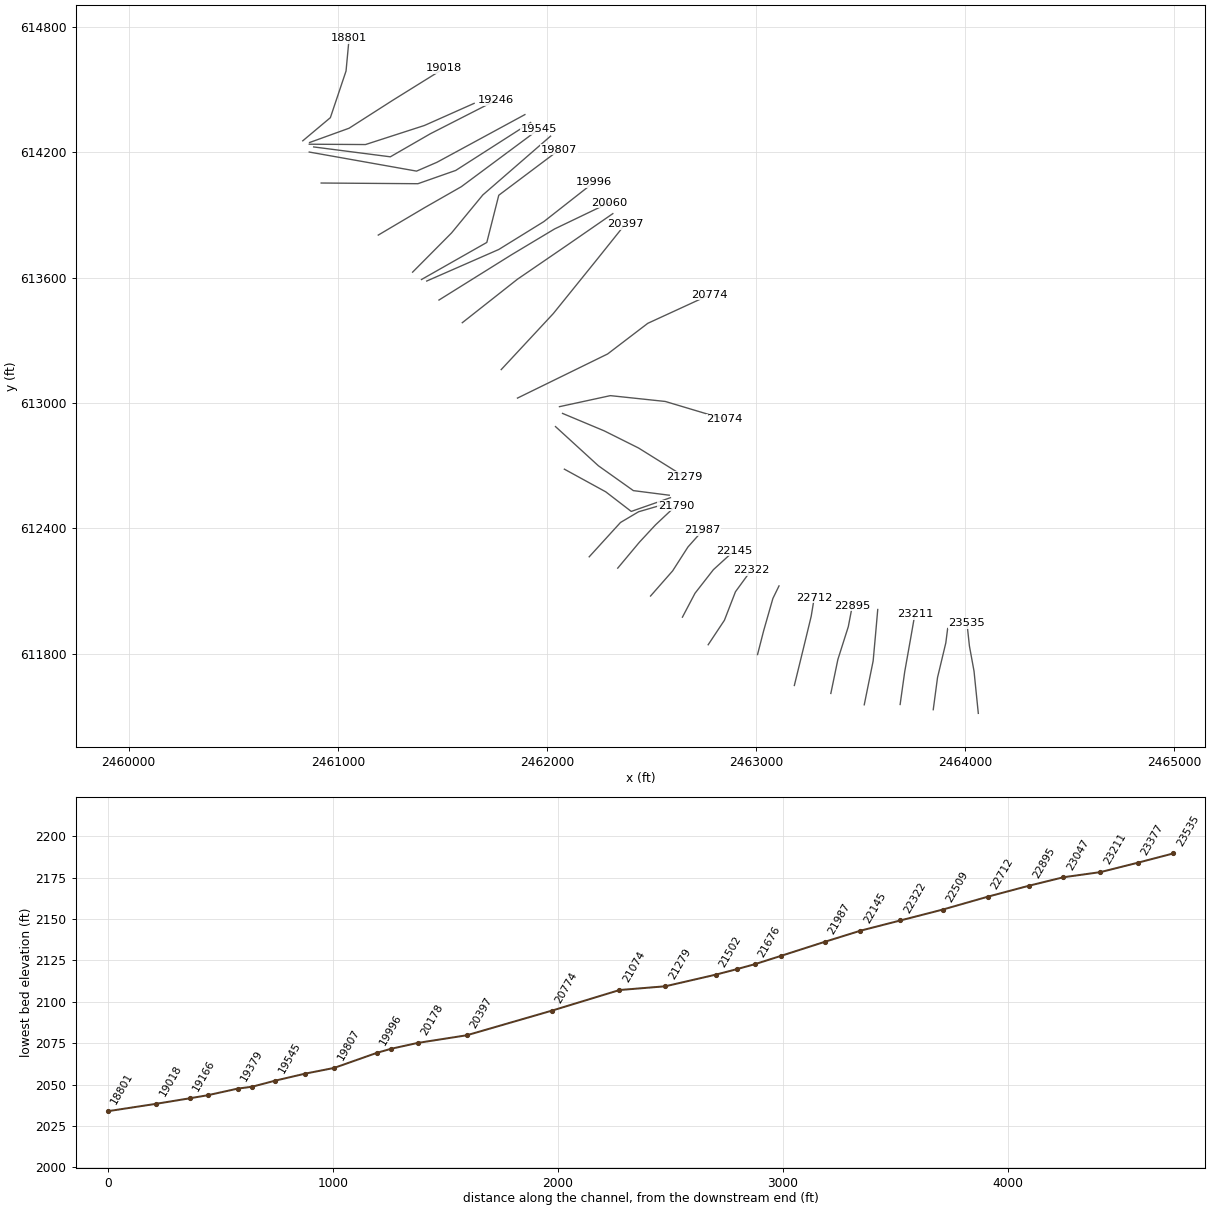
HEC-RAS study TROUTRN.prj: TROUTRN

--- TROUTRN.g01 (geometry) --- (continued)

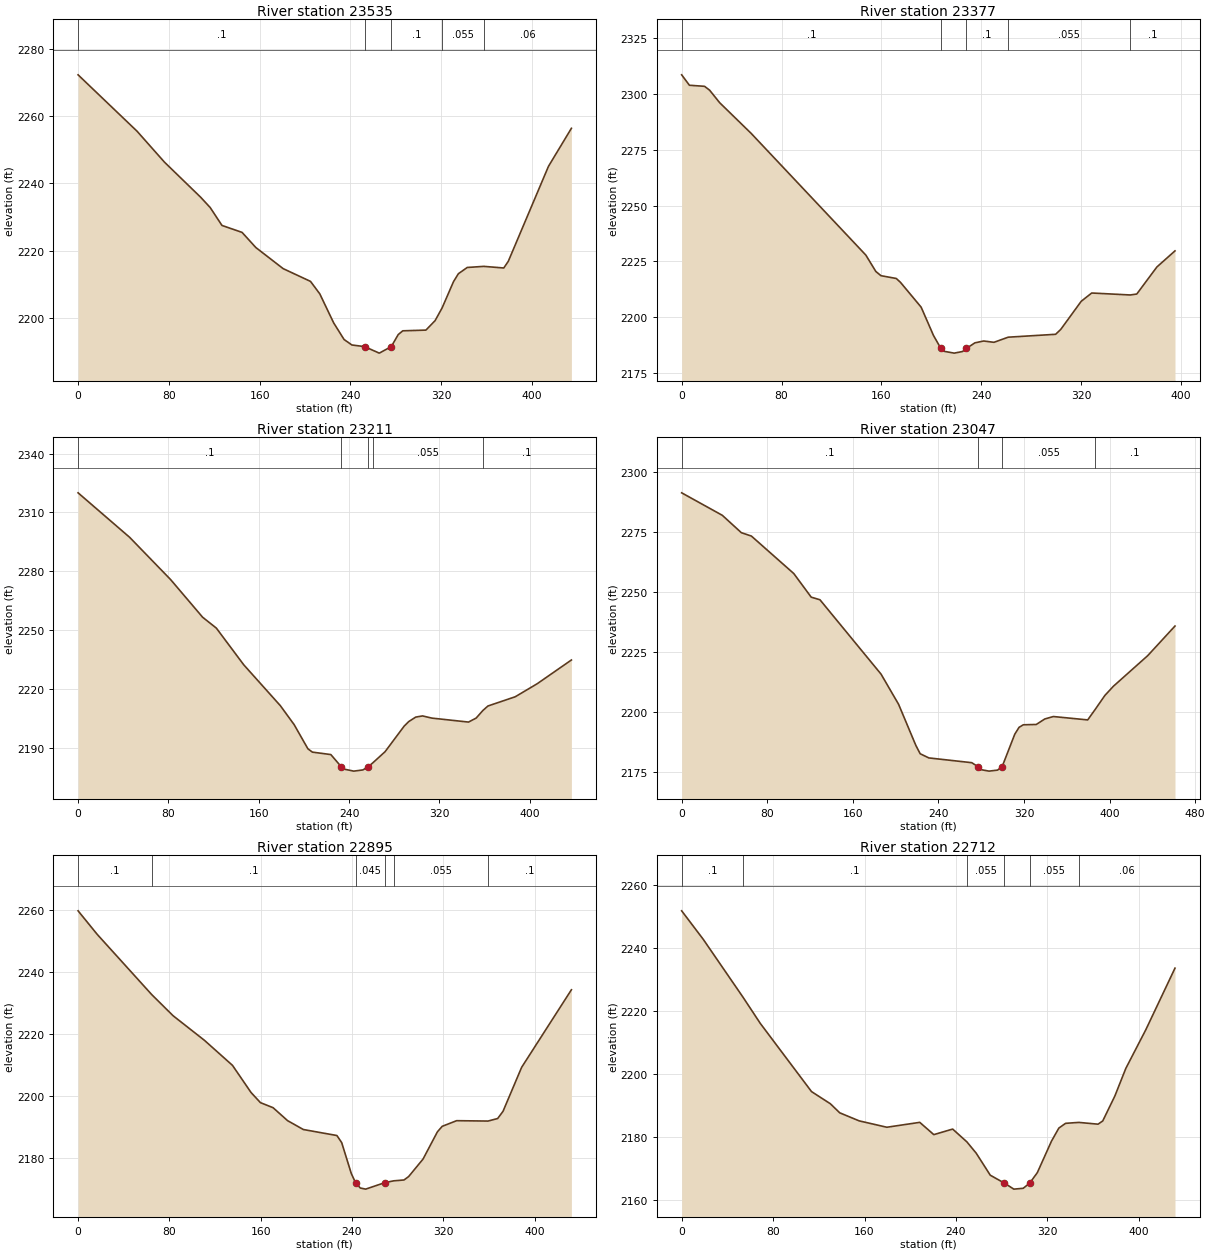
Type RM Length L Ch R = 1 ,23535   ,163,158.4,155.5
XS GIS Cut Line= 4
2464061.99068142611515.1314485292464041.46712872611717.435039385
2464019.47760798611837.6444194592464007.74986358611946.126055136
#Sta/Elev= 30
       0 2272.29      52 2255.52    76.1 2246.35     108 2235.92   116.4 2232.86
   126.8 2227.53   144.5 2225.47   156.6 2220.98   180.7  2214.7   204.8 2210.91
     213  2207.2   225.2 2198.59   234.4 2193.63   241.3 2192.01   252.42191.529
   265.4 2189.59  275.992191.528   282.1  2195.1   286.1 2196.22   306.5 2196.43
   314.6 2199.25  320.822203.059   330.8 2210.82   335.1 2213.18   342.9 2215.04
  357.462215.373   375.1 2214.89   379.1 2216.88   414.5  2245.1   434.7  2256.4
#Mann= 5 ,-1 , 0
       0      .1       0   252.4    .045       0  275.99      .1       0
  320.82    .055       0  357.46     .06       0
Bank Sta=252.4,275.99
XS Rating Curve= 0 ,0
Exp/Cntr(USF)=0,0
Exp/Cntr=0.3,0.1

Type RM Length L Ch R = 1 ,23377   ,164.7,165.6,166.2
XS GIS Cut Line= 4
2463846.49337812611532.7230651252463867.01693081611686.649710342
2463906.59806815611852.3040999562463915.39387645611921.204598291
#Sta/Elev= 30
       0 2308.54     6.2 2303.87    18.3  2303.4    22.4 2301.66    30.4 2296.08
    55.6 2282.36   147.5 2227.85   155.5 2220.52   159.6 2218.63   171.9 2217.37
   175.2 2215.67   191.8 2204.53   201.7 2191.85  207.612186.044     210 2184.79
   218.3 2183.96     225 2184.69  227.922186.044   234.9 2188.57   241.9 2189.39
   250.1  2188.8  261.532191.095   299.5 2192.39   303.6 2194.57     320 2207.16
   328.4 2210.87  359.282209.993   364.5 2210.42   380.6 2222.52   395.1 2229.73
#Mann= 5 ,-1 , 0
       0      .1       0  207.61    .045       0  227.92      .1       0
  261.53    .055       0  359.28      .1       0
Bank Sta=207.61,227.92
XS Rating Curve= 0 ,0
Exp/Cntr(USF)=0,0
Exp/Cntr=0.3,0.1

Type RM Length L Ch R = 1 ,23211   ,163.6,164.4,165.6
XS GIS Cut Line= 4
2463688.16882875 611557.64452197 2463710.1583495611714.503103286
2463738.01174244611871.3616846022463758.53529514611988.639128577
#Sta/Elev= 30
       0 2320.01    45.7 2297.33      82 2275.79   110.3 2256.65   122.4 2251.14
   146.7 2232.43   179.1 2211.62   191.3 2201.98   203.5 2189.66   207.5 2187.97
   223.8 2186.73  233.072180.506     236 2179.27   244.1  2178.3   252.2 2178.91
  256.762180.508  260.862182.463   271.8 2188.18   288.8 2201.27   292.9 2203.58
     299 2205.82     305 2206.41   313.2  2205.3   345.7 2203.28   352.5 2205.33
  358.422209.176   362.9 2211.46   387.1 2216.17   406.6 2222.83   436.8 2234.89
#Mann= 5 ,-1 , 0
       0      .1       0  233.07    .045       0  256.76      .1       0
  260.86    .055       0  358.42      .1       0
Bank Sta=233.07,256.76
XS Rating Curve= 0 ,0
Exp/Cntr(USF)=0,0
Exp/Cntr=0.3,0.1

Type RM Length L Ch R = 1 ,23047   ,153.7,151.8,147.8
XS GIS Cut Line= 4
2463516.65056694 611556.178553922463559.16364038611765.811985025
2463570.89138478611894.8171733972463581.15316112612012.094617371
#Sta/Elev= 30
       0 2291.16      38 2281.79    55.8 2274.55    65.2 2273.14   104.8 2257.53
   121.1 2247.69   129.3 2246.59   186.4 2215.61   202.8 2203.04     219 2185.84
     223 2182.43   231.1 2180.69   271.2 2178.71  276.872177.084   279.2 2175.86
   287.3 2175.19   295.3 2175.61  299.642177.089   311.4 2190.56   315.4 2193.43
   319.4  2194.5   331.5 2194.63   339.5 2196.93   347.5 2197.94   379.6 2196.53
  386.712200.978   395.7 2206.75   403.7 2210.59   435.7 2223.31   461.2 2235.65
#Mann= 4 ,-1 , 0
       0      .1       0  276.87    .045       0  299.64    .055       0
  386.71      .1       0
Bank Sta=276.87,299.64
XS Rating Curve= 0 ,0
Exp/Cntr(USF)=0,0
Exp/Cntr=0.3,0.1

Type RM Length L Ch R = 1 ,22895   ,182,183.3,183.2
XS GIS Cut Line= 4
2463356.86004952611610.4193717582463390.57731467611773.141825273
2463440.42022835611930.000406589  2463459.477813612029.686233968
#Sta/Elev= 30
       0 2259.58    16.8    2252   64.532232.657    83.2 2225.88   110.8 2217.93
   135.3 2209.91   151.6 2201.17   159.8 2197.92   170.9 2196.29   183.6 2192.13
   197.4 2189.28   226.8 2187.35     231 2185.08   239.4 2175.16  243.132172.179
   247.3 2170.48     252 2170.12  268.61 2172.18  276.532172.783   285.6 2173.06
   289.7 2174.17   302.3 2179.79   314.9 2188.55   319.1 2190.31   331.7 2192.12
  359.21    2192   367.7 2192.82   372.4 2195.15   388.7 2209.28   432.3  2234.2
#Mann= 6 ,-1 , 0
       0      .1       0   64.53      .1       0  243.13    .045       0
  268.61     .06       0  276.53    .055       0  359.21      .1       0
Bank Sta=243.13,268.61
XS Rating Curve= 0 ,0
Exp/Cntr(USF)=0,0
Exp/Cntr=0.3,0.1

Type RM Length L Ch R = 1 ,22712   ,202.5,202.1,201.5
XS GIS Cut Line= 4
2463182.40985161 611648.53454105 2463229.3208292611840.576355559
2463263.03809434611979.8433202782463277.69777484612069.267371309
#Sta/Elev= 30
       0 2251.67    18.9 2242.63   53.762224.246    68.8 2215.99   113.6 2194.39
   130.1 2190.53   138.3 2187.66   155.3 2185.11   179.5 2183.09   208.3 2184.64
   220.6 2180.75   237.1 2182.51  249.532178.456   257.7 2174.87     270 2167.89
  282.142165.431   290.6 2163.48   298.8 2163.74  304.622165.429   311.2 2168.73
   323.5 2178.65     330 2182.83   335.9 2184.33  347.382184.624   364.3 2184.06
   368.4 2185.09     379 2192.99   388.6 2201.75   406.1    2214   431.6  2233.5
#Mann= 6 ,-1 , 0
       0      .1       0   53.76      .1       0  249.53    .055       0
  282.14    .045       0  304.62    .055       0  347.38     .06       0
Bank Sta=282.14,304.62
XS Rating Curve= 0 ,0
Exp/Cntr(USF)=0,0
Exp/Cntr=0.3,0.1

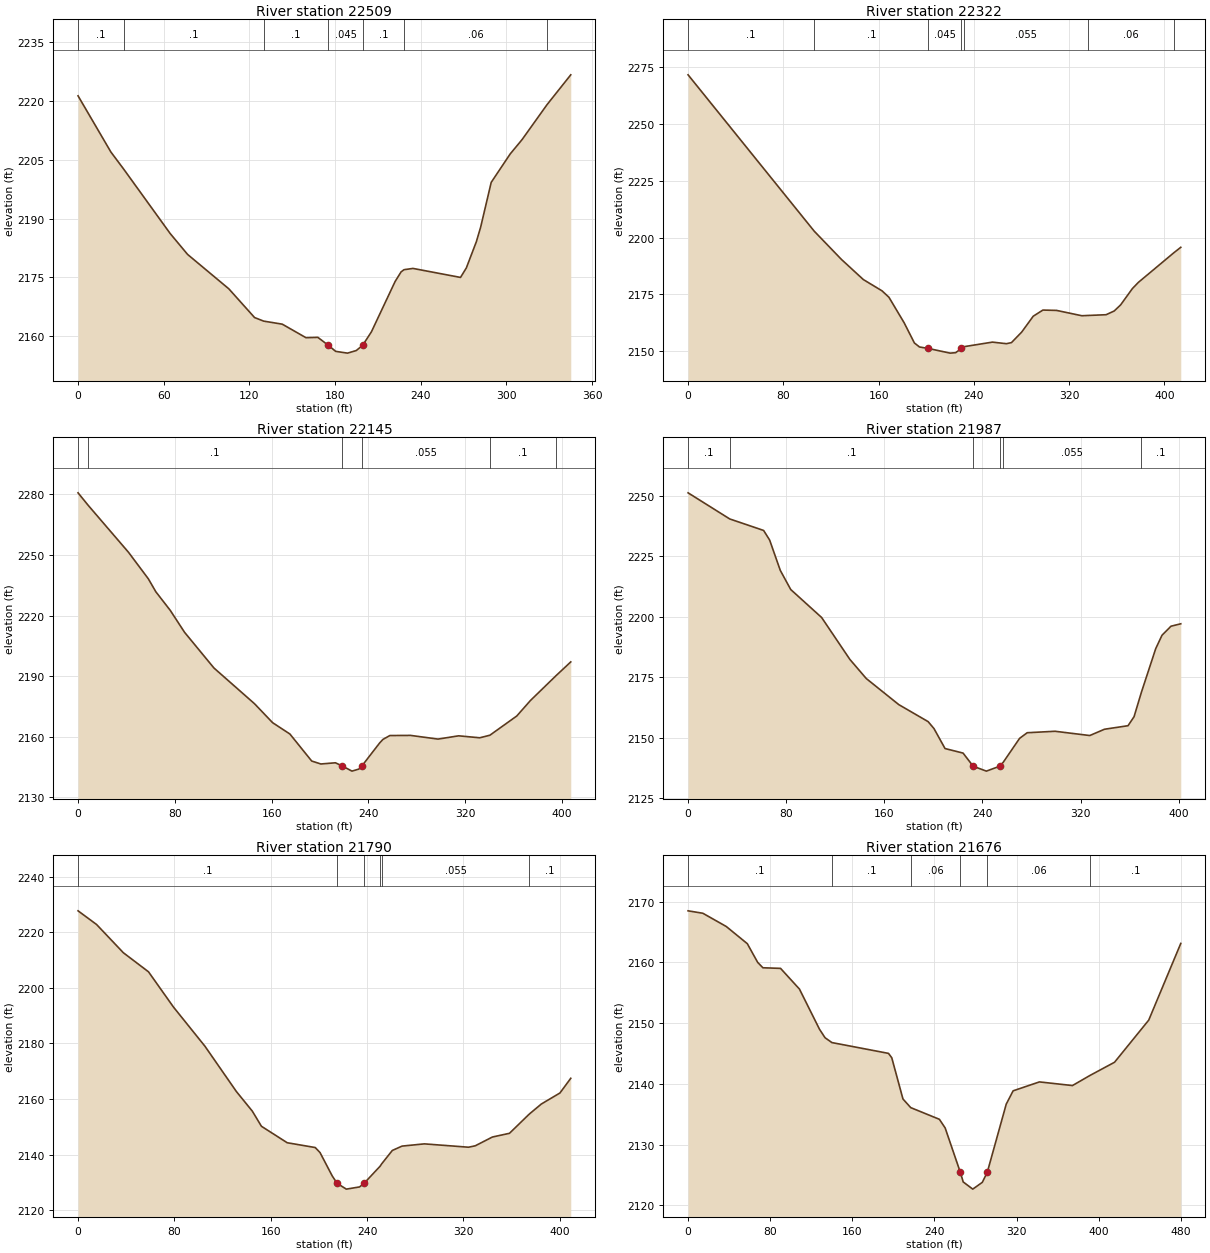
Type RM Length L Ch R = 1 ,22509   ,189,187.5,186.5
XS GIS Cut Line= 4
2463006.49368565611796.5973140682463035.81304664611910.942821943
2463079.79208813 612064.869467162463109.11144913612124.974157197
#Sta/Elev= 30
       0 2221.36      23 2207.01   31.93 2202.65    64.5 2186.19    76.7 2180.85
   105.6 2172.05   123.6 2164.72  129.962163.807     143 2163.03   159.6 2159.57
   167.9 2159.66  175.352157.601   180.4 2156.08   188.7 2155.63   194.8 2156.29
  199.242157.602   205.4 2161.06     222 2173.92   226.2 2176.39  228.252176.945
   234.5 2177.27   267.8 2174.97   271.9 2177.41   278.9  2184.1   281.9 2187.81
   289.3 2199.26   302.6 2206.52   310.9 2210.18  328.412219.123     345 2226.73
#Mann= 7 ,-1 , 0
       0      .1       0   31.93      .1       0  129.96      .1       0
  175.35    .045       0  199.24      .1       0  228.25     .06       0
  328.41      .1       0
Bank Sta=175.35,199.24
XS Rating Curve= 0 ,0
Exp/Cntr(USF)=0,0
Exp/Cntr=0.3,0.1

Type RM Length L Ch R = 1 ,22322   ,184.8,176.9,173.4
XS GIS Cut Line= 4
2462770.47282965611843.5082916582462848.16913628611960.785735633
2462900.94398607612097.120764253 2462975.7083566612199.738527731
#Sta/Elev= 30
       0 2271.76  105.97 2202.83   128.8 2190.39   147.2 2181.51   162.9 2176.54
   168.7 2173.71   181.5 2162.43   190.1 2153.54   194.4 2151.78  201.882151.126
   220.1 2149.08   224.7 2149.27  229.552151.126  231.682151.918   255.6 2153.93
   267.3 2153.24   271.6 2153.71   280.2 2158.36   289.9 2165.36     298 2168.06
   309.5 2167.91   330.7 2165.56  335.932165.681   351.1 2166.01   357.9 2167.66
   363.3 2170.36   373.2 2177.55   378.2 2180.27  408.022193.343   413.8 2195.73
#Mann= 7 ,-1 , 0
       0      .1       0  105.97      .1       0  201.88    .045       0
  229.55      .1       0  231.68    .055       0  335.93     .06       0
  408.02      .1       0
Bank Sta=201.88,229.55
XS Rating Curve= 0 ,0
Exp/Cntr(USF)=0,0
Exp/Cntr=0.3,0.1

Type RM Length L Ch R = 1 ,22145   ,157,158.2,159.1
XS GIS Cut Line= 4
2462647.33151348611975.4454161292462707.43620351612089.790924005
2462795.39428649 612202.670463832462895.08011387612293.560482911
#Sta/Elev= 30
       0 2280.79    8.142274.767    41.7 2251.33    58.1 2238.18    64.3 2231.76
    76.2 2222.56      88 2211.71   112.3 2194.01   145.8 2176.33   160.8 2166.91
   175.1 2161.29   193.1 2147.91   200.7 2146.45   212.7 2147.04  218.322145.473
   226.4 2142.91     232 2143.91  234.592145.478   249.2 2156.82     252 2158.64
   257.7 2160.54   274.8 2160.61   297.5 2158.78   314.5  2160.4     332 2159.43
  340.362160.698   362.6 2170.23   373.9 2177.91  395.382190.403   407.2 2197.02
#Mann= 6 ,-1 , 0
       0      .1       0    8.14      .1       0  218.32    .045       0
  234.59    .055       0  340.36      .1       0  395.38      .1       0
Bank Sta=218.32,234.59
XS Rating Curve= 0 ,0
Exp/Cntr(USF)=0,0
Exp/Cntr=0.3,0.1

Type RM Length L Ch R = 1 ,21987   ,198.7,196.7,194.8
XS GIS Cut Line= 4
2462494.87083631612076.5972115582462600.42053589612196.806591632
2462673.71893837612311.1520995072462744.08540475 612390.31437419
#Sta/Elev= 30
       0 2251.16   33.992240.368    61.6 2235.62    66.5 2231.66    75.2 2219.11
    83.7 2211.22   108.9 2199.66   131.9 2182.37   145.3 2174.45   171.8 2163.68
   195.7 2156.66   200.5 2153.78   209.5 2145.54   224.2 2143.66  232.432138.246
   243.2 2136.21  254.142138.245  257.01 2139.91   270.3 2149.75   276.5 2152.07
   299.2 2152.67   327.5 2150.91   339.5 2153.51   358.7 2154.97   363.6 2158.68
  369.622168.822   381.3 2186.84   386.4 2192.33   393.7 2196.06   401.7 2197.07
#Mann= 6 ,-1 , 0
       0      .1       0   33.99      .1       0  232.43    .045       0
  254.14      .1       0  257.01    .055       0  369.62      .1       0
Bank Sta=232.43,254.14
XS Rating Curve= 0 ,0
Exp/Cntr(USF)=0,0
Exp/Cntr=0.3,0.1

Type RM Length L Ch R = 1 ,21790   ,118.6,114.6,111
XS GIS Cut Line= 4
2462338.01225499612210.0003040792462442.09598652612334.607588302
 2462518.3263251612416.7017990842462616.54618443612509.057786214
#Sta/Elev= 30
       0 2227.68    15.4 2222.76    37.6 2212.62    58.5 2205.76    79.3 2193.05
   105.4 2178.99   131.5 2162.71   144.7 2155.68   152.3 2150.22   173.7  2144.3
     197 2142.57     201 2140.74   211.1 2132.36  215.21 2129.69   222.8 2127.62
   233.8 2128.41   237.52129.687  250.94  2135.9  252.182136.718     261 2141.52
   269.1 2143.09   287.6 2143.89   324.3 2142.69   329.9  2143.2   344.1 2146.35
   358.3 2147.69  374.72 2154.59   384.8 2158.23   400.2 2162.18   409.2 2167.47
#Mann= 6 ,-1 , 0
       0      .1       0  215.21    .045       0   237.5      .1       0
  250.94     .06       0  252.18    .055       0  374.72      .1       0
Bank Sta=215.21,237.5
XS Rating Curve= 0 ,0
Exp/Cntr(USF)=0,0
Exp/Cntr=0.3,0.1

Type RM Length L Ch R = 1 ,21676   ,108.3,79.4,68.2
XS GIS Cut Line= 4
2462201.67722637612264.2411219172462351.20596744612428.429543481
2462437.69808237 612479.738425222462588.69279149612523.717466711
#Sta/Elev= 30
       0 2168.51    14.4 2168.11    37.2 2165.93    57.7  2163.1    67.8 2160.02
    72.9 2159.13    90.1 2159.03   108.5 2155.62     128 2149.01   133.4 2147.61
  140.09 2146.81   195.2 2145.03   198.4 2144.31   209.3 2137.52  216.872136.095
   244.8 2134.17   250.4 2132.75  265.122125.467     268 2123.85   277.3 2122.67
   286.6 2123.79  291.472125.467   309.9 2136.67   316.6 2138.86   342.2 2140.33
   374.4 2139.73  391.612141.408   415.4 2143.57   448.7 2150.51   479.9 2163.14
#Mann= 6 ,-1 , 0
       0      .1       0  140.09      .1       0  216.87     .06       0
  265.12    .045       0  291.47     .06       0  391.61      .1       0
Bank Sta=265.12,291.47
XS Rating Curve= 0 ,0
Exp/Cntr(USF)=0,0
Exp/Cntr=0.5,0.3

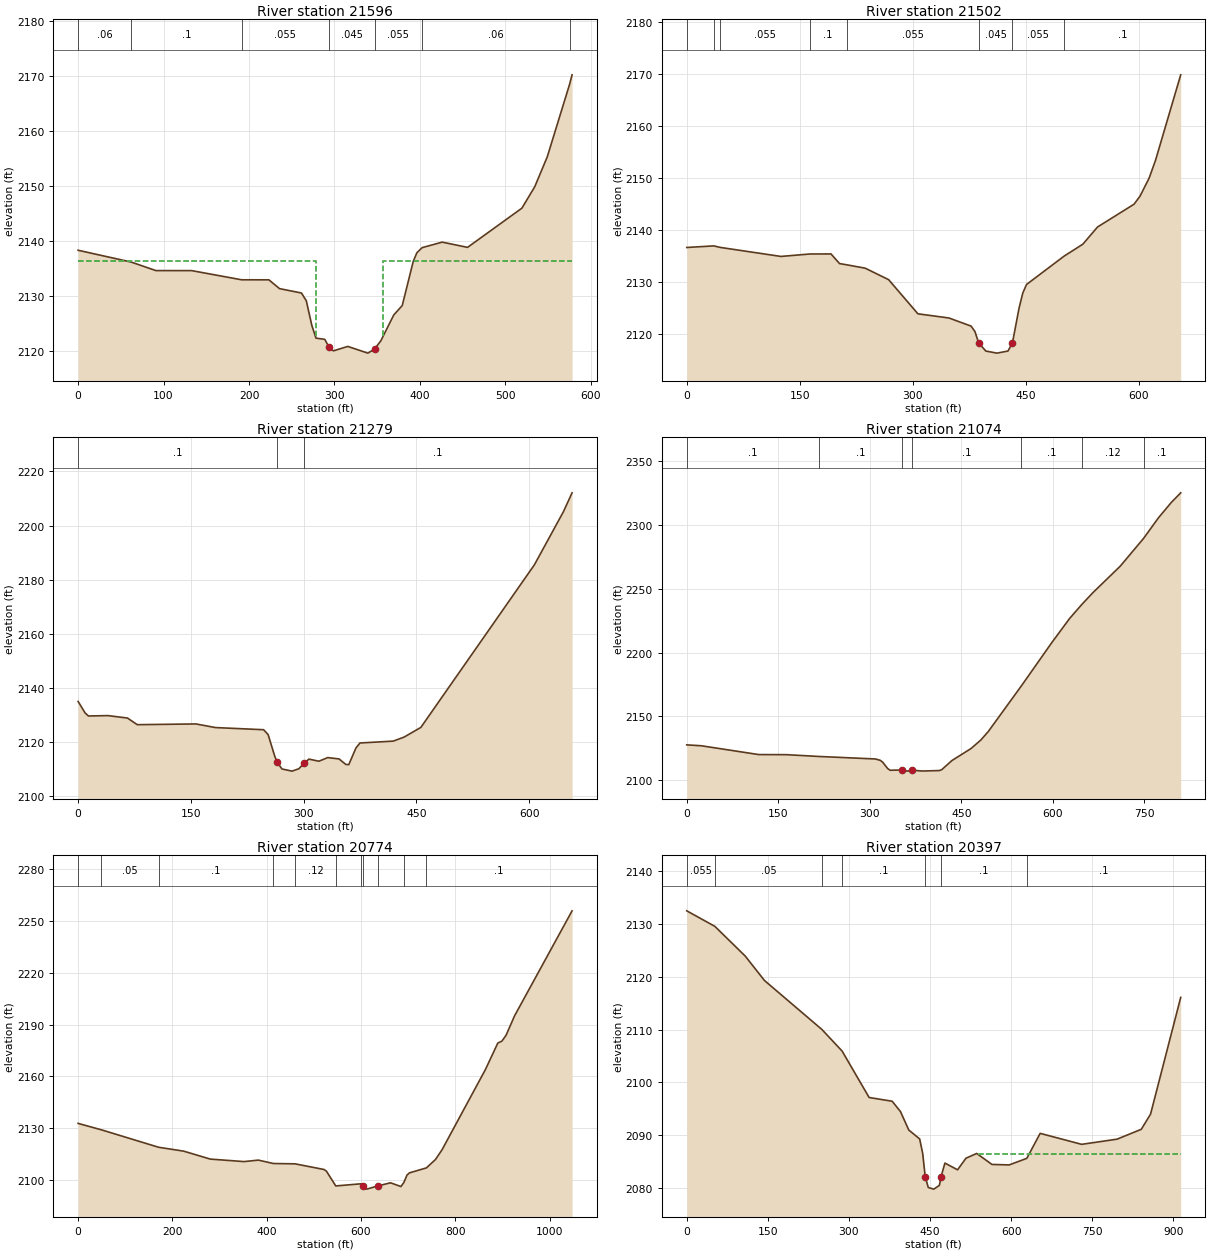
Type RM Length L Ch R = 1 ,21596   ,93,94.3,91.2
XS GIS Cut Line= 4
2462082.93381435612683.5079841262462280.83950106 612575.02634845
2462402.64153402612481.3451542082462590.15875954612547.172955506
#Sta/Elev= 30
       02138.385  62.1912136.234  91.0152134.689 132.9052134.683 191.3692133.016
 223.2992133.007   235.72131.411 261.3722130.615 267.0772129.198 273.5082124.734
 278.398 2122.41 288.6472122.197 293.693 2120.76  298.742120.097 315.5682120.909
  339.112119.688 346.9442120.431 354.2492121.921 369.3872126.621 379.3492128.343
 392.1772136.344 396.416 2137.92 402.6082138.858 426.0922139.861 455.7672138.908
 519.3562146.031 534.3952149.929 549.0322155.353 575.1862168.549 578.0852170.266
#Mann= 7 ,-1 , 0
       0     .06       0  62.191      .1       0 191.369    .055       0
 293.693    .045       0 346.944    .055       0 402.608     .06       0
 575.186      .1       0
#XS Ineff= 2 , 0
          278.12 2136.47  356.81         2136.38
Permanent Ineff=
       F       F
Bank Sta=293.693,346.944
XS Rating Curve= 0 ,0
Exp/Cntr(USF)=0,0
Exp/Cntr=0.5,0.3

Type RM Length L Ch R = 1 ,21502   ,212.8,223.3,223.1
XS GIS Cut Line= 4
2462040.42074091612887.2775430322462245.65626786612699.633632673
2462412.77662553612580.8902206482462584.29488734612558.900699903
#Sta/Elev= 30
       0 2136.63      362136.937    44.82136.636   125.1 2134.91  163.53 2135.38
   191.6 2135.39   202.9 2133.54   212.22133.308   236.9 2132.66   268.1 2130.45
     307 2123.89   348.2 2123.09   377.6 2121.53   382.7  2120.5  387.712118.291
   397.2 2116.74   411.9 2116.34   426.6 2116.74  432.522118.295   441.3 2124.98
   446.3 2127.89   451.2 2129.52  501.262134.981     526 2137.26   545.6 2140.57
     594 2144.94     602  2146.5   614.1 2149.97   622.5 2153.36     656 2169.79
#Mann= 8 ,-1 , 0
       0      .1       0      36     .06       0    44.8    .055       0
  163.53      .1       0   212.2    .055       0  387.71    .045       0
  432.52    .055       0  501.26      .1       0
Bank Sta=387.71,432.52
XS Rating Curve= 0 ,0
Exp/Cntr(USF)=0,0
Exp/Cntr=0.5,0.3

Type RM Length L Ch R = 1 ,21279   ,201.1,204,207.8
XS GIS Cut Line= 4
2462074.13800605612950.3141691692462273.50966081612866.753990337
2462437.69808237612784.6597795542462656.12732177612648.324750934
#Sta/Elev= 30
       0 2135.06     9.3 2130.83    13.7  2129.7    39.7 2129.84    65.7 2128.94
    78.7 2126.49   156.8 2126.76   182.8 2125.42   246.8 2124.63   252.8 2122.84
   261.7 2114.77  264.952112.569   271.2 2110.14   284.6 2109.34   293.6  2110.2
   300.5 2112.19     307 2113.78   320.4    2113   332.1 2114.34   347.2 2113.84
   356.2 2111.81   360.1 2111.73   369.6 2117.86     375 2119.73   419.2 2120.42
   433.7  2121.9     456 2125.48   607.1 2185.53   645.7 2205.13   657.2 2212.09
#Mann= 3 ,-1 , 0
       0      .1       0  264.95    .045       0   300.5      .1       0
Bank Sta=264.95,300.5
XS Rating Curve= 0 ,0
Exp/Cntr(USF)=0,0
Exp/Cntr=0.3,0.1

Type RM Length L Ch R = 1 ,21074   ,291.7,300.9,312.3
XS GIS Cut Line= 4
2462059.47832555612982.565466262 2462302.8290218 613035.34031605
2462565.23730269613007.4869231062462849.63510433612922.460776225
#Sta/Elev= 30
       0 2127.65    23.8 2126.96   117.9 2120.05     163 2119.97  217.172118.549
   309.3 2116.59   317.3 2115.52   321.3 2113.99   329.3 2109.11   333.4 2107.72
   353.5 2107.99   361.6 2107.06   369.3  2107.8   385.7 2107.14   413.8  2107.5
   417.9 2108.18   434.8  2115.4   466.1 2124.82   482.2 2131.53   494.3 2138.14
  548.442173.866   598.1 2207.68   627.4  2226.7  648.592238.312   665.6 2246.96
   710.5 2267.79  748.75 2289.56   773.3 2305.81   794.2 2317.76   809.7 2325.35
#Mann= 7 ,-1 , 0
       0      .1       0  217.17      .1       0   353.5    .045       0
   369.3      .1       0  548.44      .1       0  648.59     .12       0
  748.75      .1       0
Bank Sta=353.5,369.3
XS Rating Curve= 0 ,0
Exp/Cntr(USF)=0,0
Exp/Cntr=0.3,0.1

Type RM Length L Ch R = 1 ,20774   ,372.8,377,379.4
XS GIS Cut Line= 4
2461858.64070275613023.6125716532462289.63530935613234.711970807
2462481.67712386613381.308775775 2462777.8026699613517.643804396
#Sta/Elev= 30
       0  2132.7   49.142128.992  170.842118.855   223.8 2116.61   280.3    2112
     352 2110.55   382.2 2111.41  414.242109.442  460.07 2109.25   521.6 2105.97
   526.6    2105  546.412096.436  599.342097.667   603.5 2096.68   612.1 2094.59
   634.9  2096.4   662.5 2098.26   684.6 2096.08  690.862098.502   697.5 2102.77
   702.7 2104.02  738.472106.892   757.9 2111.79   771.8 2117.43   863.6 2163.84
     890 2179.25   898.8 2180.42   907.6 2183.82   925.5 2195.03  1047.5 2255.93
#Mann= 11 ,-1 , 0
       0    .055       0   49.14     .05       0  170.84      .1       0
  414.24      .1       0  460.07     .12       0  546.41      .1       0
  599.34      .1       0   603.5    .045       0   634.9      .1       0
  690.86      .1       0  738.47      .1       0
Bank Sta=603.5,634.9
XS Rating Curve= 0 ,0
Exp/Cntr(USF)=0,0
Exp/Cntr=0.3,0.1

Type RM Length L Ch R = 1 ,20397   ,223.7,218.6,211.5
XS GIS Cut Line= 4
2461780.94439611613159.9476002732462030.15896456613428.219753365
2462232.46255542613678.9002898612462373.19548818613854.816455823
#Sta/Elev= 30
       0  2132.5   51.972129.558   108.1 2123.93   143.7  2119.3  249.962110.012
  287.442105.905   337.3 2097.12   379.9 2096.41   395.3 2094.45   410.7 2090.95
   430.8 2089.26   436.4 2086.51     4412082.141   446.7 2080.06     457 2079.75
   467.3 2080.47   470.4 2082.14   477.5 2084.69   500.9 2083.41   516.4 2085.61
   536.3 2086.51   564.5 2084.43   596.4 2084.34  628.922085.582   653.7 2090.32
   730.4 2088.24   795.9 2089.22   840.7 2091.09   857.8 2093.96   913.6 2116.09
#Mann= 7 ,-1 , 0
       0    .055       0   51.97     .05       0  249.96     .12       0
  287.44      .1       0     441    .045       0   470.4      .1       0
  628.92      .1       0
#XS Ineff= 2 , 0
                          540.05         2086.46
Permanent Ineff=
       F       F
Bank Sta=441,470.4
XS Rating Curve= 0 ,0
Exp/Cntr(USF)=0,0
Exp/Cntr=0.3,0.1

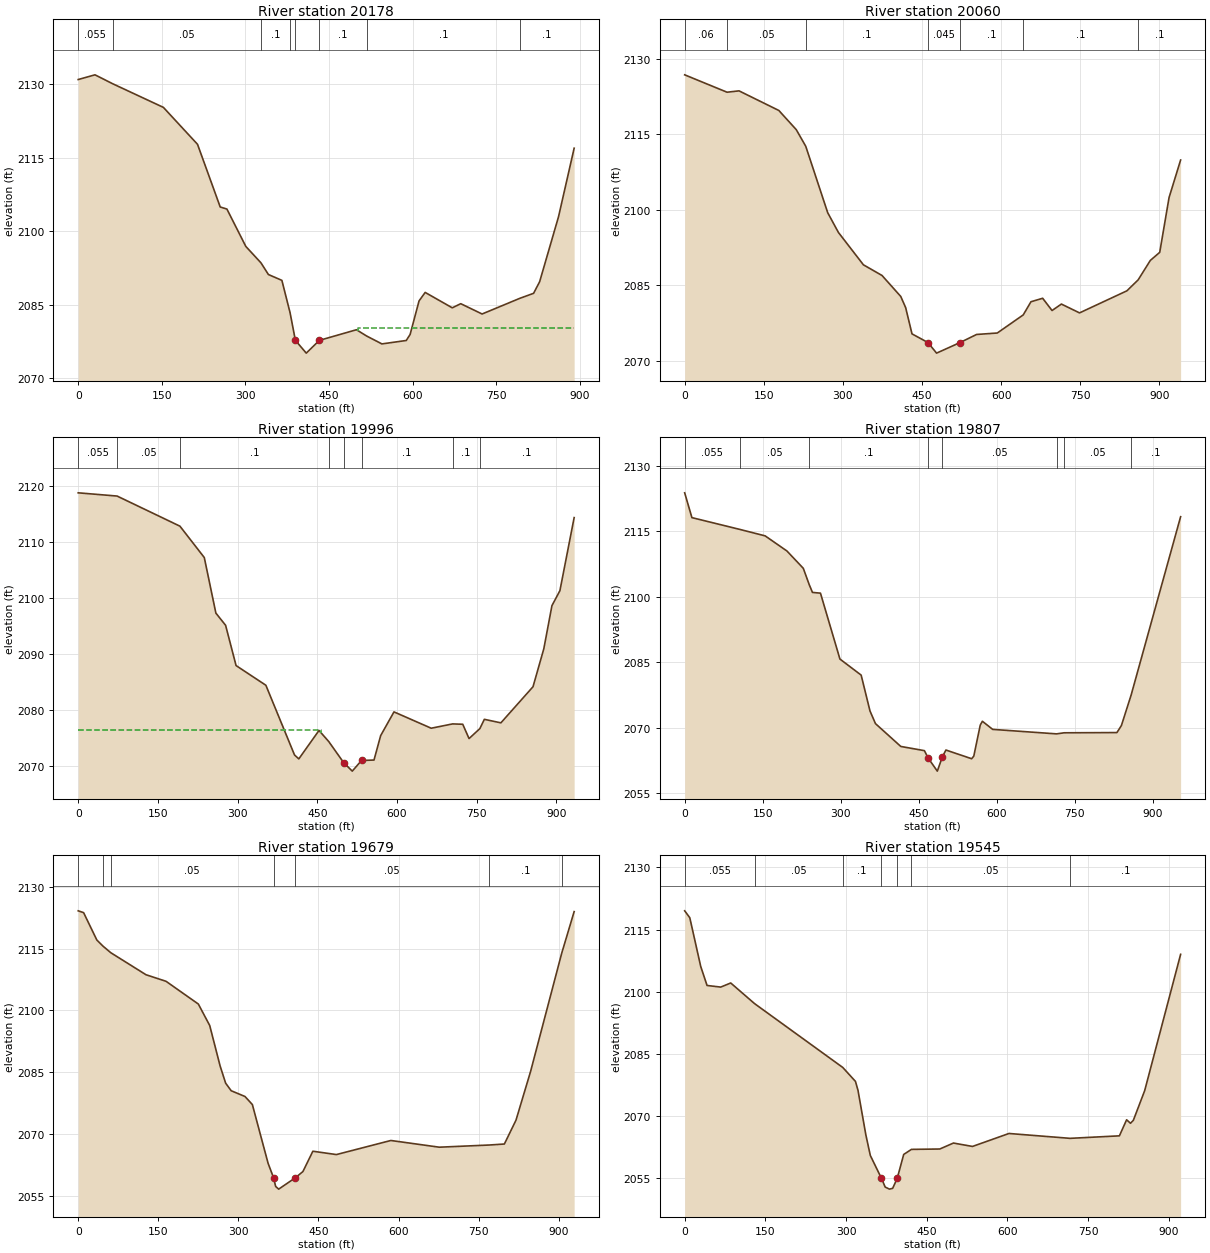
Type RM Length L Ch R = 1 ,20178   ,119.2,118.4,123.1
XS GIS Cut Line= 4
 2461594.7664538613384.2407118752461858.64070275 613592.40817493
2462096.12752679613755.130628445 2462314.5567662613906.125337562
#Sta/Elev= 30
       0  2130.9    30.1 2131.86   61.512130.057   152.8 2125.22     214 2117.69
   254.7 2104.91   266.7 2104.49   300.6 2096.87   327.82093.519   341.1 2091.14
   365.3 2089.95  380.062083.314  389.462077.732     409 2075.11   432.5 2077.71
   499.1 2079.88  517.272078.601   544.7 2076.99   588.4 2077.69   595.3 2078.92
   611.3 2085.75   622.3 2087.49   670.9 2084.35   686.1 2085.19   724.4 2083.09
  792.352086.298   816.8 2087.31   827.6 2089.67   861.5 2102.93   889.5  2116.9
#Mann= 8 ,-1 , 0
       0    .055       0   61.51     .05       0   327.8      .1       0
  380.06      .1       0  389.46    .045       0   432.5      .1       0
  517.27      .1       0  792.35      .1       0
#XS Ineff= 2 , 0
                          501.37         2080.21
Permanent Ineff=
       F       F
Bank Sta=389.46,432.5
XS Rating Curve= 0 ,0
Exp/Cntr(USF)=0,0
Exp/Cntr=0.5,0.3

Type RM Length L Ch R = 1 ,20060   ,63.4,63.2,55.5
XS GIS Cut Line= 4
2461483.35288203613492.722347551 2461830.7873098613709.685618905
2462036.02283676613832.8269350782462298.43111765613958.900187351
#Sta/Elev= 30
       0 2126.77   80.312123.321     103 2123.59   178.5  2119.7   211.5  2115.9
  229.542112.592   271.1 2099.43   291.4 2095.51   338.8 2089.09   374.1 2086.97
   409.6 2082.81   418.9 2080.59   430.9 2075.39  461.142073.671   477.5 2071.57
  522.06 2073.67   553.3 2075.27   592.6 2075.56  641.792079.154   656.4 2081.76
   678.6 2082.45   696.4 2080.02   714.1  2081.3   748.5 2079.55   838.3 2083.93
  859.562086.094   882.7 2089.96   900.5 2091.56   918.2 2102.43   940.1 2109.87
#Mann= 7 ,-1 , 0
       0     .06       0   80.31     .05       0  229.54      .1       0
  461.14    .045       0  522.06      .1       0  641.79      .1       0
  859.56      .1       0
#XS Ineff= 2 , 0
             441  2073.3     542          2073.3
Permanent Ineff=
       F       F
Bank Sta=461.14,522.06
XS Rating Curve= 0 ,0
Exp/Cntr(USF)=0,0
Exp/Cntr=0.5,0.3

Type RM Length L Ch R = 1 ,19996   ,175.9,189.5,198.4
XS GIS Cut Line= 4
2461424.71416004613583.6123666322461769.21665171613734.607075749
2461984.71395502 613868.010168272462223.66674712 614055.65407863
#Sta/Elev= 30
       0 2118.85   73.212118.272  191.46 2112.89   237.3 2107.28   259.1 2097.35
   277.4 2095.17   297.1 2087.97   353.2 2084.45   407.1 2071.99   415.2 2071.29
   453.2 2076.37  471.732074.364   499.5 2070.63   515.8  2069.1   533.2    2071
   556.7 2071.08   569.2 2075.44   594.3 2079.69   664.4 2076.77  704.572077.539
   723.7 2077.48   735.6 2074.92  755.942076.704   764.4 2078.36   795.5 2077.73
     856 2084.19   876.3 2090.97   891.6 2098.68   906.6 2101.36   933.4 2114.42
#Mann= 8 ,-1 , 0
       0    .055       0   73.21     .05       0  191.46      .1       0
  471.73      .1       0   499.5    .045       0   533.2      .1       0
  704.57      .1       0  755.94      .1       0
#XS Ineff= 2 , 0
          456.99  2076.4
Permanent Ineff=
       F       F
Bank Sta=499.5,533.2
XS Rating Curve= 0 ,0
Exp/Cntr(USF)=0,0
Exp/Cntr=0.5,0.3

Type RM Length L Ch R = 1 ,19807   ,134.1,128,115.3
XS GIS Cut Line= 4
2461399.79270319 613590.942206882461712.04389778613768.324340892
2461769.21665171613994.083420543 2462058.0123575614211.046691896
#Sta/Elev= 30
       0 2123.75    13.9 2118.07  105.852115.377   154.7 2113.89   196.6 2110.42
     228 2106.46  239.432102.702   245.6 2100.94     261 2100.77   298.4 2085.68
   339.2    2082   356.2 2073.78   366.7 2070.89   415.4 2065.66   460.8  2064.7
  467.832063.025   485.6 2060.01   495.2 2063.26   502.1 2064.84   551.6 2062.85
   555.7 2063.46   568.1 2070.55   572.2 2071.43     592 2069.57  714.742068.543
  729.372068.788   830.8 2068.84   839.4 2070.46  858.032077.408   953.2 2118.28
#Mann= 8 ,-1 , 0
       0    .055       0  105.85     .05       0  239.43      .1       0
  467.83    .045       0   495.2     .05       0  714.74      .1       0
  729.37     .05       0  858.03      .1       0
Bank Sta=467.83,495.2
XS Rating Curve= 0 ,0
Exp/Cntr(USF)=0,0
Exp/Cntr=0.3,0.1

Type RM Length L Ch R = 1 ,19679   ,139.3,134.2,128.1
XS GIS Cut Line= 4
2461357.27962975613626.1254400732461543.45757206613813.769350432
2461692.98631313613995.5493885932462016.96525211614277.015254132
#Sta/Elev= 30
       0 2124.15    10.1 2123.71    34.9 2117.06   46.382115.581   61.092113.972
     127 2108.63   164.5 2107.04     225 2101.52   246.3 2096.31   265.8 2086.48
   276.1 2082.32   286.5 2080.47   312.4 2079.07   326.2 2077.11   355.6 2062.87
  365.852059.359   369.8 2057.23   375.5 2056.58  406.932059.357   420.9 2060.85
   439.5 2065.78   483.6 2064.97   585.6 2068.39   676.3 2066.76   769.62067.287
   798.2 2067.53     820 2073.33   847.2  2085.1  905.622113.865   928.9 2123.96
#Mann= 7 ,-1 , 0
       0     .06       0   46.38    .055       0   61.09     .05       0
  365.85    .045       0  406.93     .05       0   769.6      .1       0
  905.62     .12       0
Bank Sta=365.85,406.93
XS Rating Curve= 0 ,0
Exp/Cntr(USF)=0,0
Exp/Cntr=0.3,0.1

Type RM Length L Ch R = 1 ,19545   ,104.3,101.1,100.1
XS GIS Cut Line= 4
2461193.09120819613803.5075740842461415.91835174613935.444698556
2461590.36854965614035.1305259342461961.25846622614310.732519275
#Sta/Elev= 30
       0 2119.53     9.5 2117.87    29.8 2106.11    41.6  2101.5      67 2101.11
    85.6  2102.1  129.862097.126  293.882081.701   317.5 2078.33   322.2 2076.18
   336.8 2065.43   345.1 2060.45  365.742054.938   372.8  2052.8   380.8 2052.31
   386.7 2052.51  395.212054.938   407.2 2060.69  421.592061.909   474.3    2062
   499.7 2063.44   535.1 2062.62   602.9 2065.75  716.432064.577   808.2 2065.18
   821.6 2069.06   828.8 2068.22   834.1 2068.92   855.2  2076.1     922 2109.02
#Mann= 7 ,-1 , 0
       0    .055       0  129.86     .05       0  293.88      .1       0
  365.74    .045       0  395.21      .1       0  421.59     .05       0
  716.43      .1       0
Bank Sta=365.74,395.21
XS Rating Curve= 0 ,0
Exp/Cntr(USF)=0,0
Exp/Cntr=0.5,0.3

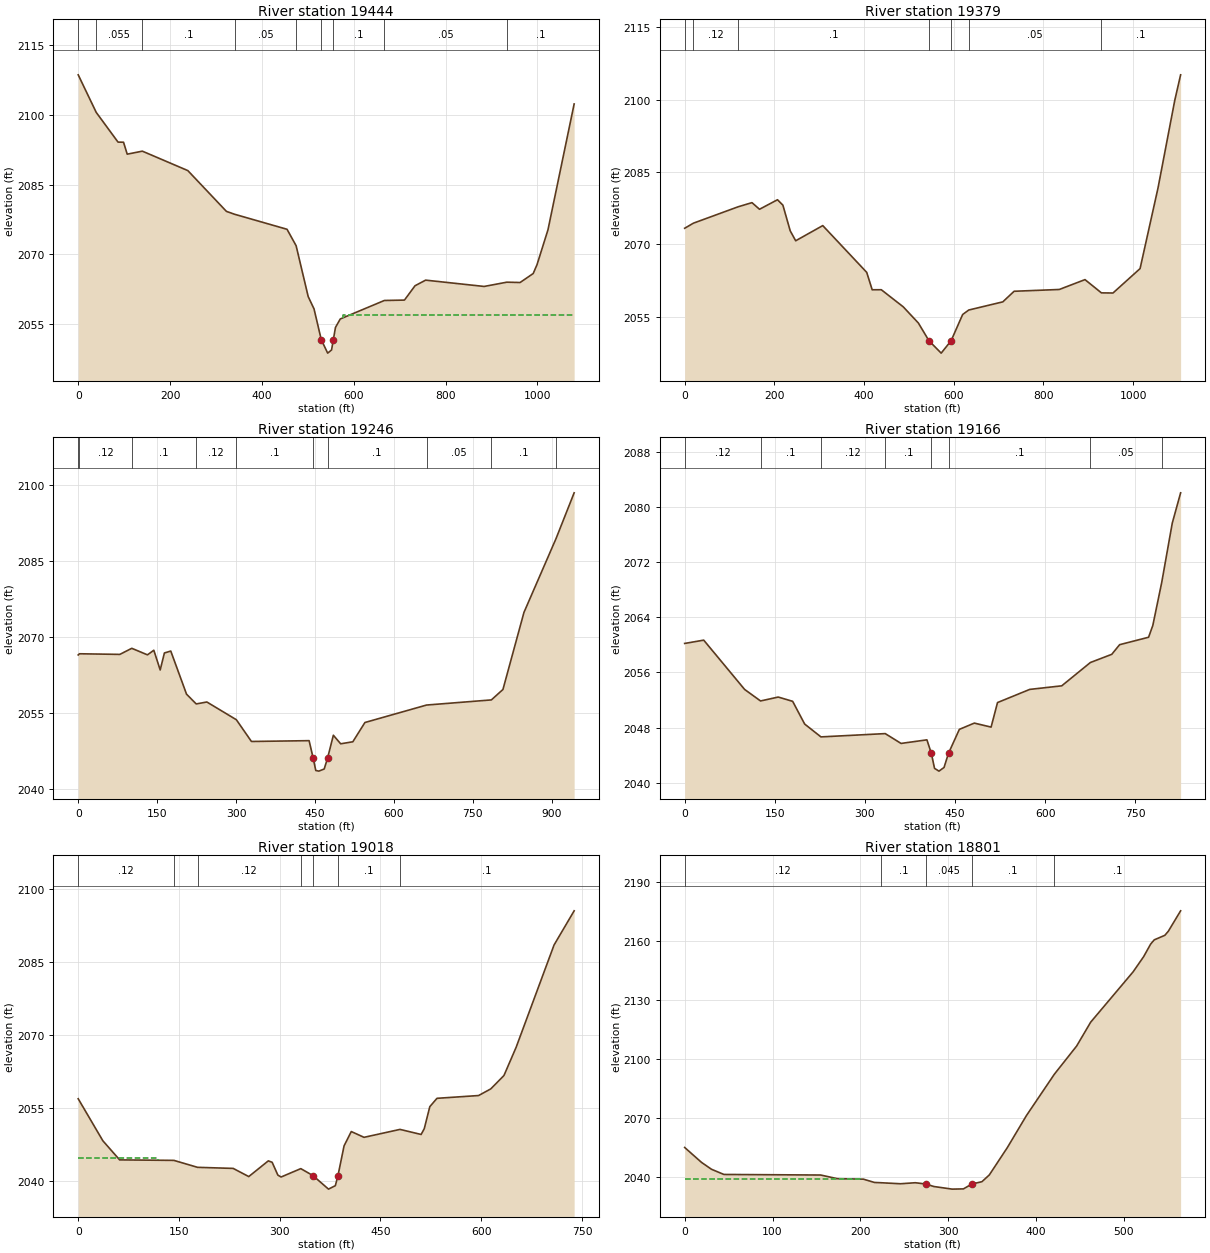
Type RM Length L Ch R = 1 ,19444   ,67.4,64.7,64.6
XS GIS Cut Line= 4
2460920.09538027614052.5592571922461382.68974262614049.301550415
2461563.49246874614112.8268325682461921.84021422614342.495160351
#Sta/Elev= 30
       0 2108.67   39.212100.578    86.7 2094.17    98.7 2094.14   106.7 2091.57
  139.722092.217   238.7 2088.03   322.7 2079.24  340.722078.612   454.7 2075.38
  474.492071.838   500.8 2060.87   513.5 2058.22  529.212051.602   543.2 2048.69
   551.7 2049.38  555.542051.598   560.2 2054.23   570.6 2056.05  666.582060.035
   710.4 2060.12   733.4 2063.21   756.5 2064.42   883.9 2063.06  933.312063.979
   962.2 2063.91   990.7 2065.84   999.1 2067.77  1022.9 2075.27  1079.9 2102.39
#Mann= 9 ,-1 , 0
       0     .12       0   39.21    .055       0  139.72      .1       0
  340.72     .05       0  474.49      .1       0  529.21    .045       0
  555.54      .1       0  666.58     .05       0  933.31      .1       0
#XS Ineff= 2 , 0
             508    2057     576            2057
Permanent Ineff=
       F       F
Bank Sta=529.21,555.54
XS Rating Curve= 0 ,0
Exp/Cntr(USF)=0,0
Exp/Cntr=0.5,0.3

Type RM Length L Ch R = 1 ,19379   ,126.7,133.1,137.3
XS GIS Cut Line= 4
2460863.08551167614200.7849155492461376.17432906 614109.56912579
2461473.90553237614151.9193138922461894.14970662614379.958788288
#Sta/Elev= 30
       0 2073.36   19.44 2074.41  118.762077.788     150 2078.66   166.9 2077.29
   206.9 2079.26     219 2078.14   235.3 2072.83   247.5 2070.77   307.9 2073.91
   405.9 2064.23   418.1 2060.63   438.4 2060.64   487.2 2057.11   521.1 2053.75
  544.772050.071   571.9 2047.52     594 2050.07   619.8 2055.51  633.41 2056.44
   709.4 2058.13   734.5 2060.32   835.2 2060.69   892.6 2062.73  929.22 2059.99
     955 2059.96  1015.4 2065.01  1055.3 2081.65  1092.8 2099.85  1105.8 2105.11
#Mann= 7 ,-1 , 0
       0      .1       0   19.44     .12       0  118.76      .1       0
  544.77    .045       0     594      .1       0  633.41     .05       0
  929.22      .1       0
Bank Sta=544.77,594
XS Rating Curve= 0 ,0
Exp/Cntr(USF)=0,0
Exp/Cntr=0.5,0.3

Type RM Length L Ch R = 1 ,19246   ,82.6,79.8,76.8
XS GIS Cut Line= 4
2460884.26060572614225.2177163772461250.75261814614177.980968109
2461442.95731799614288.7429985292461755.69716859614448.370630606
#Sta/Elev= 30
       0 2066.49    2.442066.723    79.1  2066.6  101.812067.803   131.6 2066.51
   143.7 2067.42   155.8 2063.52   163.8 2066.88   175.9 2067.26   205.9 2058.73
  224.292056.809   244.5 2057.19  300.552053.688   329.2 2049.39   438.8 2049.55
  446.45 2046.13   451.5 2043.66   457.2 2043.53   467.5 2043.95  473.952046.128
   484.9 2050.62   498.8 2048.93   521.9 2049.33   544.9 2053.14  662.052056.591
  785.212057.604   807.2 2059.67   847.1 2074.89  908.362089.557   942.5 2098.53
#Mann= 10 ,-1 , 0
       0      .1       0    2.44     .12       0  101.81      .1       0
  224.29     .12       0  300.55      .1       0  446.45    .045       0
  473.95      .1       0  662.05     .05       0  785.21      .1       0
  908.36      .1       0
Bank Sta=446.45,473.95
XS Rating Curve= 0 ,0
Exp/Cntr(USF)=0,0
Exp/Cntr=0.3,0.1

Type RM Length L Ch R = 1 ,19166   ,144.7,148.4,151.5
XS GIS Cut Line= 4
2460863.08551167614238.2485434852461131.84632078614236.619690096
  2461413.637957614327.8354798542461651.45055172614433.710950109
#Sta/Elev= 30
       0 2060.21    31.7 2060.69    99.7 2053.54  126.252051.863   155.7 2052.43
   179.7 2051.81   199.7 2048.51  226.772046.647  333.742047.125   360.1  2045.7
   403.1 2046.22  410.432044.276   415.8 2042.08   423.2 2041.68   431.6 2042.21
  439.072044.277   457.1 2047.74     482 2048.65   509.9 2048.07   520.6 2051.63
   574.2 2053.54   627.5 2054.06  675.162057.444   710.7 2058.63   723.8 2060.03
     772 2061.11     779 2062.81  793.862069.066   811.4 2077.67   825.3 2082.07
#Mann= 8 ,-1 , 0
       0     .12       0  126.25      .1       0  226.77     .12       0
  333.74      .1       0  410.43    .045       0  439.07      .1       0
  675.16     .05       0  793.86      .1       0
Bank Sta=410.43,439.07
XS Rating Curve= 0 ,0
Exp/Cntr(USF)=0,0
Exp/Cntr=0.3,0.1

Type RM Length L Ch R = 1 ,19018   ,199.1,216.5,225
XS GIS Cut Line= 4
2460864.71436506614246.3928104282461053.66135813614314.804652746
2461262.15459186614448.3706306062461508.11145353614601.482849129
#Sta/Elev= 30
       0 2056.95    36.7 2048.31    61.7 2044.38  142.44 2044.28  177.692042.851
   230.7 2042.63   253.9 2040.95     283 2044.18   288.7 2043.89   297.2 2041.26
     302 2040.86  331.342042.584   349.4 2041.16   372.6 2038.37   382.8 2039.08
  386.69 2041.15   395.8 2047.27   406.5 2050.21   425.5 2049.02  479.06 2050.65
   510.5 2049.61   515.2 2050.81   523.4 2055.32   534.1 2057.04     596 2057.61
   614.2 2058.98   633.8 2061.73   651.9 2067.52   708.4 2088.57   738.3 2095.59
#Mann= 7 ,-1 , 0
       0     .12       0  142.44      .1       0  177.69     .12       0
  331.34      .1       0   349.4    .045       0  386.69      .1       0
  479.06      .1       0
#XS Ineff= 2 , 0
          119.35 2044.78
Permanent Ineff=
       F       F
Bank Sta=349.4,386.69
XS Rating Curve= 0 ,0
Exp/Cntr(USF)=0,0
Exp/Cntr=0.3,0.1

Type RM Length L Ch R = 1 ,18801   ,149.6,156.1,161
XS GIS Cut Line= 4
2460832.13729729 614254.537077372460964.07442176614365.299107791
2461039.00167763 614588.452022022461053.66135813 614744.82194732
#Sta/Elev= 30
       0 2055.04    19.1 2047.49    30.5 2043.96    44.7 2041.32   154.9 2041.03
   173.9 2039.17   203.5 2038.93   216.1 2037.25   223.22037.116   245.7 2036.59
   262.6 2037.11  274.842036.443   283.7 2035.19   304.7 2033.86   317.4 2033.98
  326.992036.442   338.5 2037.65   346.9 2041.09   367.5 2055.06   389.1 2071.24
  420.942092.311   446.3 2106.64   462.3 2118.78   510.6 2144.37   522.6  2152.1
   530.6 2158.52   534.7 2160.66   546.7 2162.94   550.7 2165.02   564.7 2175.41
#Mann= 5 ,-1 , 0
       0     .12       0   223.2      .1       0  274.84    .045       0
  326.99      .1       0  420.94      .1       0
#XS Ineff= 2 , 0
          201.13 2039.08
Permanent Ineff=
       F       F
Bank Sta=274.84,326.99
XS Rating Curve= 0 ,0
Exp/Cntr(USF)=0,0
Exp/Cntr=0.3,0.1