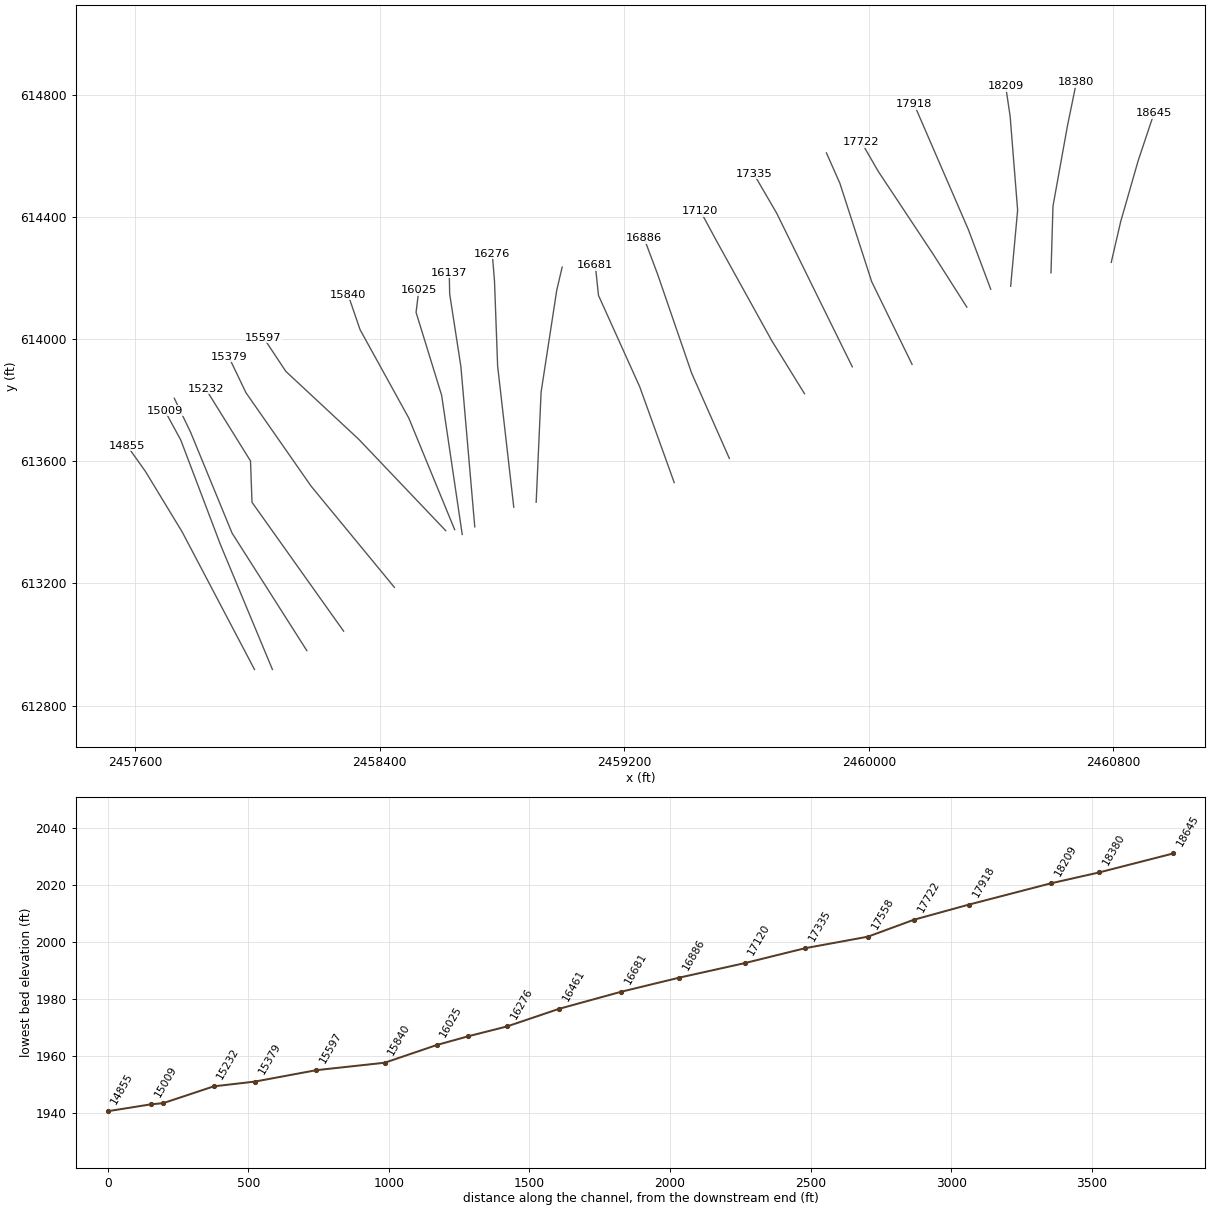
HEC-RAS study TROUTRN.prj: TROUTRN

--- TROUTRN.g01 (geometry) --- (continued)

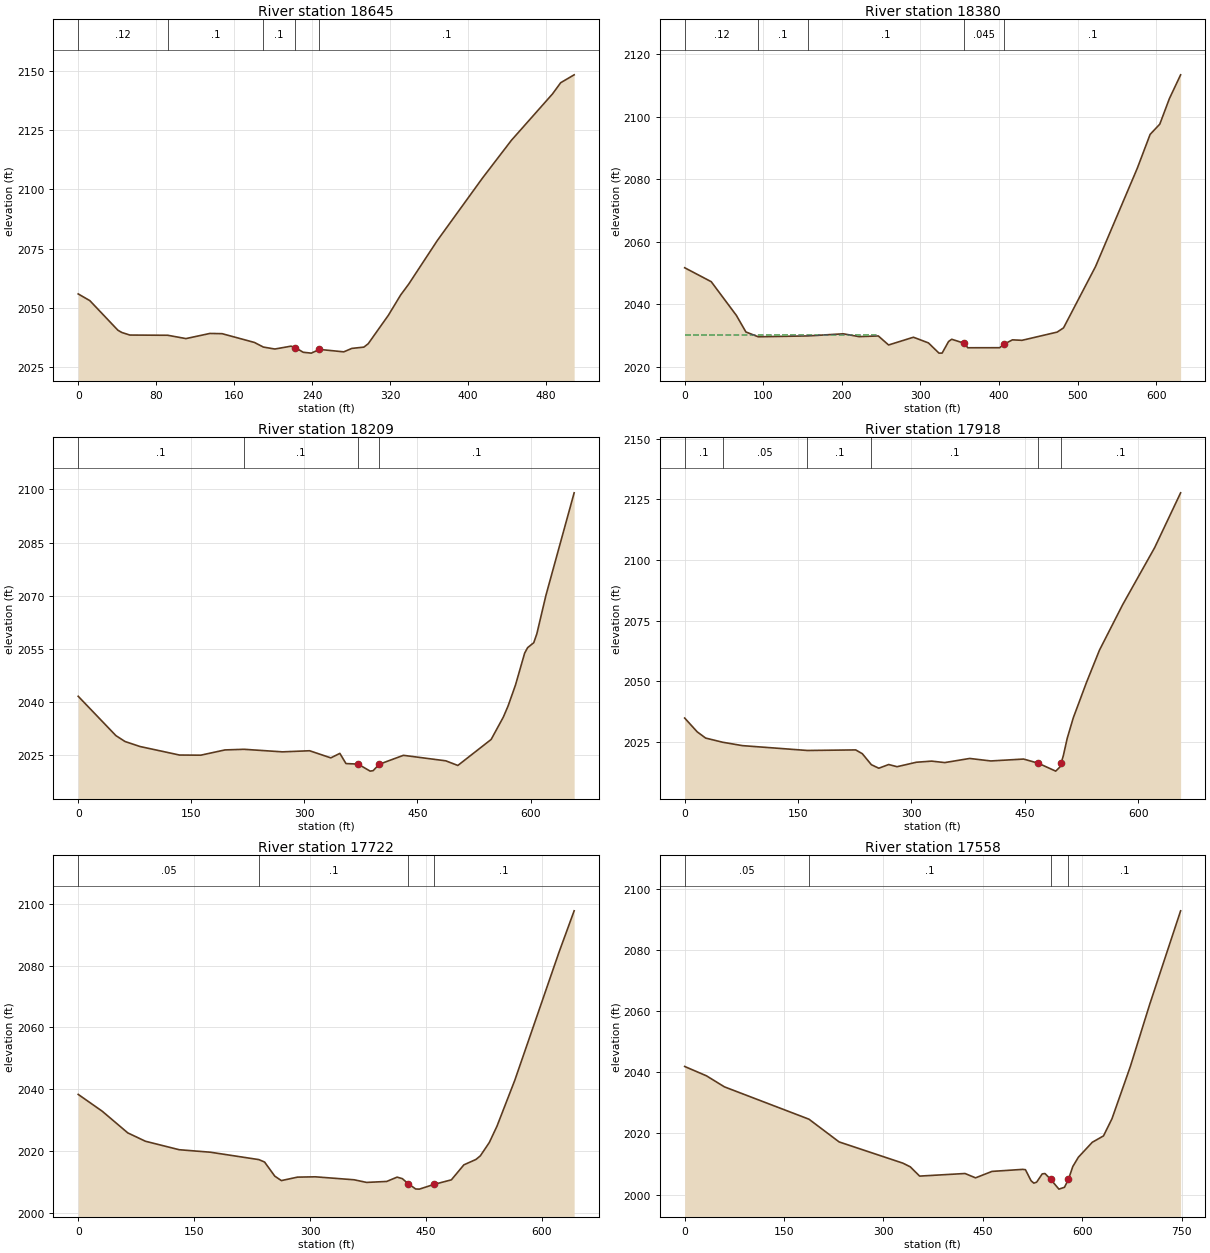
Type RM Length L Ch R = 1 ,18645   ,249.6,264.9,264.1
XS GIS Cut Line= 4
2460793.04481597614251.2793705932460823.99303035614384.845348453
2460881.00289895614583.5654618552460933.12620738614739.935387154
#Sta/Elev= 30
       0 2055.92    11.9 2053.11    40.7 2040.64    44.8 2039.68      53  2038.6
   91.842038.513   110.5 2037.11   135.1 2039.28   147.6 2039.18   180.8 2035.48
   189.92033.542   201.7 2032.72   218.3 2033.92   222.5 2033.34   230.8 2031.35
   239.1 2030.99   247.4 2032.55   272.4 2031.53   280.7 2032.98     293 2033.52
   297.4 2034.91   318.2 2046.97   330.7 2055.45     339 2060.06   368.4 2078.45
   414.8 2104.79   444.3  2120.6   486.5 2140.16   494.9 2144.88   508.7  2148.2
#Mann= 5 ,-1 , 0
       0     .12       0   91.84      .1       0   189.9      .1       0
   222.5    .045       0   247.4      .1       0
Bank Sta=222.5,247.4
XS Rating Curve= 0 ,0
Exp/Cntr(USF)=0,0
Exp/Cntr=0.3,0.1

Type RM Length L Ch R = 1 ,18380   ,153.4,170.7,170.8
XS GIS Cut Line= 4
2460595.95355595614217.0734494342460602.46896951614435.339803498
2460649.70571777614697.5851990522460679.02507877614840.924297243
#Sta/Elev= 30
       0 2051.62    33.8 2047.16    65.8 2036.37    77.9 2031.07   93.622029.528
  156.842029.807   201.9 2030.48     222 2029.58   246.4  2029.8   259.5 2026.91
   291.1 2029.39   310.2 2027.57   323.6  2024.3   327.6 2024.31   335.8 2028.01
   339.8 2028.74     356 2027.44   360.2 2026.02   400.8 2026.03   406.22027.132
   417.1 2028.55   429.3  2028.4     474 2031.03   482.1 2032.38   522.9 2052.04
     576 2083.48   592.3  2094.3   604.6 2097.58   616.8 2105.74   631.1 2113.36
#Mann= 5 ,-1 , 0
       0     .12       0   93.62      .1       0  156.84      .1       0
     356    .045       0   406.2      .1       0
#XS Ineff= 2 , 0
           243.9 2030.12
Permanent Ineff=
       F       F
Bank Sta=356,406.2
XS Rating Curve= 0 ,0
Exp/Cntr(USF)=0,0
Exp/Cntr=0.3,0.1

Type RM Length L Ch R = 1 ,18209   ,278,291.5,290.7
XS GIS Cut Line= 4
2460464.01643148614173.0944079432460486.82037892614422.308976389
2460462.38757809614728.533413434 2460447.7278976614827.893470135
#Sta/Elev= 30
       0 2041.62      50 2030.52    62.1 2028.86    82.1 2027.44   134.4 2025.04
   162.6    2025   194.6 2026.48  219.782026.661   270.9 2025.94     307 2026.25
   335.1 2024.24   347.1 2025.51   355.2 2022.63   371.2 2022.49   387.3  2020.5
   391.3 2020.64   399.3 2022.43   431.4 2024.96   487.6 2023.41   503.6  2022.1
   547.8 2029.44   563.9 2035.73   570.2 2038.86   580.1 2044.81   592.2 2053.78
   596.2 2055.36   604.3 2056.74   608.4 2059.25   620.5 2070.14   657.9 2099.04
#Mann= 4 ,-1 , 0
       0      .1       0  219.78      .1       0   371.2    .045       0
   399.3      .1       0
#XS Ineff= 2 , 0
          215.91 2026.59
Permanent Ineff=
       F       F
Bank Sta=371.2,399.3
XS Rating Curve= 0 ,0
Exp/Cntr(USF)=0,0
Exp/Cntr=0.3,0.1

Type RM Length L Ch R = 1 ,17918   ,190,195.6,194.6
XS GIS Cut Line= 4
2460398.86229594614163.3212876122460325.56389346614358.783694236
2460183.85364865614686.183225332 2460148.0188741614769.254748148
#Sta/Elev= 30
       0  2034.9    16.6 2029.21    27.7 2026.66   50.16 2024.94    76.4 2023.54
  162.352021.545   226.2 2021.78     235 2020.21  246.942015.682   256.8 2014.24
   269.9 2015.76   280.9 2014.86   306.5  2016.7   326.6 2017.16     344 2016.56
     377 2018.26     405 2017.23   448.3 2018.01   467.6 2016.31   490.8 2013.04
   496.5  2014.8  497.962016.312   500.9 2019.46     506 2026.55     514 2034.97
   531.4  2049.5   548.6 2062.83   579.3 2081.58   621.7 2105.12     656 2127.67
#Mann= 6 ,-1 , 0
       0      .1       0   50.16     .05       0  162.35      .1       0
  246.94      .1       0   467.6    .045       0  497.96      .1       0
Bank Sta=467.6,497.96
XS Rating Curve= 0 ,0
Exp/Cntr(USF)=0,0
Exp/Cntr=0.3,0.1

Type RM Length L Ch R = 1 ,17722   ,167.1,163.8,157.8
XS GIS Cut Line= 4
2460320.67733329614104.6825656252460209.91530287614278.969878198
2460030.74143013614549.3595406952459975.36041492614645.461890619
#Sta/Elev= 30
       0 2038.35    31.1 2032.91    64.2  2025.9      87 2023.21   130.6 2020.47
   171.1 2019.66  233.792017.273   241.2 2016.48   254.4 2011.92   262.9 2010.49
   283.8 2011.61   306.9 2011.71   357.1 2010.75   373.2  2009.9   399.2 2010.21
   412.7 2011.61   419.4 2011.12   427.1 2009.48   436.7 2007.78   441.5 2007.73
   460.7 2009.28   482.9 2010.73   499.1 2015.58   514.7 2017.32   520.4 2018.49
     532  2022.8   541.9 2028.05     565 2042.93   622.2  2084.3   641.8 2097.69
#Mann= 4 ,-1 , 0
       0     .05       0  233.79      .1       0   427.1    .045       0
   460.7      .1       0
Bank Sta=427.1,460.7
XS Rating Curve= 0 ,0
Exp/Cntr(USF)=0,0
Exp/Cntr=0.3,0.1

Type RM Length L Ch R = 1 ,17558   ,220.6,223.6,225.2
XS GIS Cut Line= 4
2460141.50346055613917.3644259432460009.56633608 614187.75408844
2459905.31971921614510.2670593712459861.34067772614609.627116071
#Sta/Elev= 30
       0  2041.9    32.9 2038.84      60 2035.23  187.572024.656   233.1 2017.22
   329.4 2010.27   340.5 2009.07   354.6 2006.04   423.1 2006.89     439 2005.47
   463.9 2007.58   510.1 2008.24   514.3 2008.14   522.8 2004.52     527 2003.74
   531.2 2004.06   539.6 2006.76   543.8 2006.88   552.2 2005.02   564.8 2001.78
   573.2 2002.38  579.27 2005.02   585.8 2009.18   594.2 2012.22   615.2 2017.11
   632.1 2019.19   644.9  2024.8   672.6 2041.88   701.7 2062.12   748.5 2092.81
#Mann= 4 ,-1 , 0
       0     .05       0  187.57      .1       0   552.2    .045       0
  579.27      .1       0
Bank Sta=552.2,579.27
XS Rating Curve= 0 ,0
Exp/Cntr(USF)=0,0
Exp/Cntr=0.3,0.1

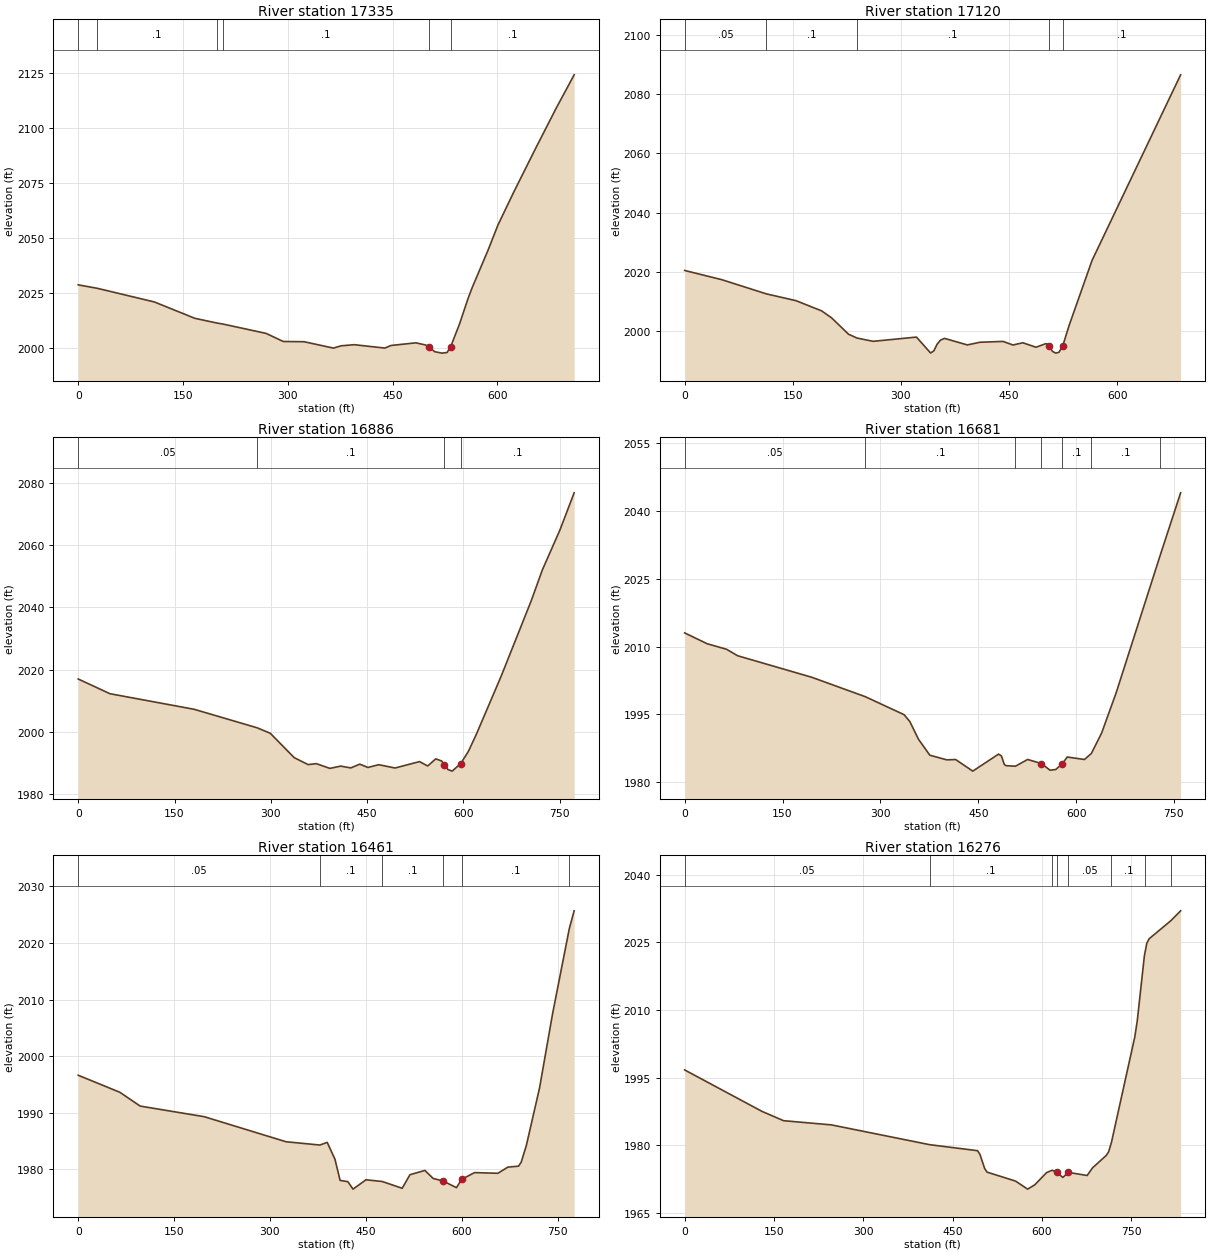
Type RM Length L Ch R = 1 ,17335   ,213.6,214.7,215.3
XS GIS Cut Line= 4
2459946.04105393   613909.2201592459835.27902351614134.001926619
2459698.45533887614412.535856058  2459623.528083614541.215273753
#Sta/Elev= 30
       0 2028.77   27.342027.195   108.9    2021   166.9 2013.56  198.61  2011.4
  207.022010.954   268.9  2006.7   293.5 2003.02   323.4 2002.91   365.2 2000.02
   376.4 2001.06   395.1 2001.56   438.8 2000.03   447.7 2001.21   483.3 2002.41
   496.8 2001.46   502.7 2000.43   510.1 1998.39   520.6 1997.73   527.9    1998
  533.172000.728   545.7 2010.93   557.9 2022.51   563.6  2027.3   586.8  2044.7
   600.7 2055.93   623.9 2071.28     656 2091.63     684 2109.01   709.8 2124.23
#Mann= 6 ,-1 , 0
       0     .05       0   27.34      .1       0  198.61      .1       0
  207.02      .1       0   502.7    .045       0  533.17      .1       0
Bank Sta=502.7,533.17
XS Rating Curve= 0 ,0
Exp/Cntr(USF)=0,0
Exp/Cntr=0.3,0.1

Type RM Length L Ch R = 1 ,17120   ,235.5,233.8,230.9
XS GIS Cut Line= 4
2459789.67112863 613821.262076022459682.16680498613995.549388593
2459504.62178563614316.4335061352459449.24077042614419.051269613
#Sta/Elev= 30
       0 2020.43    51.3 2017.33  113.392012.516   154.5 2010.22   189.9 2006.79
   203.7 2004.45   227.4 1998.88  239.081997.593   261.4 1996.49   321.6 1997.92
   341.2 1992.54   345.7 1993.27   350.3 1995.53   354.9 1996.89   360.6 1997.48
   392.2 1995.27   409.7 1996.17   441.7 1996.46   455.5 1995.25   469.2    1996
   487.5 1994.49   501.2 1995.72   505.7 1994.93   510.3 1993.09   514.9  1992.5
   519.5 1992.83   524.7 1995.06   533.5 2001.92   565.2 2023.81   688.1 2086.53
#Mann= 5 ,-1 , 0
       0     .05       0  113.39      .1       0  239.08      .1       0
   505.7    .045       0   524.7      .1       0
Bank Sta=505.7,524.7
XS Rating Curve= 0 ,0
Exp/Cntr(USF)=0,0
Exp/Cntr=0.3,0.1

Type RM Length L Ch R = 1 ,16886   ,204.8,205.3,205.5
XS GIS Cut Line= 4
2459543.71426696613609.6740208482459420.57295078613888.207950288
2459309.15937901614212.1868892682459265.18033752614329.464333243
#Sta/Elev= 30
       0 2016.95    49.4 2012.23   180.5 2007.23  278.722001.287   299.2 1999.52
   336.4 1991.71   358.1 1989.47   370.8 1989.78     392 1988.26   408.8 1988.99
   424.5 1988.41   438.5 1989.62   451.2 1988.56   468.1 1989.44   493.5 1988.38
   531.6 1990.44   544.3 1989.03   556.9 1991.32   566.2 1990.62   570.2 1989.48
   575.6 1987.92   582.3 1987.38  595.481989.724   607.7 1993.72   620.4 1999.35
   658.6 2017.79   705.6 2042.08   722.8 2051.92   750.2 2064.75   772.4 2076.71
#Mann= 4 ,-1 , 0
       0     .05       0  278.72      .1       0   570.2    .045       0
  595.48      .1       0
Bank Sta=570.2,595.48
XS Rating Curve= 0 ,0
Exp/Cntr(USF)=0,0
Exp/Cntr=0.3,0.1

Type RM Length L Ch R = 1 ,16681   ,226.3,220,210.2
XS GIS Cut Line= 4
2459363.40019685613530.5117461652459250.52065702613844.228908798
2459115.65159645614143.286390933 2459105.3898201614241.506250262
#Sta/Elev= 30
       0 2013.02    34.4 2010.63    64.2  2009.4    81.2 2007.97   194.6 2003.22
  276.781998.924   336.3 1994.94   345.1 1993.43   358.3 1989.53   375.8 1985.98
   401.8 1984.95   415.3 1985.03   441.6 1982.46   481.1 1986.22   485.5 1985.84
   489.9 1983.95   492.5 1983.67  506.931983.541   525.8 1985.04   546.9 1984.12
   560.1 1982.66   568.9 1982.83   578.9  1984.1   586.4 1985.58   612.8 1985.03
  623.361986.362   639.1 1990.87   661.5 1999.82  729.332030.367   760.2 2043.99
#Mann= 7 ,-1 , 0
       0     .05       0  276.78      .1       0  506.93      .1       0
   546.9    .045       0   578.9      .1       0  623.36      .1       0
  729.33      .1       0
Bank Sta=546.9,578.9
XS Rating Curve= 0 ,0
Exp/Cntr(USF)=0,0
Exp/Cntr=0.3,0.1

Type RM Length L Ch R = 1 ,16461   ,184.5,185.2,187.6
XS GIS Cut Line= 4
2458911.88203754613466.0091519792458928.00768609613826.637292202
2458979.31656783614160.8780075292458996.90818443614235.642378063
#Sta/Elev= 30
       0 1996.62      65 1993.62      97 1991.17   197.1  1989.3   325.2 1984.87
  378.16 1984.29   389.6 1984.76   401.7  1981.8   409.8 1978.04   421.9 1977.82
     430  1976.5   450.3 1978.15  475.691977.849   506.9 1976.65   519.1 1979.05
   542.5  1979.8   555.5 1978.38   570.6 1977.95   591.9 1976.76     600 1978.23
   620.2 1979.42   656.7  1979.3   672.3 1980.39     689 1980.56   693.1 1981.25
   701.2 1984.21   721.8 1994.34   742.3 2007.52   768.52022.561     776 2025.67
#Mann= 6 ,-1 , 0
       0     .05       0  378.16      .1       0  475.69      .1       0
   570.6    .045       0     600      .1       0   768.5      .1       0
Bank Sta=570.6,600
XS Rating Curve= 0 ,0
Exp/Cntr(USF)=0,0
Exp/Cntr=0.3,0.1

Type RM Length L Ch R = 1 ,16276   ,138.4,138.8,141.4
XS GIS Cut Line= 4
2458838.58363506613449.8835034332458785.80878527613911.663439083
2458775.54700892614190.1973685232458768.21716868614279.621419554
#Sta/Elev= 30
       0 1996.74   129.8 1987.56   166.1 1985.49   246.5 1984.56   411.7 1980.17
     492 1978.84     496 1978.04     504 1974.89     508 1974.09   556.1 1972.09
   576.1 1970.32   588.1 1971.27   608.1 1973.99   617.6 1974.51   625.3 1974.02
   635.3 1972.91   644.6 1974.03   676.2 1973.34   685.2 1975.04   708.2 1977.78
   712.2 1978.58  716.941980.645   756.2 2004.05   760.3 2007.55   772.3 2022.01
  773.792023.044   776.3 2024.79   780.3 2025.81  816.992029.847   833.2 2032.01
#Mann= 8 ,-1 , 0
       0     .05       0   411.7      .1       0   617.6     .05       0
   625.3    .045       0   644.6     .05       0  716.94      .1       0
  773.79     .05       0  816.99      .1       0
Bank Sta=625.3,644.6
XS Rating Curve= 0 ,0
Exp/Cntr(USF)=0,0
Exp/Cntr=0.3,0.1

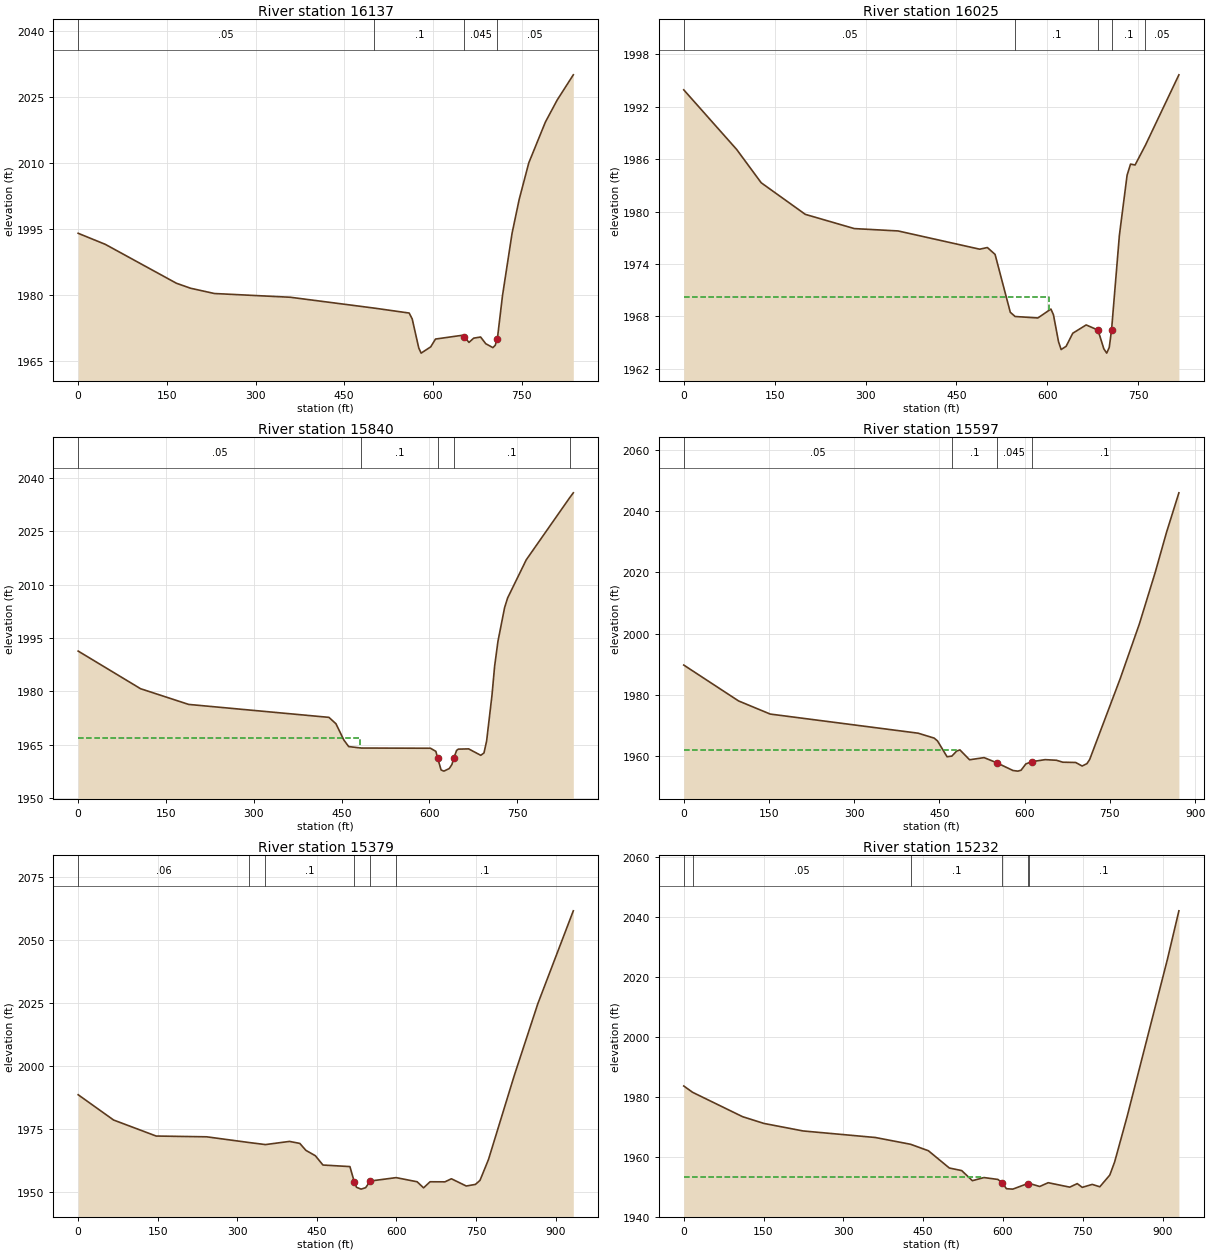
Type RM Length L Ch R = 1 ,16137   ,111.2,111.7,115.4
XS GIS Cut Line= 4
2458711.04441474613385.380909247 2458665.5994052613910.197471033
2458628.95020396614147.6842950822458627.48423591614218.050761467
#Sta/Elev= 30
       0 1994.08      46 1991.56   166.1 1982.73   190.1 1981.59   230.4 1980.39
   358.8 1979.54  500.911977.071   559.9 1975.95     565 1974.61   576.1 1968.01
   580.1 1966.84   596.3 1968.27   604.4 1970.04   648.9 1970.88   653.4 1970.51
     661 1969.28   669.1 1970.25   680.7  1970.5   689.4 1968.98   701.5 1968.09
   705.6 1968.65   708.7 1970.14   709.6 1970.71   717.7 1979.89   733.9 1994.08
     746 2001.81   762.2 2010.09   790.3 2019.37   810.3 2024.39   837.5  2030.1
#Mann= 4 ,-1 , 0
       0     .05       0  500.91      .1       0   653.4    .045       0
   708.7     .05       0
Bank Sta=653.4,708.7
XS Rating Curve= 0 ,0
Exp/Cntr(USF)=0,0
Exp/Cntr=0.3,0.1

Type RM Length L Ch R = 1 ,16025   ,180.7,185.6,185.3
XS GIS Cut Line= 4
2458669.99730935613360.4594524022458602.56277906613816.375515854
2458519.00260023614087.5796050452458527.79840853 614159.41203948
#Sta/Elev= 30
       0 1993.95    87.4 1987.11   127.8  1983.3   200.6 1979.68   281.5 1978.05
   353.7 1977.78   488.3 1975.69     501 1975.88   513.7 1975.09   538.8 1968.46
   546.81967.976   584.3 1967.81   605.8 1968.83     610 1968.18   618.4 1965.08
   622.7 1964.19   630.9 1964.56   641.9 1966.06     664 1967.01   683.5 1966.42
   693.1 1964.28   697.9 1963.78   702.1 1964.44   705.9 1966.45   718.8 1977.28
   731.5 1984.16   737.2 1985.44   744.7 1985.34  761.831987.615     817 1995.67
#Mann= 5 ,-1 , 0
       0     .05       0   546.8      .1       0   683.5    .045       0
   705.9      .1       0  761.83     .05       0
#XS Ineff= 2 , 0
          603.33  1970.2
Permanent Ineff=
       F       F
Bank Sta=683.5,705.9
XS Rating Curve= 0 ,0
Exp/Cntr(USF)=0,0
Exp/Cntr=0.3,0.1

Type RM Length L Ch R = 1 ,15840   ,237.4,242.5,247.5
XS GIS Cut Line= 4
2458645.23873784613376.259330271 2458495.3842261613741.122489303
2458335.75659402614031.0583924632458296.66411269614145.078129661
#Sta/Elev= 30
       0 1991.34   106.6 1980.75   188.8 1976.33   428.4 1972.69   440.4 1970.89
   453.8 1966.34   462.1 1964.47  483.551964.056   601.9    1964   611.1 1963.12
  614.181961.212     620 1957.89   624.8 1957.56   633.9 1958.28   638.5 1959.42
  641.751961.213   646.5 1963.38   649.5 1963.75   667.1 1963.82   687.8 1962.01
   693.3 1962.68   697.8 1966.06     707 1978.98   711.5 1987.13   717.2 1994.13
   728.5 2003.56   733.7  2006.3   765.5 2017.02  839.692034.492   845.9 2035.87
#Mann= 5 ,-1 , 0
       0     .05       0  483.55      .1       0  614.18    .045       0
  641.75      .1       0  839.69     .05       0
#XS Ineff= 2 , 0
          482.22 1967.01
Permanent Ineff=
       F       F
Bank Sta=614.18,641.75
XS Rating Curve= 0 ,0
Exp/Cntr(USF)=0,0
Exp/Cntr=0.3,0.1

Type RM Length L Ch R = 1 ,15597   ,210.6,218.8,216.9
XS GIS Cut Line= 4
2458615.91937685613373.0016234942458330.87003385613672.710646985
2458093.05743913613894.2347078262458019.75903664614004.996738247
#Sta/Elev= 30
       0 1989.68    96.5 1977.93   152.1 1973.64   412.4 1967.38   440.7 1965.77
   446.6 1964.84   463.4 1959.67  471.85 1959.88   480.3 1961.53     486 1961.91
     503 1958.68   528.6 1959.38   550.8  1957.7   579.4 1955.16   587.9 1954.96
   593.6 1955.25     602 1957.31     612 1958.03     636 1958.72   655.8 1958.52
   667.1 1957.88   689.8 1957.79   701.1 1956.63   709.6 1957.42   714.4 1958.78
   768.2 1985.28   801.8 2003.12   829.8 2020.07   849.7 2033.18   871.4 2046.05
#Mann= 4 ,-1 , 0
       0     .05       0  471.85      .1       0   550.8    .045       0
     612      .1       0
#XS Ineff= 2 , 0
          483.87 1962.01
Permanent Ineff=
       F       F
Bank Sta=550.8,612
XS Rating Curve= 0 ,0
Exp/Cntr(USF)=0,0
Exp/Cntr=0.3,0.1

Type RM Length L Ch R = 1 ,15379   ,155,146.2,134.5
XS GIS Cut Line= 4
2458448.14747783613187.3123372012458176.12896194613517.969575074
2457962.74916804613824.1940121192457905.73929945613943.100309482
#Sta/Elev= 30
       0 1988.51    66.8 1978.45     147 1972.08   242.2 1971.77  322.181969.495
  352.931968.677   398.3 1969.94   417.8 1969.14   429.3 1966.37   447.1 1964.24
   461.4 1960.54   512.2 1959.92   520.51953.829   524.6 1951.68   533.3 1950.95
   541.9 1951.53   550.5 1954.17  599.331955.527   638.9 1953.88   651.1 1951.46
   663.3 1953.88   691.3 1953.85   703.5 1955.07   731.5 1952.19   748.8 1952.83
   757.4 1954.43   773.4 1962.74   822.1 1996.23   866.4 2024.74   933.3 2061.71
#Mann= 6 ,-1 , 0
       0     .06       0  322.18     .05       0  352.93      .1       0
   520.5    .045       0   550.5      .1       0  599.33      .1       0
Bank Sta=520.5,550.5
XS Rating Curve= 0 ,0
Exp/Cntr(USF)=0,0
Exp/Cntr=0.3,0.1

Type RM Length L Ch R = 1 ,15232   ,173.3,179.8,184.5
XS GIS Cut Line= 4
 2458282.0044322 613043.973239012457982.29540871613465.846266641
2457977.40884854613601.0410978892457830.81204357613837.224839227
#Sta/Elev= 30
       0 1983.68   16.631981.569   110.6 1973.44   150.7 1971.19   224.4 1968.68
   360.1  1966.5  426.451964.238   459.9 1962.08   499.2 1956.33   522.5 1955.46
   542.6 1952.09   564.4 1953.14   590.6 1952.51  598.751951.343   606.6 1949.42
   618.5 1949.28   646.6 1951.14  648.571951.239   669.1 1950.16   685.1 1951.42
   725.6 1949.94   739.7 1951.12   749.1 1949.87   767.9 1950.86   782.1 1950.06
   800.9 1953.97     810 1958.35   833.3 1973.38   909.2 2025.92   930.8  2042.1
#Mann= 6 ,-1 , 0
       0     .06       0   16.63     .05       0  426.45      .1       0
  598.75    .045       0   646.6      .1       0  648.57      .1       0
#XS Ineff= 2 , 0
          563.15 1953.16
Permanent Ineff=
       F       F
Bank Sta=598.75,646.6
XS Rating Curve= 0 ,0
Exp/Cntr(USF)=0,0
Exp/Cntr=0.5,0.3

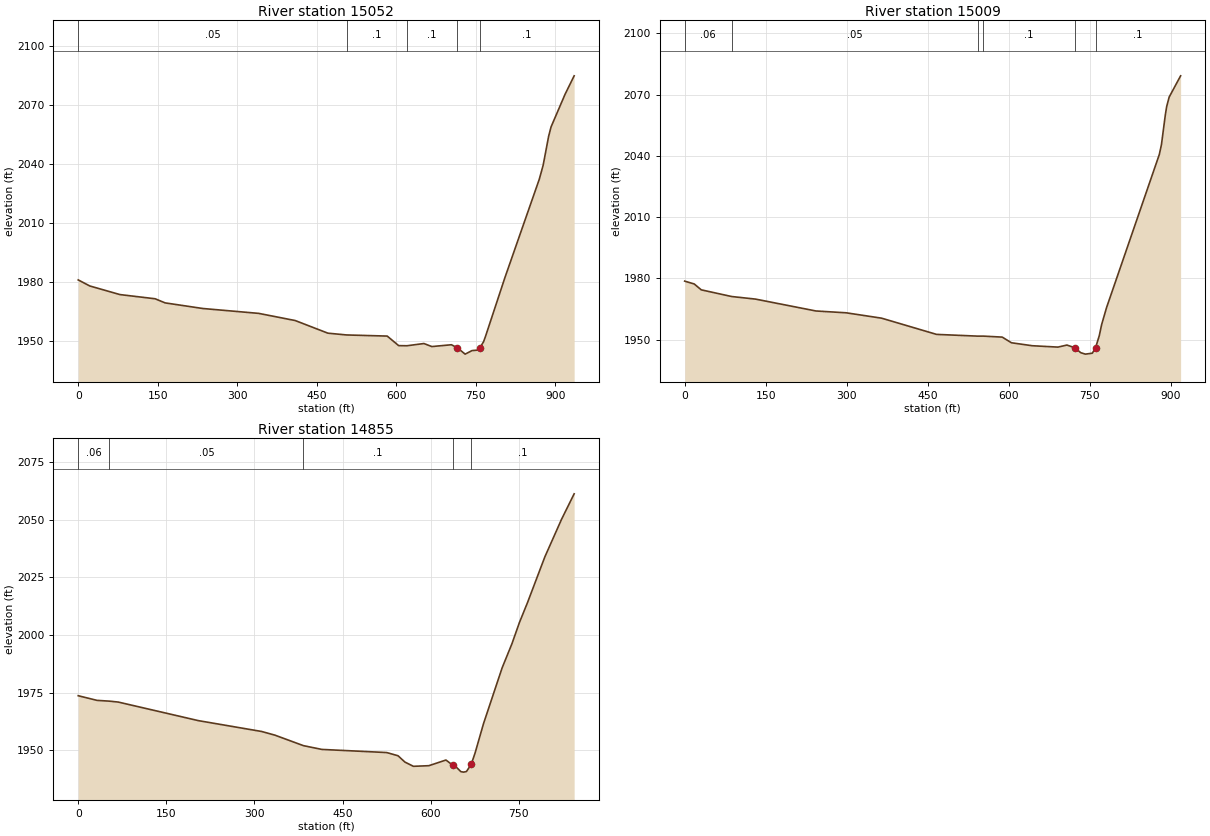
Type RM Length L Ch R = 1 ,15052   ,43.5,43.6,42
XS GIS Cut Line= 4
2458161.46928145612980.4479568572457917.14127316613364.857356551
2457781.94644192613693.8857410362457728.19428009613806.276624845
#Sta/Elev= 30
       0 1981.06    21.9 1977.98    78.7 1973.62   145.1 1971.49     164  1969.4
   235.1 1966.55   340.6 1964.07   409.4 1960.44   471.1 1954.03  506.241953.123
   583.1 1952.55   604.7  1947.7  620.231947.637   652.3 1948.77   667.3 1947.23
   704.2 1948.15  715.381946.613   730.1 1943.39   743.1 1945.19   753.1  1945.4
  757.831946.615   764.7 1949.57   768.5 1952.37   805.2 1982.26     870 2032.15
   877.3 2039.27   887.7 2054.02   892.3 2058.77   918.7 2075.31   935.8 2084.65
#Mann= 5 ,-1 , 0
       0     .05       0  506.24      .1       0  620.23      .1       0
  715.38    .045       0  757.83      .1       0
#XS Ineff= 2 , 0
             695 1946.67     777         1946.67
Permanent Ineff=
       F       F
Bank Sta=715.38,757.83
XS Rating Curve= 0 ,0
Exp/Cntr(USF)=0,0
Exp/Cntr=0.5,0.3

Type RM Length L Ch R = 1 ,15009   ,146.6,154,156.3
XS GIS Cut Line= 4
2458049.07839764612918.5515280922457879.67764523613325.764875227
2457749.36937415613669.4529402082457697.24606571613765.555290131
#Sta/Elev= 30
       0  1978.7    17.7 1977.31    30.7 1974.44    86.81971.173     131 1969.91
     243 1964.09   298.8  1963.2   364.3 1960.58   466.2 1952.63  542.031951.783
   552.81951.788   587.7  1951.3   604.8 1948.53   643.3 1947.08   690.8 1946.41
   707.5 1947.41   721.91946.093   733.1 1943.67   741.7 1942.97   754.5 1943.43
  760.511946.092   767.4 1952.05   771.6  1957.3   780.7 1965.65   878.5 2040.72
   882.4 2045.47   889.6 2060.07   892.1 2064.16   896.7 2068.79   917.9  2079.2
#Mann= 6 ,-1 , 0
       0     .06       0    86.8     .05       0  542.03      .1       0
   552.8      .1       0   721.9    .045       0  760.51      .1       0
Bank Sta=721.9,760.51
XS Rating Curve= 0 ,0
Exp/Cntr(USF)=0,0
Exp/Cntr=0.5,0.3

Type RM Length L Ch R = 1 ,14855   ,236.9,239.6,240
XS GIS Cut Line= 4
2457990.43967565612918.5515280922457754.25593431613368.115063329
2457633.72078356 613566.835176732457573.45320818613651.535552934
#Sta/Elev= 30
       0 1973.69      32 1971.67   52.781971.337    68.1 1970.94   204.4 1962.89
   312.2 1958.18   334.8 1956.59   383.41952.032   414.7  1950.4   525.1 1949.04
   544.4 1947.65   556.1 1944.92   570.6 1943.07   596.9 1943.34     626  1945.8
   637.4 1943.57   642.1 1943.09   651.4 1940.75   656.1 1940.55   660.9 1940.82
  669.021943.951   675.5 1948.79     690 1961.65   721.6 1985.77   738.3 1996.23
     751 2005.41   764.9 2014.14   794.3 2033.89   822.7 2050.18   844.2 2061.25
#Mann= 5 ,-1 , 0
       0     .06       0   52.78     .05       0   383.4      .1       0
   637.4    .045       0  669.02      .1       0
Bank Sta=637.4,669.02
XS Rating Curve= 0 ,0
Exp/Cntr(USF)=0,0
Exp/Cntr=0.3,0.1