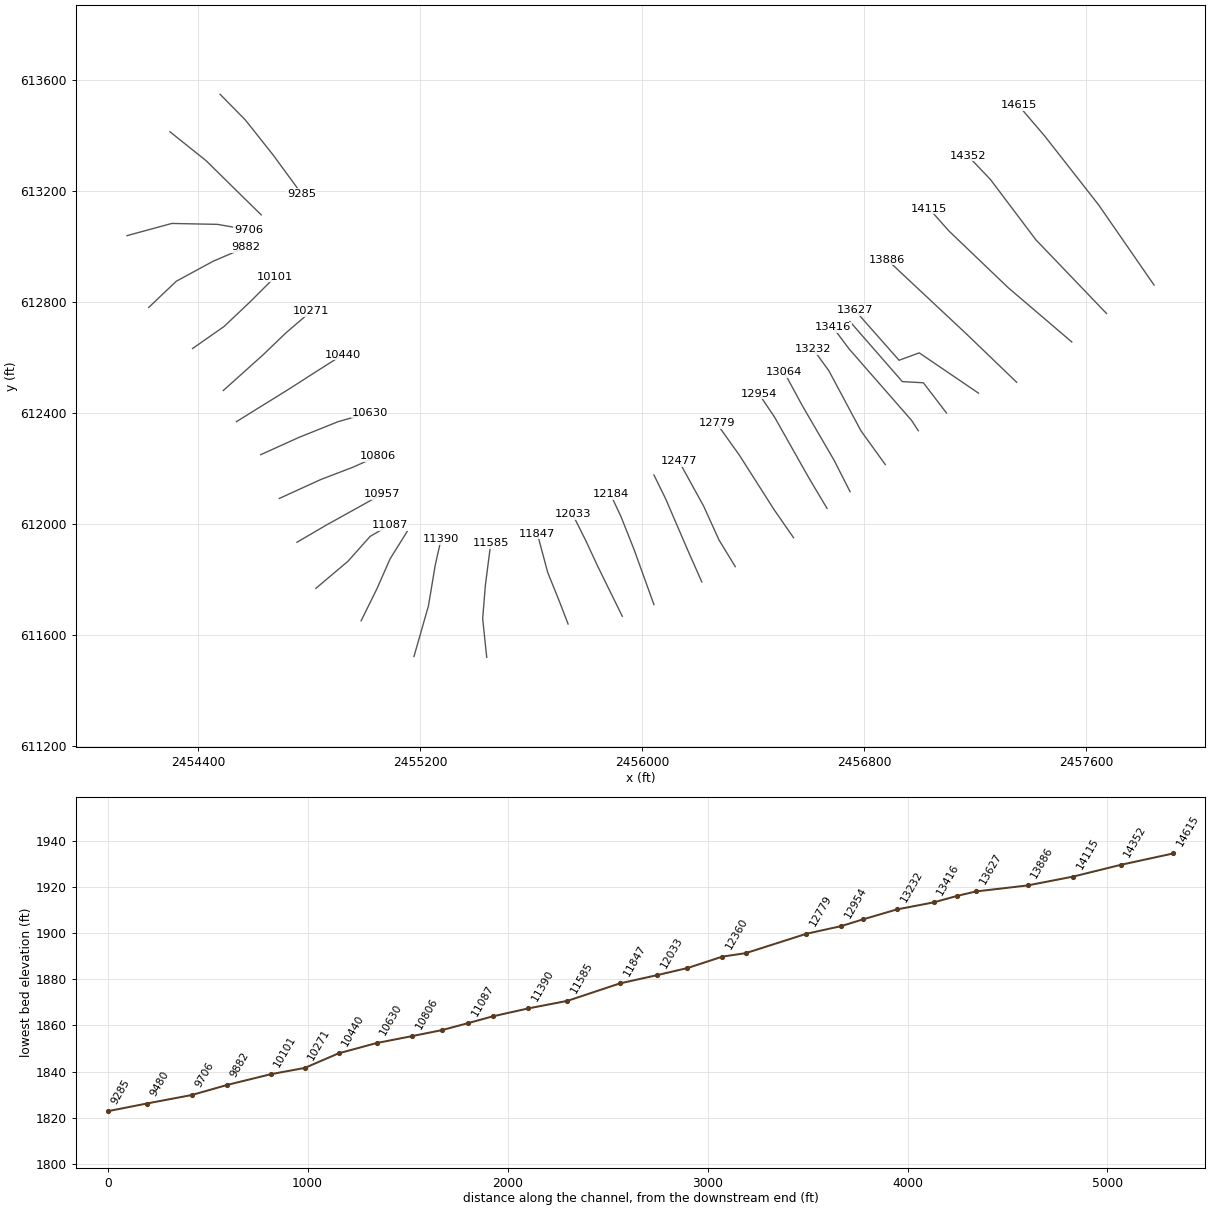
HEC-RAS study TROUTRN.prj: TROUTRN

--- TROUTRN.g01 (geometry) --- (continued)

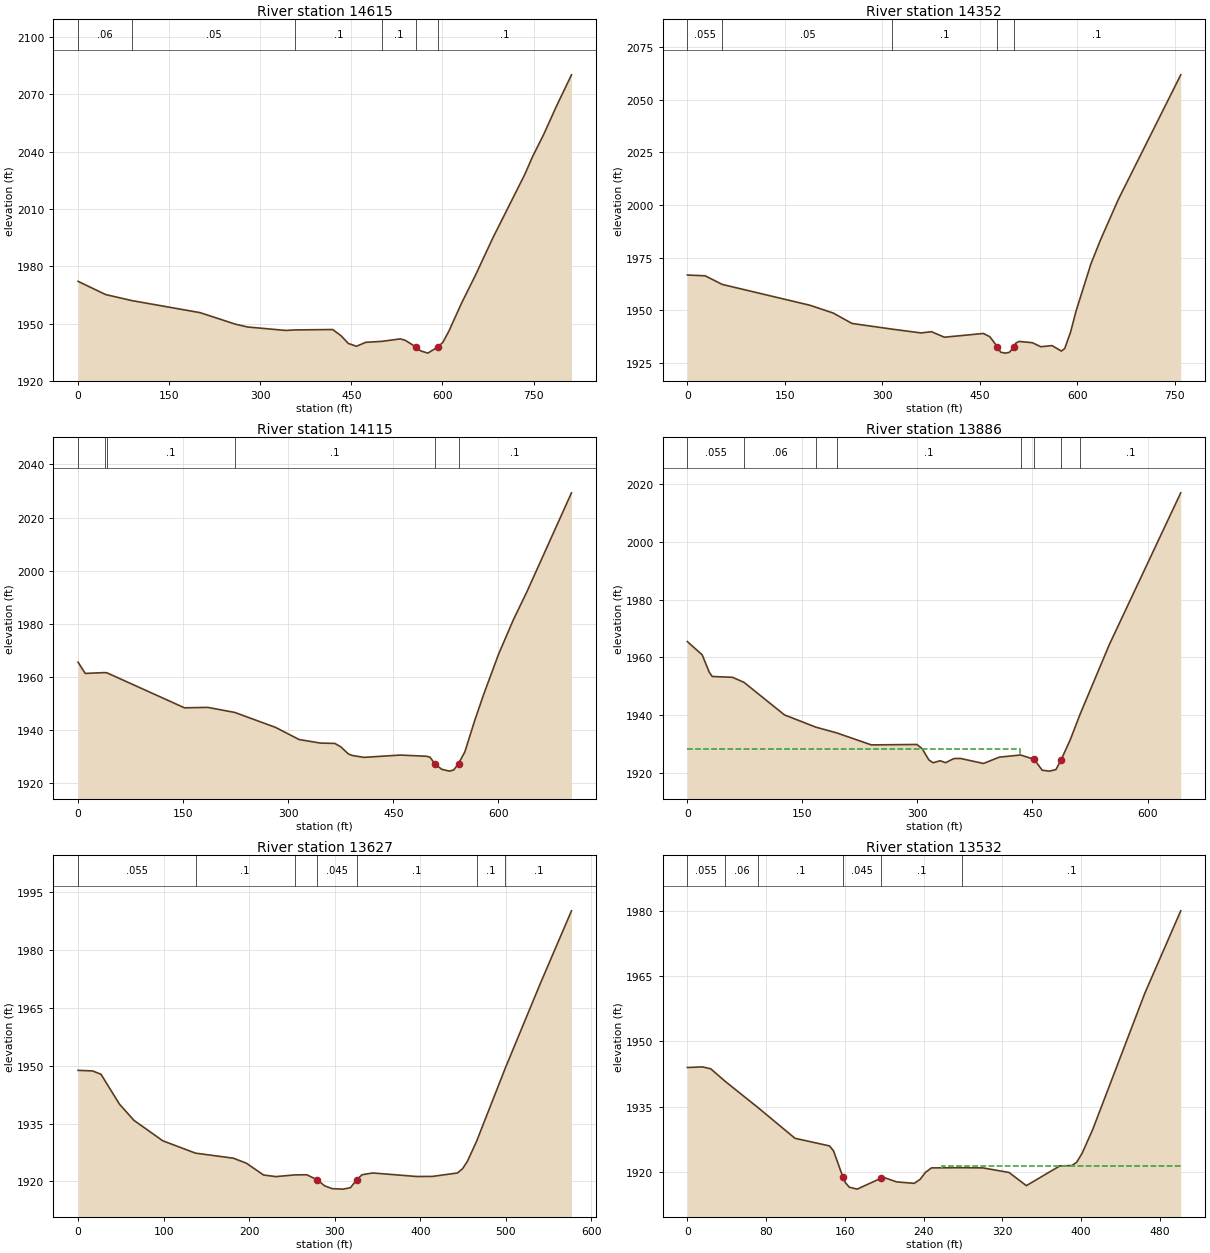
Type RM Length L Ch R = 1 ,14615   ,262.2,263.5,265
XS GIS Cut Line= 4
2457845.47172407612861.5416594942457645.12275728613151.477562653
2457451.28920404613399.0632777112457356.81570751613509.825308131
#Sta/Elev= 30
       0 1972.08    45.4 1965.16   88.361962.012     201 1955.69   258.8 1949.68
     279 1948.19     342 1946.38  357.451946.651   419.2 1946.86     433 1943.61
   444.9 1939.59   458.4  1938.1   473.6 1940.16  500.161940.668   530.4 1941.96
   538.9 1941.19  556.031937.772   563.9 1935.72   575.9 1934.51  592.561937.771
   600.6 1940.15   610.8 1946.18   631.1 1960.48   654.8 1975.62   682.4 1994.47
   735.5 2028.02   747.8    2037   766.5 2048.86   787.6 2063.71   812.4 2080.16
#Mann= 6 ,-1 , 0
       0     .06       0   88.36     .05       0  357.45      .1       0
  500.16      .1       0  556.03    .045       0  592.56      .1       0
Bank Sta=556.03,592.56
XS Rating Curve= 0 ,0
Exp/Cntr(USF)=0,0
Exp/Cntr=0.3,0.1

Type RM Length L Ch R = 1 ,14352   ,230.6,237,238.4
XS GIS Cut Line= 4
2457674.10249452612759.0333799882457419.38468068613024.923027774
2457256.27590514613241.6566062212457173.60433398613328.796910958
#Sta/Elev= 30
       0  1966.7    27.5 1966.33   53.761962.227     189  1952.3   224.6 1948.62
   253.5 1943.67  315.651940.954   359.9 1939.16   375.8 1939.76   395.7 1937.13
   455.8 1938.91   465.8 1937.34  477.361932.579   482.4 1929.98     490 1929.56
   495.8 1929.95   502.3 1932.36   505.8 1934.35   510.8 1935.12   530.9 1934.53
   544.3  1932.6   561.5 1933.15   575.7 1930.54   580.9  1931.7     590 1939.59
   598.6 1949.74   621.4 1972.08     636 1983.36   663.2 2002.43   759.6  2061.9
#Mann= 5 ,-1 , 0
       0    .055       0   53.76     .05       0  315.65      .1       0
  477.36    .045       0   502.3      .1       0
Bank Sta=477.36,502.3
XS Rating Curve= 0 ,0
Exp/Cntr(USF)=0,0
Exp/Cntr=0.3,0.1

Type RM Length L Ch R = 1 ,14115   ,228,229,228.8
XS GIS Cut Line= 4
2457548.97795439612656.2525077352457318.83817521612852.876785089
2457106.57333034613056.2041628082457035.07359312 613136.64136718
#Sta/Elev= 30
       0  1965.5    10.2 1961.29   37.871961.595   41.171961.516   151.9 1948.33
     185  1948.5  223.581946.599   281.8 1940.97   315.5 1936.39   346.1 1935.05
   366.4 1934.93     375 1933.65   385.9 1930.94   391.5 1930.38   408.1 1929.67
   459.8 1930.54   496.7  1930.1   502.2 1929.78  508.991927.359   518.8 1925.21
   529.9 1924.49   536.2 1924.93  543.12 1927.36   552.1 1931.74   565.8 1943.26
   578.6 1953.13   600.2 1968.52   621.1 1981.35   640.9 1992.18   704.3  2029.3
#Mann= 6 ,-1 , 0
       0    .055       0   37.87     .06       0   41.17      .1       0
  223.58      .1       0  508.99    .045       0  543.12      .1       0
#XS Ineff= 2 , 0
          466.02 1930.38
Permanent Ineff=
       F       F
Bank Sta=508.99,543.12
XS Rating Curve= 0 ,0
Exp/Cntr(USF)=0,0
Exp/Cntr=0.3,0.1

Type RM Length L Ch R = 1 ,13886   ,231.9,258.8,277.6
XS GIS Cut Line= 4
2457350.11931024612511.0186665082457169.13560041612685.299275981
2456959.10512232612881.9235533352456883.13665153612953.423290555
#Sta/Elev= 30
       0 1965.44    19.3 1960.89    28.6 1954.84    32.4 1953.38    58.9 1953.09
   73.921951.336   126.7 1940.08  167.681935.841  194.731933.868   239.9 1929.71
   299.4 1929.86   306.3 1928.35   314.8 1924.55   320.3 1923.54   329.7 1924.23
   336.7 1923.56   347.5 1924.98     356 1925.03     386 1923.29   406.9 1925.48
  434.591926.215   452.2 1924.72   462.7 1920.94     472 1920.64   480.5 1921.15
  486.971924.332   499.4 1931.59  512.251940.438   550.4 1964.53   643.3  2016.9
#Mann= 8 ,-1 , 0
       0    .055       0   73.92     .06       0  167.68      .1       0
  194.73      .1       0  434.59      .1       0   452.2    .045       0
  486.97      .1       0  512.25      .1       0
#XS Ineff= 2 , 0
          434.24 1928.24
Permanent Ineff=
       F       F
Bank Sta=452.2,486.97
XS Rating Curve= 0 ,0
Exp/Cntr(USF)=0,0
Exp/Cntr=0.5,0.3

Type RM Length L Ch R = 1 ,13627   ,101.7,95.2,84.5
XS GIS Cut Line= 4
2457212.73133426612471.6509270582456998.99319262612616.992863376
2456926.32222446612590.2755956712456767.08730894 612770.88432536
#Sta/Elev= 30
       0 1948.83    16.9 1948.69    26.8 1947.81    48.4 1940.06    65.3 1935.86
    99.1 1930.55  137.261927.354   181.4 1926.05   196.7 1924.75   216.8 1921.68
   231.2 1921.27  253.121921.705   267.3 1921.75   279.21920.476   288.3 1918.86
   297.1 1918.14   309.9 1918.02   318.4  1918.4  325.691920.477     332 1921.76
   344.5 1922.21   395.6  1921.3   413.9 1921.31   443.4 1922.21   449.4 1923.32
   455.1 1925.26  465.831930.463  499.351949.424   540.1 1971.27   576.7 1990.22
#Mann= 7 ,-1 , 0
       0    .055       0  137.26      .1       0  253.12      .1       0
   279.2    .045       0  325.69      .1       0  465.83      .1       0
  499.35      .1       0
#XS Ineff= 2 , 0
             255  1921.3     348          1921.3
Permanent Ineff=
       F       F
Bank Sta=279.2,325.69
XS Rating Curve= 0 ,0
Exp/Cntr(USF)=0,0
Exp/Cntr=0.5,0.3

Type RM Length L Ch R = 1 ,13532   ,125.1,115.6,94.8
XS GIS Cut Line= 4
2457097.31273778612400.0486496082457013.95486254612509.055101846
2456938.07782225612513.329864679 2456748.9195669612730.274078447
#Sta/Elev= 30
       0 1944.02    15.3 1944.16    23.8 1943.72   37.991940.922   71.971934.771
   109.3 1927.75   144.4 1925.99   148.5 1924.85  158.061918.801   160.5 1917.55
   164.5  1916.5   172.5 1916.06   196.5 1918.55   200.5 1918.66   212.6 1917.72
   230.5 1917.39   236.6 1918.35   241.8 1919.91   247.9 1920.94  279.421920.989
   300.2 1920.94   326.7 1919.89   344.3 1916.86   378.3  1921.4   390.4 1921.48
   395.3  1922.2     401 1924.34   411.7 1929.77   464.7 1961.14   501.1 1980.04
#Mann= 6 ,-1 , 0
       0    .055       0   37.99     .06       0   71.97      .1       0
  158.06    .045       0   196.5      .1       0  279.42      .1       0
#XS Ineff= 2 , 0
                          258.87         1921.35
Permanent Ineff=
       F       F
Bank Sta=158.06,196.5
XS Rating Curve= 0 ,0
Exp/Cntr(USF)=0,0
Exp/Cntr=0.5,0.3

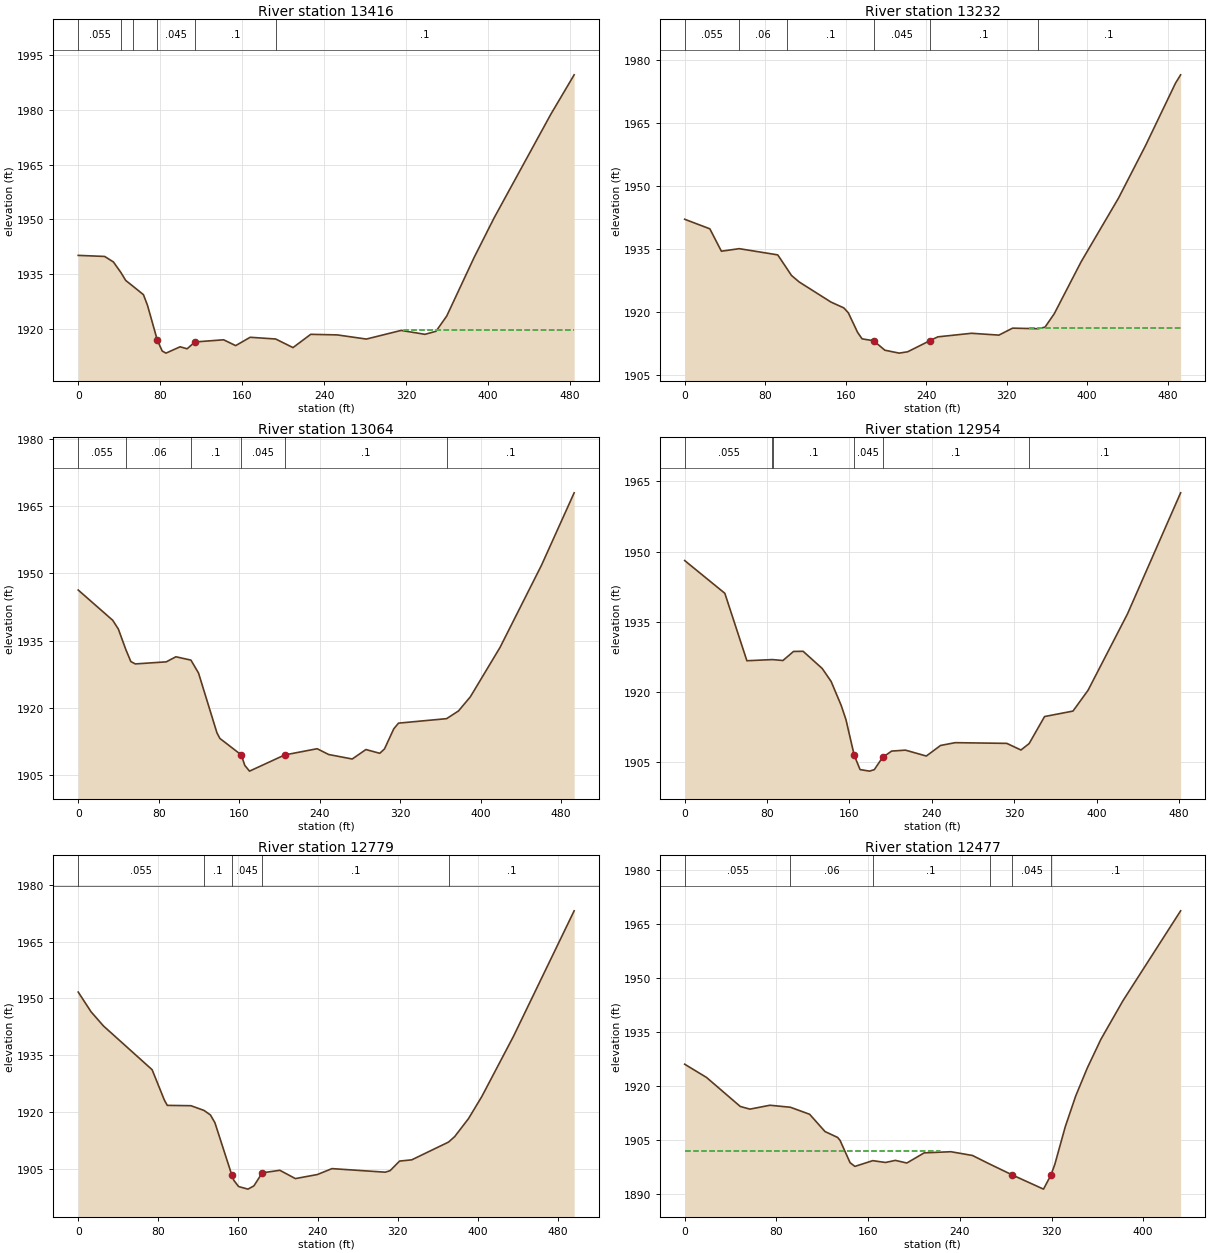
Type RM Length L Ch R = 1 ,13416   ,181.4,184,181.6
XS GIS Cut Line= 4
2456995.67130902612336.1619248882456971.23850819612373.625552824
2456746.45674057612630.9843882132456687.81801859612709.169350863
#Sta/Elev= 30
       0 1940.12    25.8 1939.83    34.4 1938.31   41.651935.429    46.4 1933.24
   53.441931.665    63.7 1929.34    67.7 1926.36   77.33 1916.78      82 1913.89
    85.7  1913.3    99.5 1915.04   106.3 1914.49     114 1916.36     142 1916.96
   153.7 1915.36   167.9 1917.65  192.781917.176   209.7 1914.82     227 1918.46
   252.9  1918.3   281.3 1917.16   315.3 1919.53   338.5 1918.46   349.3 1919.29
   359.8 1923.48   386.4 1939.47   405.9 1950.33   461.3 1978.78   484.2 1989.66
#Mann= 6 ,-1 , 0
       0    .055       0   41.65     .06       0   53.44      .1       0
   77.33    .045       0     114      .1       0  192.78      .1       0
#XS Ineff= 2 , 0
                          318.55         1919.72
Permanent Ineff=
       F       F
Bank Sta=77.33,114
XS Rating Curve= 0 ,0
Exp/Cntr(USF)=0,0
Exp/Cntr=0.3,0.1

Type RM Length L Ch R = 1 ,13232   ,156.6,168.3,162.8
XS GIS Cut Line= 4
2456876.76501166612213.9979207472456788.80692868612336.161924888
2456673.15833809612552.7994255632456616.14846949612630.984388213
#Sta/Elev= 30
       0 1942.08      25 1939.81    36.5 1934.48   54.221935.087    92.5 1933.61
  101.671930.338   106.1 1928.73   113.8 1927.17   145.4 1922.39   158.2    1921
   162.7 1919.82   171.8 1915.21   176.3 1913.65  187.761913.191     199 1910.94
   213.2 1910.25   221.6 1910.57  243.521913.191   251.6 1914.12   285.1 1914.97
   312.3 1914.53   325.9 1916.19     3511916.053   358.1 1916.42   367.3 1919.61
   393.9 1931.92   431.2 1947.12   458.1 1959.63   487.8 1974.43   492.9 1976.42
#Mann= 6 ,-1 , 0
       0    .055       0   54.22     .06       0  101.67      .1       0
  187.76    .045       0  243.52      .1       0     351      .1       0
#XS Ineff= 2 , 0
                          343.41          1916.3
Permanent Ineff=
       F       F
Bank Sta=187.76,243.52
XS Rating Curve= 0 ,0
Exp/Cntr(USF)=0,0
Exp/Cntr=0.3,0.1

Type RM Length L Ch R = 1 ,13064   ,110.7,110.4,112.7
XS GIS Cut Line= 4
2456749.71444735612116.2667174352456692.70457875612228.657601244
2456577.05598817612427.3777146462456511.90185262612547.912865398
#Sta/Elev= 30
       0  1946.3    34.3 1939.56    39.9 1937.61   47.281933.074    52.3 1930.37
    56.8 1929.84    87.5  1930.3    97.1 1931.43  112.04 1930.69   119.6 1927.81
   137.9  1914.5   140.8 1913.25   162.11909.573   165.6 1907.24   170.3 1905.96
   205.2 1909.56   237.5 1910.95     249 1909.66   272.4 1908.66     286 1910.77
   299.8 1909.93   304.5 1910.92   313.7 1915.39   318.4 1916.65  366.211917.648
     378 1919.36   389.8 1922.51   419.3 1933.51   460.6 1951.85     493 1967.95
#Mann= 6 ,-1 , 0
       0    .055       0   47.28     .06       0  112.04      .1       0
   162.1    .045       0   205.2      .1       0  366.21      .1       0
Bank Sta=162.1,205.2
XS Rating Curve= 0 ,0
Exp/Cntr(USF)=0,0
Exp/Cntr=0.3,0.1

Type RM Length L Ch R = 1 ,12954   ,173.9,174.1,174.7
XS GIS Cut Line= 4
2456666.64292454612055.9991420592456599.85993561612168.390025868
2456477.69593147612385.0275265442456420.68606287612469.727902748
#Sta/Elev= 30
       0 1948.08      39 1941.07    60.4 1926.64   85.24 1926.89   85.411926.886
    95.4 1926.69   105.7 1928.63     115 1928.66   133.6 1924.97   142.2  1922.2
     152 1917.06   156.6 1914.03   164.61906.414   170.3 1903.35   179.5 1903.02
   184.1 1903.34   192.1 1905.94   200.9 1907.31   214.4 1907.51   234.6 1906.25
   248.4 1908.51   262.6 1909.11   312.7 1908.96   326.5 1907.54  334.44 1908.92
   349.4  1914.7     377 1915.87   391.6 1920.31   429.9 1936.66   481.5 1962.57
#Mann= 6 ,-1 , 0
       0    .055       0   85.24     .06       0   85.41      .1       0
   164.6    .045       0   192.1      .1       0  334.44      .1       0
Bank Sta=164.6,192.1
XS Rating Curve= 0 ,0
Exp/Cntr(USF)=0,0
Exp/Cntr=0.3,0.1

Type RM Length L Ch R = 1 ,12779   ,298.4,302.6,298.9
XS GIS Cut Line= 4
2456546.10777378611950.1236718042456476.06707808612051.112581894
2456350.64536716612248.2038419072456269.20269773612362.223579104
#Sta/Elev= 30
       0 1951.69    12.9 1946.47    25.3 1942.74      74  1931.2    86.3 1923.17
    89.2 1921.79   112.9  1921.7  125.93 1920.46   132.4 1919.26   136.9 1917.21
  153.711903.483   155.8 1902.03   160.6 1900.37     170 1899.69   175.9 1900.54
   184.3 1903.99   201.9 1904.66   217.5 1902.47   239.6 1903.55   254.1  1905.1
   307.5 1904.16   312.3 1904.56   321.8 1907.09     334 1907.42  370.841912.108
     377 1913.56   390.8 1918.29   404.1  1924.1   435.8 1939.99   496.6 1973.12
#Mann= 5 ,-1 , 0
       0    .055       0  125.93      .1       0  153.71    .045       0
   184.3      .1       0  370.84      .1       0
Bank Sta=153.71,184.3
XS Rating Curve= 0 ,0
Exp/Cntr(USF)=0,0
Exp/Cntr=0.3,0.1

Type RM Length L Ch R = 1 ,12477   ,117.7,116.9,112.7
XS GIS Cut Line= 4
2456335.98568666611845.8770549382456277.34696468611941.979404862
2456221.96594947612064.143409002 2456132.3790131612227.028747856
#Sta/Elev= 30
       0 1926.05    19.1 1922.36    48.5  1914.3    56.9 1913.56    74.4 1914.64
    92.21914.083     109 1912.13   122.4 1907.33   133.4 1905.69   135.5  1904.9
   144.3 1898.66   148.5 1897.64  164.071899.237   175.1 1898.73   183.8 1899.31
   193.8 1898.58   208.9  1901.4   232.2 1901.72   251.1 1900.67  265.931898.309
  285.871895.247     313 1891.32   319.51895.245   322.9 1898.24     332 1908.69
   341.1 1917.23   351.2    1925     363 1932.93   382.2 1943.65   432.6 1968.69
#Mann= 6 ,-1 , 0
       0    .055       0    92.2     .06       0  164.07      .1       0
  265.93      .1       0  285.87    .045       0   319.5      .1       0
#XS Ineff= 2 , 0
          222.45 1901.97
Permanent Ineff=
       F       F
Bank Sta=285.87,319.5
XS Rating Curve= 0 ,0
Exp/Cntr(USF)=0,0
Exp/Cntr=0.3,0.1

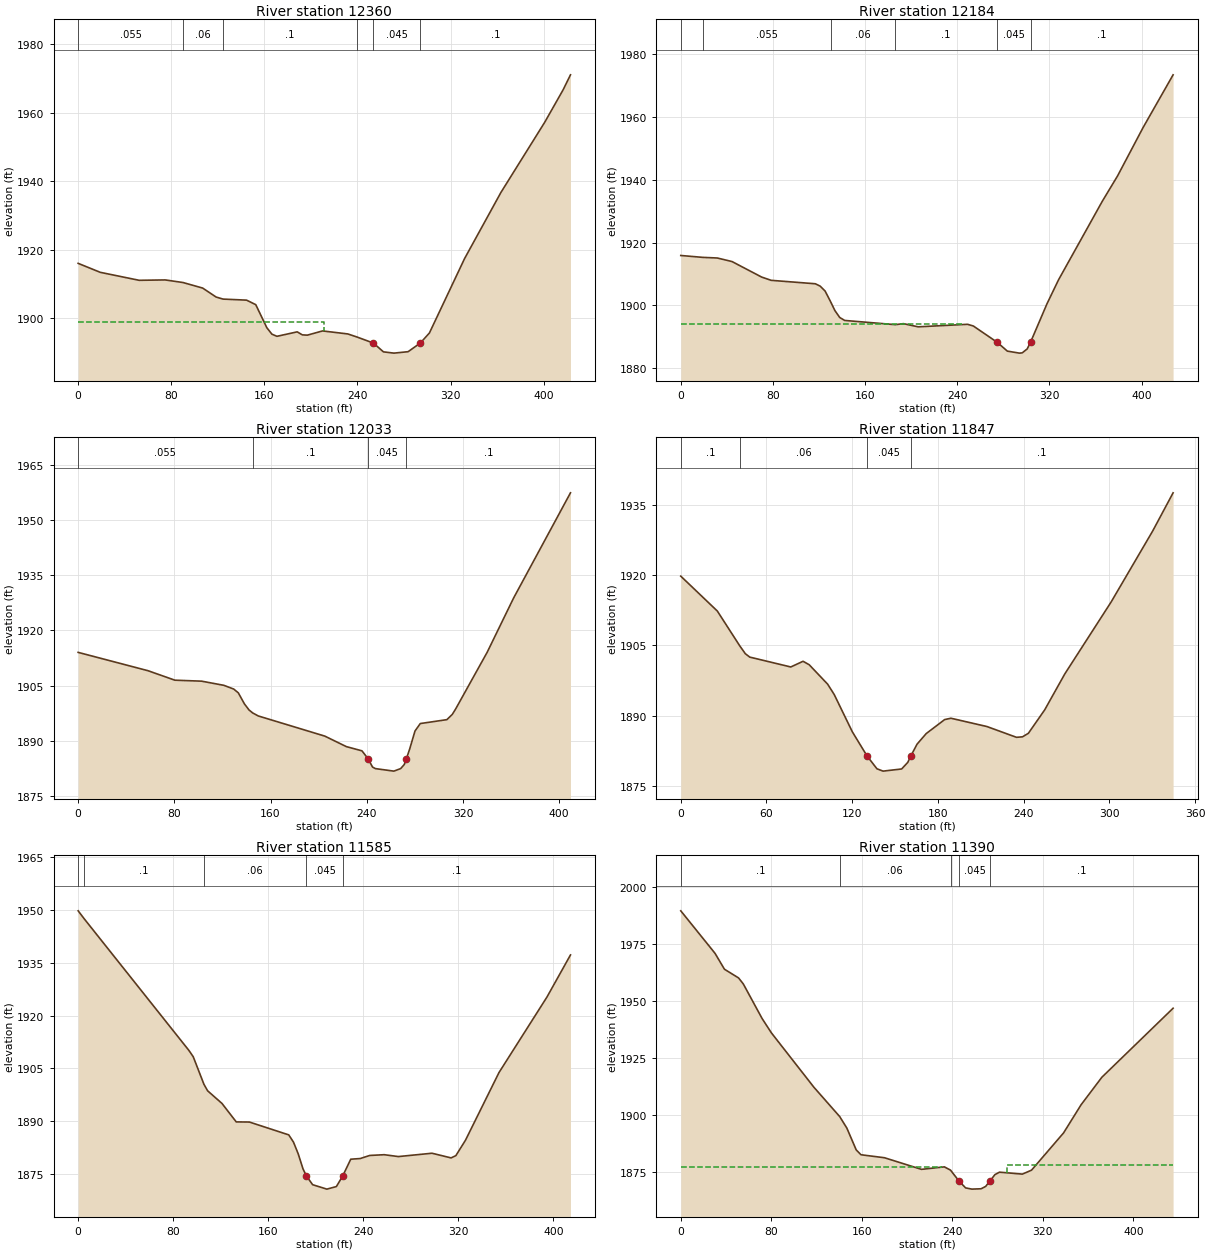
Type RM Length L Ch R = 1 ,12360   ,176.1,175.7,174.8
XS GIS Cut Line= 4
2456215.45053591611790.4960397282456164.95608087611904.515776925
2456085.14226483612090.2050632192456042.79207673612176.534292811
#Sta/Elev= 30
       0 1916.02      19  1913.4    52.4 1911.07    74.8 1911.18   90.111910.421
     107  1908.8   118.5 1906.19  124.481905.585   144.7 1905.28   152.6 1903.96
   162.1 1897.23   166.5 1895.34   170.8 1894.72   188.2 1896.02   192.6 1895.14
   196.9 1895.06     210 1896.29   231.7 1895.41   239.6 1894.51  253.641892.754
   262.3 1890.18   271.3 1889.81   283.5 1890.23  293.981892.754   301.8 1895.69
     332 1917.41   363.2  1936.7   400.9 1957.23   416.7  1966.7     423 1971.06
#Mann= 6 ,-1 , 0
       0    .055       0   90.11     .06       0  124.48      .1       0
   239.6      .1       0  253.64    .045       0  293.98      .1       0
#XS Ineff= 2 , 0
          211.54 1898.78
Permanent Ineff=
       F       F
Bank Sta=253.64,293.98
XS Rating Curve= 0 ,0
Exp/Cntr(USF)=0,0
Exp/Cntr=0.3,0.1

Type RM Length L Ch R = 1 ,12184   ,150.5,151.5,151.7
XS GIS Cut Line= 4
2456042.79207673611709.0533703012455971.12252763611907.773483702
2455923.88577936612026.6797810662455886.42215143612106.493597104
#Sta/Elev= 30
       0 1915.88   18.971915.284    31.7 1915.08    44.5 1913.95    70.2 1909.02
    78.5 1907.98   116.8 1906.89     121 1906.14   125.3 1904.58  130.121901.151
   133.8 1898.37     138 1896.17   142.3 1895.23   186.31893.888   193.3 1894.21
   206.1  1893.2     249    1894     254 1893.46  274.631888.302   283.5 1885.48
     294 1884.84   296.4 1884.92   300.7 1886.16  303.64  1888.3   317.9 1900.51
   327.9 1908.11   365.9 1933.09   379.2 1941.18   401.3 1956.52   427.4 1973.31
#Mann= 6 ,-1 , 0
       0      .1       0   18.97    .055       0  130.12     .06       0
   186.3      .1       0  274.63    .045       0  303.64      .1       0
#XS Ineff= 2 , 0
          245.97 1894.19
Permanent Ineff=
       F       F
Bank Sta=274.63,303.64
XS Rating Curve= 0 ,0
Exp/Cntr(USF)=0,0
Exp/Cntr=0.3,0.1

Type RM Length L Ch R = 1 ,12033   ,184.6,185.4,183.6
XS GIS Cut Line= 4
2455928.77233953611666.7031821992455840.81425655611845.877054938
2455796.83521506611940.3505514732455749.59846679612034.824048008
#Sta/Elev= 30
       0 1914.03    58.1 1909.05    80.4 1906.48   102.7 1906.21   121.2 1905.08
   129.4 1904.06   133.2 1903.03   138.3 1900.02   142.1 1898.39  145.13 1897.58
   149.8 1896.76   205.1 1891.29     223 1888.44     236 1887.29  240.991885.184
   244.8 1882.89   247.1 1882.47   262.5 1881.78   268.2 1882.47   271.2 1883.58
     273 1885.19   275.7 1887.81   280.1 1892.67   284.5  1894.7   306.6 1895.76
   311.1 1897.18   313.8  1898.6   340.1 1914.04   362.1 1928.79   409.4 1957.36
#Mann= 4 ,-1 , 0
       0    .055       0  145.13      .1       0  240.99    .045       0
     273      .1       0
Bank Sta=240.99,273
XS Rating Curve= 0 ,0
Exp/Cntr(USF)=0,0
Exp/Cntr=0.3,0.1

Type RM Length L Ch R = 1 ,11847   ,269.2,262.5,256.1
XS GIS Cut Line= 4
 2455733.3099329611639.0126745942455700.73286513611723.713050797
2455660.01153042611824.7019608872455622.54790248611964.783352301
#Sta/Elev= 30
       0 1919.75    25.6 1912.31   41.311904.888    45.2 1903.22    48.3  1902.5
      77  1900.4    85.6 1901.61    89.9 1900.87   102.8 1896.74   107.4 1894.53
   120.1 1886.58   130.41881.431   137.3 1878.71   141.6 1878.21   154.6 1878.67
   158.9 1880.08     1611881.429   165.4 1883.96   171.8 1886.21   184.7 1889.19
   189.1 1889.48   214.3 1887.71     235 1885.41   239.2 1885.52   243.3 1886.27
   254.7 1891.25   268.8 1898.92   301.3 1914.28   330.3 1929.36   344.6  1937.5
#Mann= 4 ,-1 , 0
       0      .1       0   41.31     .06       0   130.4    .045       0
     161      .1       0
#XS Ineff= 2 , 0
                          190.05         1889.26
Permanent Ineff=
       F       F
Bank Sta=130.4,161
XS Rating Curve= 0 ,0
Exp/Cntr(USF)=0,0
Exp/Cntr=0.3,0.1

Type RM Length L Ch R = 1 ,11585   ,197.1,195.2,194.2
XS GIS Cut Line= 4
2455440.11632297611518.4775238422455425.45664247611658.558915256
 2455435.2297628611779.0940660082455454.77600346611930.577431142
#Sta/Elev= 30
       0 1949.81    5.04 1947.57    93.3 1910.08    96.9  1908.3  105.921900.453
     109 1898.62   121.1 1895.02   133.1 1889.77   144.2 1889.73   177.3 1886.08
   181.3 1884.02   185.3 1880.66   189.3 1876.41   192.21874.387   197.4 1871.91
   209.4 1870.65   217.4 1871.38  222.731874.388   229.5 1879.16   237.5 1879.35
   245.5 1880.23   257.7 1880.44   269.6 1879.91   297.9 1880.86     314 1879.53
     318 1880.18   326.1 1884.56   354.3  1903.8   394.7 1925.29   414.5 1937.26
#Mann= 5 ,-1 , 0
       0      .1       0    5.04      .1       0  105.92     .06       0
   192.2    .045       0  222.73      .1       0
Bank Sta=192.2,222.73
XS Rating Curve= 0 ,0
Exp/Cntr(USF)=0,0
Exp/Cntr=0.3,0.1

Type RM Length L Ch R = 1 ,11390   ,182.7,179.5,176.2
XS GIS Cut Line= 4
2455177.87092741611521.7352306192455229.99423585611704.166810135
2455254.42703667611850.7636151032455275.60213072611945.237111639
#Sta/Elev= 30
       0  1989.7    30.3 1971.01    38.6 1964.04    51.1  1960.2    55.3 1957.55
    71.9 1942.36    80.2 1936.01   117.7 1912.16  140.511899.268   146.8 1894.22
   155.1 1884.62   159.3  1882.5   180.1 1881.18   212.8 1876.08     233 1877.17
  238.431875.747  246.191870.792   251.8 1867.93   257.4 1867.39   265.5 1867.55
   269.5 1868.58  273.02 1870.79   277.7 1873.76   281.7 1874.84     302 1873.99
   310.1 1875.74   338.4 1892.11   353.9 1904.49   372.2 1916.54   435.2 1946.89
#Mann= 5 ,-1 , 0
       0      .1       0  140.51     .06       0  238.43      .1       0
  246.19    .045       0  273.02      .1       0
#XS Ineff= 2 , 0
          231.18  1877.2  288.46         1877.95
Permanent Ineff=
       F       F
Bank Sta=246.19,273.02
XS Rating Curve= 0 ,0
Exp/Cntr(USF)=0,0
Exp/Cntr=0.3,0.1

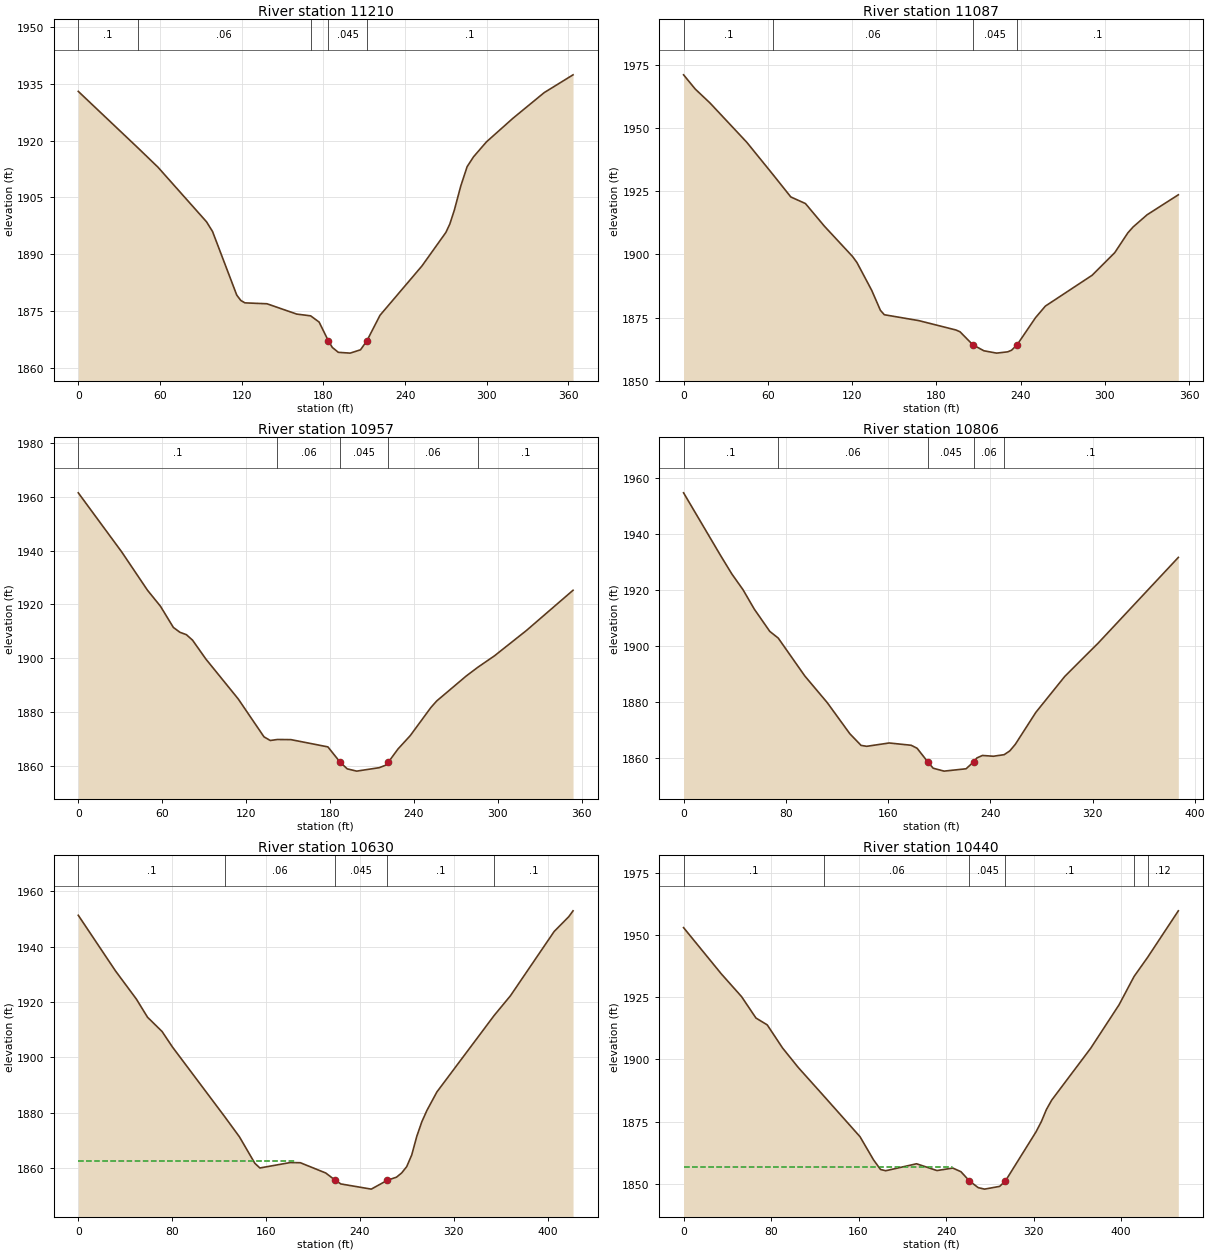
Type RM Length L Ch R = 1 ,11210   ,128.5,123.5,120.2
XS GIS Cut Line= 4
2454987.29508095611650.4146483132455044.30494955611766.063238899
2455091.54169782611873.5675625432455153.43812658611972.927619244
#Sta/Elev= 30
       0 1933.01   43.521918.197    58.5 1913.01    94.2 1898.58    98.6 1896.03
   116.4 1879.23   119.4 1877.81   122.4 1877.18   138.6 1876.94   160.4 1874.22
  170.671873.752   176.9 1872.11  183.651867.181   186.6 1865.41     191 1864.12
   199.7 1863.91   207.3 1864.79  212.021867.183   221.6 1873.89   252.4 1886.91
     270 1895.77   272.9    1898   276.2 1901.64   280.9 1907.98   285.6 1913.13
   290.3 1915.73   299.8 1919.68   319.3 1925.92   342.2 1932.68   363.4 1937.38
#Mann= 5 ,-1 , 0
       0      .1       0   43.52     .06       0  170.67      .1       0
  183.65    .045       0  212.02      .1       0
Bank Sta=183.65,212.02
XS Rating Curve= 0 ,0
Exp/Cntr(USF)=0,0
Exp/Cntr=0.3,0.1

Type RM Length L Ch R = 1 ,11087   ,135.1,129.2,125.1
XS GIS Cut Line= 4
 2454824.4097421611767.6920922882454940.05833269  611865.4232956
2455019.87214872 611955.010231972455089.91284443611995.731566683
#Sta/Elev= 30
       0 1971.02     8.3  1965.4    18.8  1959.9      45 1944.36    63.81931.494
    76.4 1922.72    86.8 1920.12   100.4 1911.11   120.3 1899.21   123.5 1896.79
     134  1885.8   140.2  1877.9     143 1876.15   167.5 1873.83     194 1870.12
   196.9 1869.41  206.021864.273   213.9  1861.9     223 1860.97   230.9 1861.49
   233.6 1862.11  237.581864.275   250.7 1875.01   257.7 1879.57     291 1891.76
   307.1 1900.69   316.4  1908.5   320.2 1910.87   330.2  1915.7   352.4 1923.58
#Mann= 4 ,-1 , 0
       0      .1       0    63.8     .06       0  206.02    .045       0
  237.58      .1       0
Bank Sta=206.02,237.58
XS Rating Curve= 0 ,0
Exp/Cntr(USF)=0,0
Exp/Cntr=0.3,0.1

Type RM Length L Ch R = 1 ,10957   ,152,150.9,146.9
XS GIS Cut Line= 4
2454755.99789978611933.8351379192454861.87337004611995.731566683
2454979.15081401612060.8857022252455063.85119021612108.122450492
#Sta/Elev= 30
       0 1961.55      31  1939.6    49.5  1925.3    58.8 1919.32      68 1911.45
    72.7 1909.65    77.3 1908.76    81.7 1906.73    91.2 1899.72   114.4 1884.83
   132.8 1870.74   137.3 1869.38  142.421869.756   152.1  1869.7   178.5    1867
  187.251861.315   192.3 1858.83   199.1 1857.98   215.2 1859.26   219.7 1860.16
  221.731861.317   228.6  1866.2   237.4  1871.2   252.1 1881.62   256.3 1884.09
   277.3 1893.33  285.671896.616   297.6 1900.88   320.5 1910.33   353.8 1925.29
#Mann= 5 ,-1 , 0
       0      .1       0  142.42     .06       0  187.25    .045       0
  221.73     .06       0  285.67      .1       0
Bank Sta=187.25,221.73
XS Rating Curve= 0 ,0
Exp/Cntr(USF)=0,0
Exp/Cntr=0.3,0.1

Type RM Length L Ch R = 1 ,10806   ,173,176.2,175.3
XS GIS Cut Line= 4
2454692.47261763612091.8339166072454842.32712937612160.245758926
2454961.23342674612205.8536538052455047.56265633612244.946135129
#Sta/Elev= 30
       0 1954.81    28.9 1932.44    37.7 1925.85    46.5 1920.17    55.3 1913.25
    67.4  1905.3   74.031902.894    94.8 1889.36   112.4  1879.8     130 1868.72
   138.8 1864.55   143.2 1864.22   160.8 1865.41     178 1864.59   182.6 1863.53
   190.9  1858.7   195.2 1856.39   203.7 1855.35   220.9 1856.19  226.931858.699
   229.4 1860.07   233.7 1860.95   242.3 1860.67  250.681861.231   255.1 1862.58
   259.4 1864.92   275.5 1876.37   298.1  1889.2   324.5 1901.24   386.9 1931.73
#Mann= 5 ,-1 , 0
       0      .1       0   74.03     .06       0   190.9    .045       0
  226.93     .06       0  250.68      .1       0
Bank Sta=190.9,226.93
XS Rating Curve= 0 ,0
Exp/Cntr(USF)=0,0
Exp/Cntr=0.3,0.1

Type RM Length L Ch R = 1 ,10630   ,186,190.3,192.5
XS GIS Cut Line= 4
 2454625.6896287612249.8326952952454762.51331333 612311.72912406
2454904.22355814612368.7389926582455018.24329534612401.316060429
#Sta/Elev= 30
       0 1951.28    31.7 1931.19    49.5 1921.01      59 1914.46    71.4  1909.3
    80.2 1903.72  124.591878.629   137.3 1871.26   150.4 1861.72   154.7 1860.01
   180.6 1861.97   189.2  1861.9   210.8  1858.2  219.081855.537   223.7 1854.24
   249.6 1852.37  263.151855.538   271.1 1856.69   275.5 1858.21   279.8  1860.5
   284.1 1864.74   288.4 1871.46   292.7 1876.72     297 1880.78   305.5 1887.46
  354.351915.119   368.2 1922.23   405.4 1945.42   417.9 1950.79   421.5 1952.89
#Mann= 5 ,-1 , 0
       0      .1       0  124.59     .06       0  219.08    .045       0
  263.15      .1       0  354.35      .1       0
#XS Ineff= 2 , 0
          184.81 1862.63
Permanent Ineff=
       F       F
Bank Sta=219.08,263.15
XS Rating Curve= 0 ,0
Exp/Cntr(USF)=0,0
Exp/Cntr=0.3,0.1

Type RM Length L Ch R = 1 ,10440   ,165.3,168.6,171.1
XS GIS Cut Line= 4
2454537.73154572612368.7389926582454726.67853879612486.016436633
2454817.89432854 612544.655158622454920.51209202612609.809294162
#Sta/Elev= 30
       0 1952.91    34.4  1934.4      53 1925.22    66.2 1916.61    76.5 1913.86
    90.6 1904.53   104.8 1896.79  128.071885.387   161.3 1868.98   173.7 1859.66
   180.1  1855.8   184.8 1855.29     213 1858.09   231.7 1855.37   246.2 1856.37
   253.6 1854.91  261.441851.181   269.4 1848.51   275.2 1847.91     289 1849.01
  294.27 1851.18   322.3 1870.93   327.1 1874.99   331.8 1879.91   336.6 1883.65
   372.3 1904.51   398.2 1921.93   411.91933.287  424.371941.018   452.4 1959.66
#Mann= 6 ,-1 , 0
       0      .1       0  128.07     .06       0  261.44    .045       0
  294.27      .1       0   411.9      .1       0  424.37     .12       0
#XS Ineff= 2 , 0
           245.3 1856.82
Permanent Ineff=
       F       F
Bank Sta=261.44,294.27
XS Rating Curve= 0 ,0
Exp/Cntr(USF)=0,0
Exp/Cntr=0.3,0.1

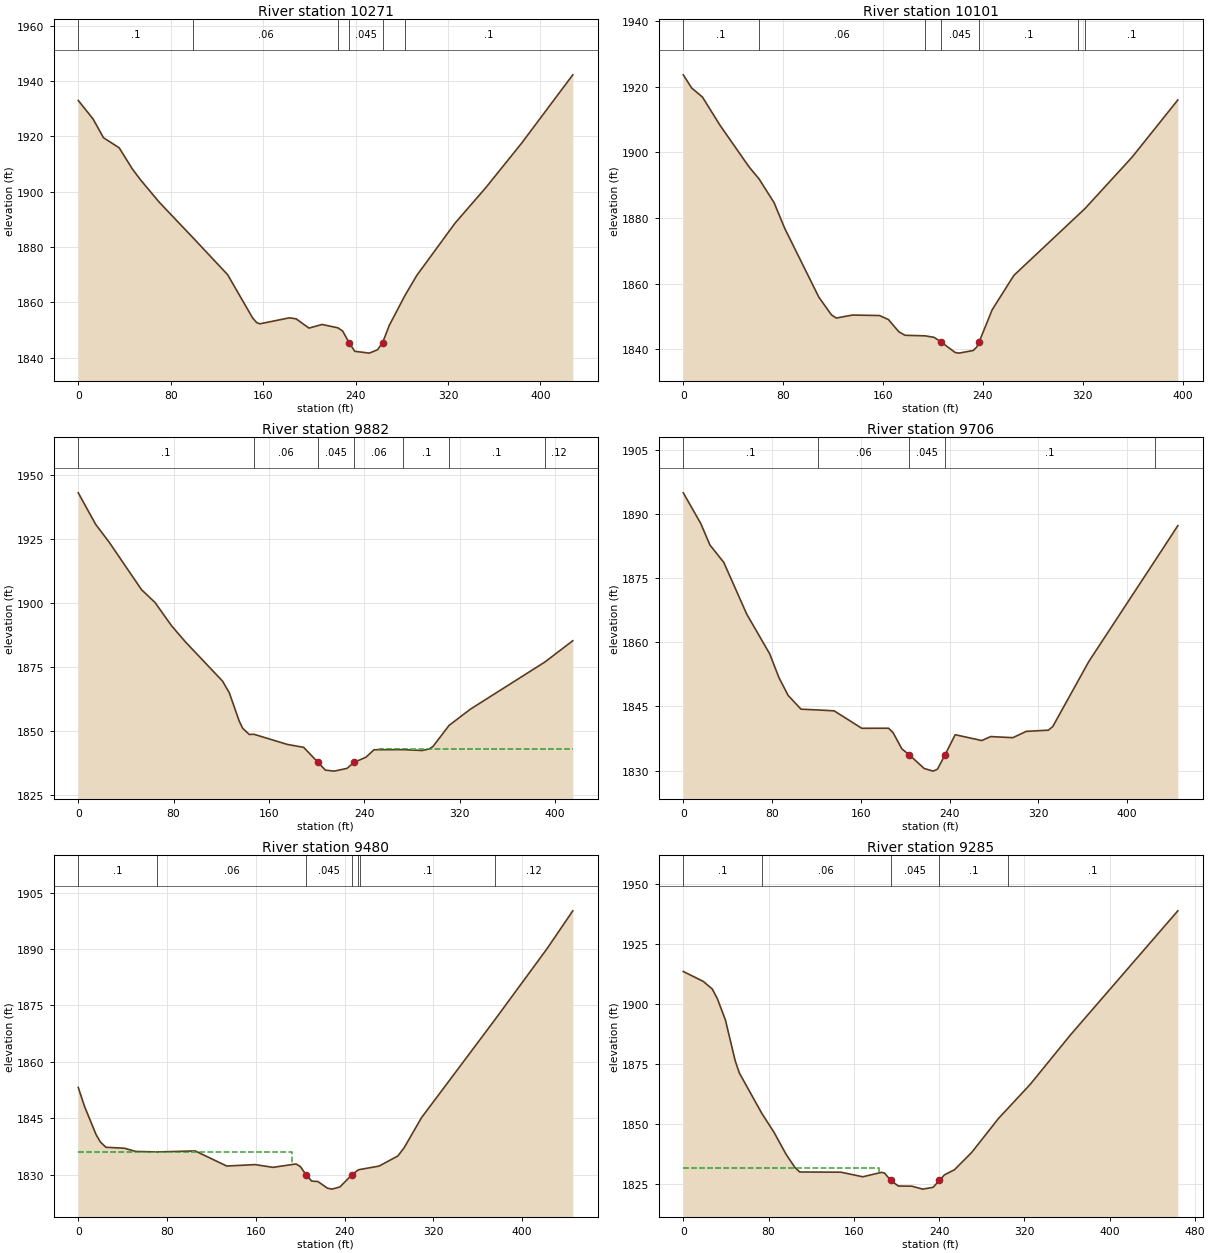
Type RM Length L Ch R = 1 ,10271   ,170.7,170.6,170.5
XS GIS Cut Line= 4
2454490.49479745612481.1298764672454633.83389564612609.809294162
2454716.90541846  612689.62311022454808.12120821 612767.80807285
#Sta/Elev= 30
       0 1932.97    12.8 1926.28    21.8  1919.5    35.4 1915.85    46.7 1908.27
    54.1 1904.15    70.2 1896.12   99.651883.171   129.3 1869.95   150.8 1854.39
   154.4 1852.64   157.2  1852.2   182.7 1854.36   188.5 1854.01   199.7 1850.65
     211 1851.96  224.74 1850.75   228.8 1849.59  234.521845.336   239.3 1842.26
   251.9  1841.6   259.1 1842.84  263.36 1845.34   269.2 1851.65  282.641862.362
     293 1869.71   326.1  1888.6   352.6 1901.37   383.8 1917.56     428 1942.23
#Mann= 6 ,-1 , 0
       0      .1       0   99.65     .06       0  224.74      .1       0
  234.52    .045       0  263.36      .1       0  282.64      .1       0
Bank Sta=234.52,263.36
XS Rating Curve= 0 ,0
Exp/Cntr(USF)=0,0
Exp/Cntr=0.3,0.1

Type RM Length L Ch R = 1 ,10101   ,222.7,218.7,214.9
XS GIS Cut Line= 4
2454379.73276703612632.6132416012454493.75250423 612712.42705764
2454588.22600076612802.0139940092454677.81293713612891.600930379
#Sta/Elev= 30
       0 1923.59     6.7 1919.58    15.3 1916.84    29.6 1908.13    52.6  1895.6
   60.661891.915    72.7 1884.69    81.3 1876.81   108.6 1855.89   118.7 1850.51
   122.5 1849.55   135.5 1850.46   157.1 1850.32   164.3 1849.09   172.7 1845.35
   177.6  1844.3  193.731844.135   200.9 1843.67  206.511842.255   217.7 1839.08
   220.8 1838.87   232.2 1839.67     235 1840.71  236.931842.257   247.4 1852.07
   264.8 1862.54  316.041880.838  321.631882.825   359.5 1898.54   396.1 1915.93
#Mann= 7 ,-1 , 0
       0      .1       0   60.66     .06       0  193.73      .1       0
  206.51    .045       0  236.93      .1       0  316.04     .12       0
  321.63      .1       0
Bank Sta=206.51,236.93
XS Rating Curve= 0 ,0
Exp/Cntr(USF)=0,0
Exp/Cntr=0.3,0.1

Type RM Length L Ch R = 1 ,9882    ,184.2,175.8,168.4
XS GIS Cut Line= 4
2454221.73398834612780.8388999582454321.09404504612875.312396494
2454453.03116951612946.9819455892454570.30861349612997.476400634
#Sta/Elev= 30
       0 1943.07    14.6 1930.74    26.2 1923.58    53.1 1905.17    64.4 1900.17
    78.4 1890.99    89.9 1884.76     121 1869.44   126.7 1864.88   135.1 1853.69
     138 1850.93   143.5 1848.54  147.261848.633   175.4 1844.65   189.1 1843.51
  201.171837.625   207.3  1834.6   214.7  1834.2   225.5 1835.28  231.441837.627
   241.3 1839.63   248.2 1842.57  272.811842.605   288.5 1842.27   294.6 1842.89
   297.6 1843.85  311.141852.102   328.9 1858.41  391.471876.875   414.9 1885.21
#Mann= 7 ,-1 , 0
       0      .1       0  147.26     .06       0  201.17    .045       0
  231.44     .06       0  272.81      .1       0  311.14      .1       0
  391.47     .12       0
#XS Ineff= 2 , 0
                          252.02         1843.01
Permanent Ineff=
       F       F
Bank Sta=201.17,231.44
XS Rating Curve= 0 ,0
Exp/Cntr(USF)=0,0
Exp/Cntr=0.3,0.1

Type RM Length L Ch R = 1 ,9706    ,239.7,226,213.9
XS GIS Cut Line= 4
2454143.54902569613039.8265887362454304.80551116613083.805630226
 2454469.3197034613080.5479234492454581.71058721613061.001682787
#Sta/Elev= 30
       0 1895.01    15.8  1887.8      24  1882.8    36.5 1878.73    57.2 1866.61
    77.9 1857.32    86.2 1851.77    94.5  1847.6   106.1 1844.37  121.18 1844.19
     136 1843.98   160.9  1839.9   185.1 1839.91   189.1 1838.88   197.1 1835.06
  203.631833.706   217.1  1830.5   225.1 1829.87   229.1 1830.31  235.991833.704
   245.1 1838.39   269.1 1837.03   277.1 1837.96   297.1  1837.7   309.1 1839.17
   329.1 1839.46   333.1 1840.32   365.6 1855.54  424.891879.007   445.8 1887.32
#Mann= 5 ,-1 , 0
       0      .1       0  121.18     .06       0  203.63    .045       0
  235.99      .1       0  424.89     .12       0
Bank Sta=203.63,235.99
XS Rating Curve= 0 ,0
Exp/Cntr(USF)=0,0
Exp/Cntr=0.3,0.1

Type RM Length L Ch R = 1 ,9480    ,197.5,194.9,192.6
XS GIS Cut Line= 4
 2454298.2900976  613414.46286812454428.59836869613310.216251233
2454545.87581266613194.5676606472454627.31848209613114.753844609
#Sta/Elev= 30
       0 1853.19     5.7 1848.12      16  1840.7    19.9 1838.72    24.9  1837.3
    41.6 1837.04    51.8 1836.19   71.081836.048   105.3 1836.33   133.8 1832.31
   159.4 1832.69   175.5 1831.96   196.2 1832.86   200.1 1832.18  205.421829.923
   210.3 1828.32     216 1828.18   224.5 1826.43   228.6 1826.17   235.8 1826.76
  246.391829.922  252.211831.265  253.761831.389     271 1832.29   287.9 1834.97
   293.5  1837.1   309.3 1845.17  375.491871.235   422.6 1890.18   445.6 1900.16
#Mann= 7 ,-1 , 0
       0      .1       0   71.08     .06       0  205.42    .045       0
  246.39     .06       0  252.21      .1       0  253.76      .1       0
  375.49     .12       0
#XS Ineff= 2 , 0
          192.93 1835.94
Permanent Ineff=
       F       F
Bank Sta=205.42,246.39
XS Rating Curve= 0 ,0
Exp/Cntr(USF)=0,0
Exp/Cntr=0.3,0.1

Type RM Length L Ch R = 1 ,9285    ,232,236.6,243.8
XS GIS Cut Line= 4
2454479.09282373613549.6576993482454570.30861349613456.813056202
2454669.66867019613331.3913452842454772.28643367 613191.30995387
#Sta/Elev= 30
       0 1913.46    18.7 1909.34    27.2 1906.14    31.9 1902.18    39.5 1893.28
    48.7 1876.25    52.6 1871.17   73.591854.427    85.1 1846.49    96.5 1837.27
   104.8  1831.8   109.2 1829.98   147.9 1829.89   168.3 1827.98   185.9 1829.82
   188.8  1829.5  194.461826.501   201.7 1824.13   214.3 1824.07   224.5 1822.84
   234.3 1823.59  240.24  1826.5   244.9 1828.77   254.3 1830.91   270.4 1838.08
   295.7 1852.31  304.71  1856.6   325.5 1866.53   362.8 1886.88   463.8 1938.71
#Mann= 5 ,-1 , 0
       0      .1       0   73.59     .06       0  194.46    .045       0
  240.24      .1       0  304.71      .1       0
#XS Ineff= 2 , 0
          183.62 1831.73
Permanent Ineff=
       F       F
Bank Sta=194.46,240.24
XS Rating Curve= 0 ,0
Exp/Cntr(USF)=0,0
Exp/Cntr=0.3,0.1