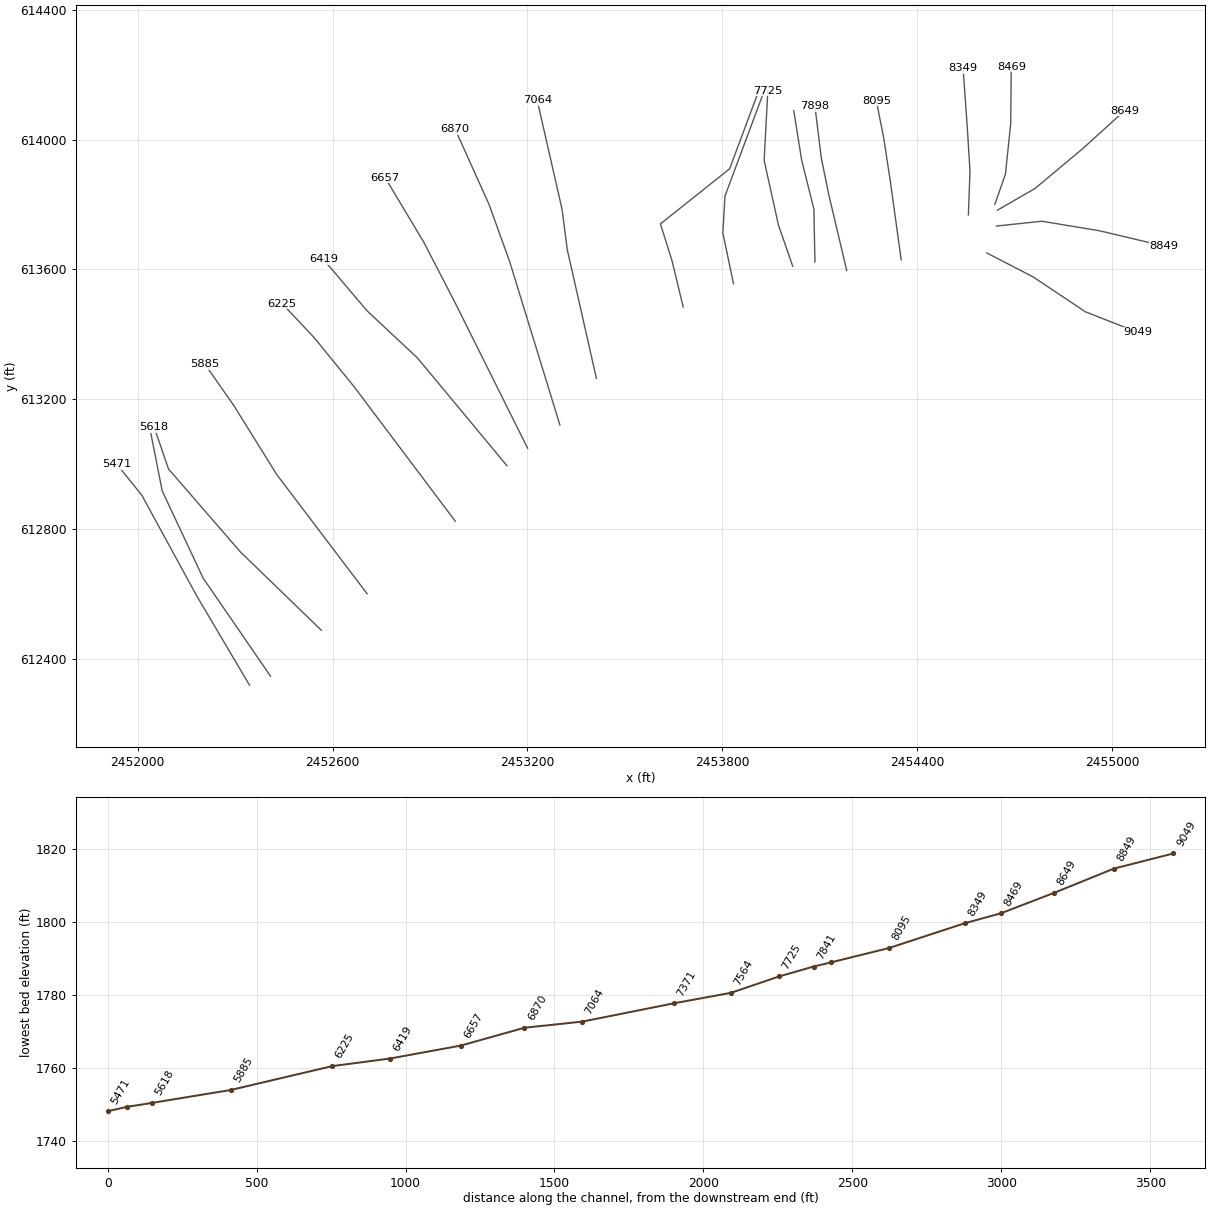
HEC-RAS study TROUTRN.prj: TROUTRN

--- TROUTRN.g01 (geometry) --- (continued)

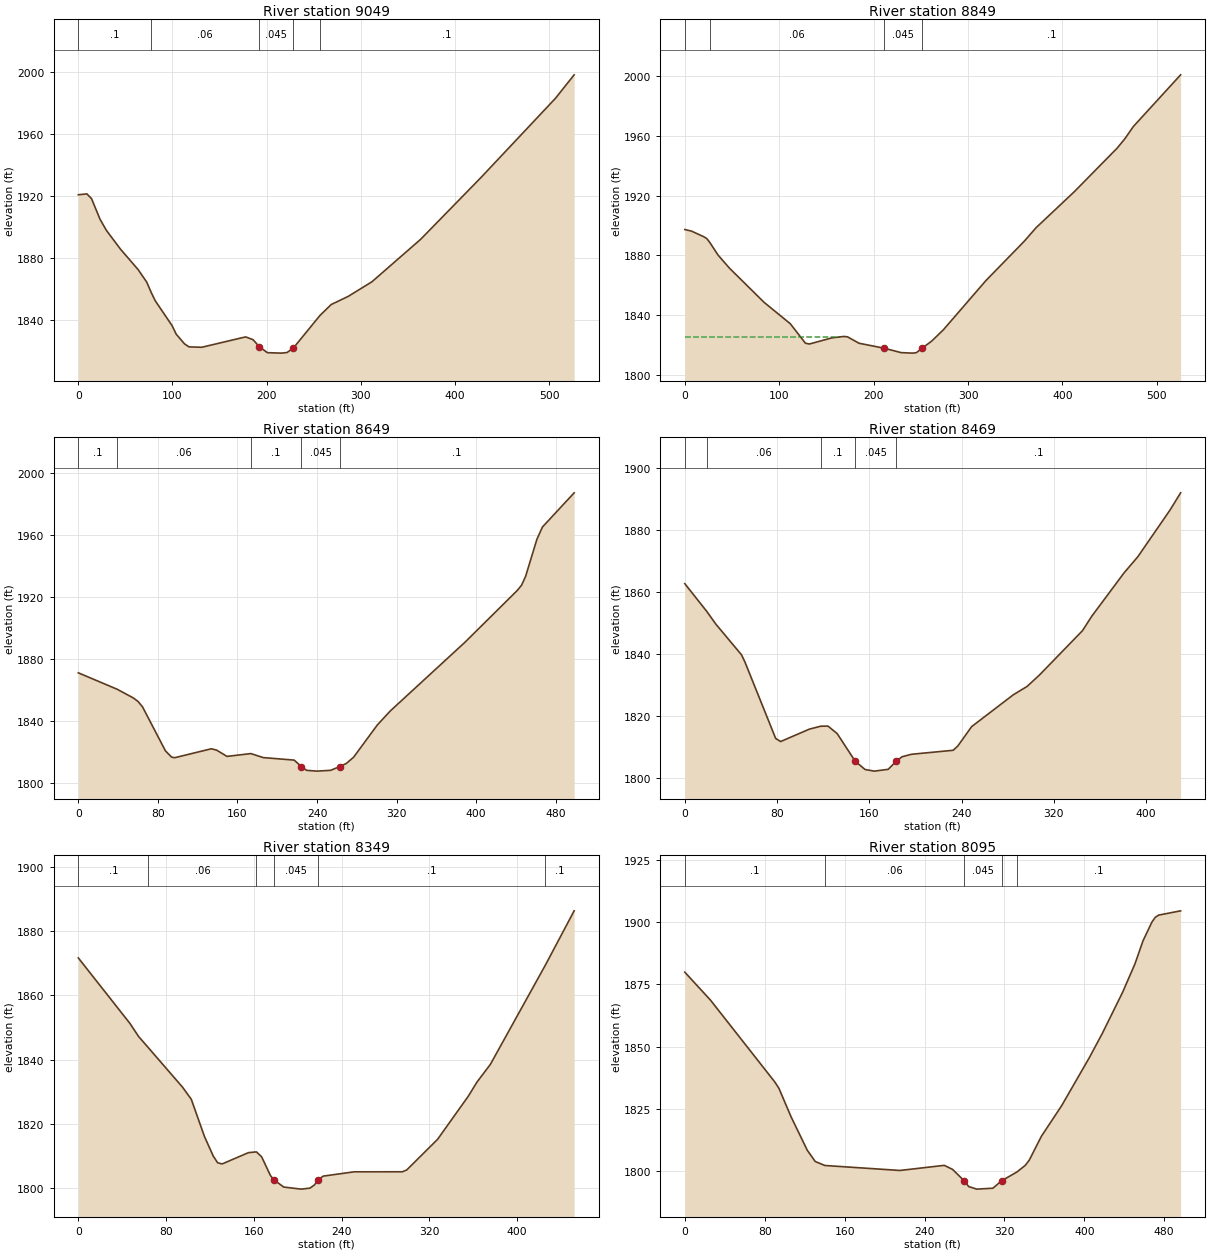
Type RM Length L Ch R = 1 ,9049    ,192.2,200.2,208.4
XS GIS Cut Line= 4
2454614.28765498613650.6466094382454755.99789978613577.348206953
2454917.25438525 613469.843883312455078.51087071613406.318601157
#Sta/Elev= 30
       0 1920.96     9.1 1921.52      14 1918.49      23 1905.22    29.8 1897.99
    44.7  1885.9    63.6 1872.58    72.6  1864.6   77.59 1857.66    81.6 1852.62
    99.6 1836.44     104 1830.92   112.9 1824.62   117.6 1822.74   131.1 1822.48
   177.7 1829.18   185.6 1827.38   192.1 1822.94   200.8    1819   215.7  1818.7
   221.7 1819.09  228.511822.037  256.631842.994   268.6 1850.07   286.6 1855.31
   311.9 1864.78   363.6 1892.17   427.7 1932.08   506.8 1983.21   526.7  1998.4
#Mann= 5 ,-1 , 0
       0      .1       0   77.59     .06       0   192.1    .045       0
  228.51     .06       0  256.63      .1       0
#XS Ineff= 2 , 0
          175.81 1828.37
Permanent Ineff=
       F       F
Bank Sta=192.1,228.51
XS Rating Curve= 0 ,0
Exp/Cntr(USF)=0,0
Exp/Cntr=0.3,0.1

Type RM Length L Ch R = 1 ,8849    ,181.6,199.9,215
XS GIS Cut Line= 4
2454643.60701597613733.7181322532454783.68840739 613748.37781275
2454961.23342674613719.0584517562455159.95354014613671.821703488
#Sta/Elev= 30
       0 1897.31     7.2 1896.22    20.2 1892.45    23.3 1891.24   26.62 1888.52
    35.3 1880.14    47.4 1871.37      84 1848.54   111.7 1834.25   127.8 1821.17
   131.9 1820.66   156.1 1824.81   168.3  1825.7   172.3 1825.47   184.5 1821.17
  211.18 1817.83   229.1 1814.89   241.2 1814.55   245.3 1814.86  251.29 1817.83
   261.5 1822.62   273.9  1830.2   318.8 1863.06   359.4 1889.39     372 1898.51
   412.8 1922.79     458 1951.88   466.3 1958.26     475 1966.23   525.1 2000.87
#Mann= 4 ,-1 , 0
       0      .1       0   26.62     .06       0  211.18    .045       0
  251.29      .1       0
#XS Ineff= 2 , 0
          164.52 1825.52
Permanent Ineff=
       F       F
Bank Sta=211.18,251.29
XS Rating Curve= 0 ,0
Exp/Cntr(USF)=0,0
Exp/Cntr=0.3,0.1

Type RM Length L Ch R = 1 ,8649    ,163.9,179.4,193.2
XS GIS Cut Line= 4
2454646.86472275613782.5837339092454762.51331334613849.366722839
2454910.73897169613973.159580368  2455037.789536614088.808170954
#Sta/Elev= 30
       0 1871.17   39.111860.592    55.3 1855.01    59.9 1852.83    64.5 1849.33
    87.6 1820.97    93.8 1816.96    96.9 1816.57   133.8 1822.33   139.1 1821.42
   149.5 1817.41  173.461819.224   185.9 1816.65     217 1815.03  224.261810.854
   229.5 1808.45   239.9 1807.94   253.7 1808.45  262.681810.853   269.3  1812.8
   276.8 1816.91   300.6 1837.63   313.7 1846.68   388.7 1890.83   441.2 1924.08
   445.7  1927.6   449.7 1933.26     461 1956.97   466.6 1964.95   498.5 1986.95
#Mann= 5 ,-1 , 0
       0      .1       0   39.11     .06       0  173.46      .1       0
  224.26    .045       0  262.68      .1       0
Bank Sta=224.26,262.68
XS Rating Curve= 0 ,0
Exp/Cntr(USF)=0,0
Exp/Cntr=0.3,0.1

Type RM Length L Ch R = 1 ,8469    ,117,120.6,123.4
XS GIS Cut Line= 4
2454638.72045581613800.5011211832454671.29752358 613893.34576433
2454687.58605746614049.7156896292454689.21491085614224.003002203
#Sta/Elev= 30
       0 1862.64    18.91853.787      27 1849.59    49.2 1839.73    52.1 1837.48
    78.8 1812.84    83.1 1811.84     108 1815.83  117.791816.764   124.1 1816.82
   132.1 1814.41  147.751805.509   156.3 1802.84   164.3 1802.32   176.4  1802.9
  183.31 1805.51   188.4 1806.95   196.5 1807.74   232.7 1809.03   236.7 1810.39
   248.7 1816.64   284.8 1826.88   296.8 1829.58   307.5 1833.25   344.8 1847.51
   352.8 1852.13   380.8 1866.09   392.8 1871.31   420.8 1886.38   429.9 1891.87
#Mann= 5 ,-1 , 0
       0      .1       0    18.9     .06       0  117.79      .1       0
  147.75    .045       0  183.31      .1       0
Bank Sta=147.75,183.31
XS Rating Curve= 0 ,0
Exp/Cntr(USF)=0,0
Exp/Cntr=0.3,0.1

Type RM Length L Ch R = 1 ,8349    ,251.9,254.2,255.6
XS GIS Cut Line= 4
2454557.27778638613767.9240534122454562.16434655613903.118884661
 2454554.0200796614035.0560091322454540.98925249614219.116442037
#Sta/Elev= 30
       0 1871.67      47 1851.28      55 1847.16   63.721843.741      95 1831.39
     103 1827.61     115    1816     123 1809.92     127 1807.83   131.1 1807.47
   155.1 1810.99  162.38 1811.23   167.1  1809.7   175.1 1803.88   178.11802.583
   187.2 1800.27   203.2 1799.62   211.2 1799.94   215.2 1800.91  218.931802.585
   223.2 1803.67   251.3 1805.01   295.4 1805.03   299.4  1805.6   327.5 1815.14
   355.5 1828.58   363.5 1833.02   375.6 1838.49  425.641869.353     452 1886.35
#Mann= 6 ,-1 , 0
       0      .1       0   63.72     .06       0  162.38      .1       0
   178.1    .045       0  218.93      .1       0  425.64      .1       0
Bank Sta=178.1,218.93
XS Rating Curve= 0 ,0
Exp/Cntr(USF)=0,0
Exp/Cntr=0.3,0.1

Type RM Length L Ch R = 1 ,8095    ,196,196.7,197.9
XS GIS Cut Line= 4
2454350.41340603613629.4715153862454317.83633826613865.655256724
2454296.66124421 614004.107794752454273.85729677614119.756385336
#Sta/Elev= 30
       0 1879.92    25.7  1868.7    90.3 1835.75    94.3 1833.24   106.4 1821.87
   122.6 1808.46   130.6 1803.93  140.211802.329   215.4 1800.33   259.8 1802.38
     268 1800.78  279.781796.166   284.2 1793.88   292.3 1792.84   308.5 1793.21
  317.091796.165  332.371799.681   340.8 1802.35   344.9 1804.49     357 1814.04
   377.3 1826.34     405  1845.6     418 1855.33   438.4 1871.91   450.7 1883.27
   458.8 1892.55   467.6 1899.98     471 1901.91   474.4 1902.81   496.4 1904.53
#Mann= 5 ,-1 , 0
       0      .1       0  140.21     .06       0  279.78    .045       0
  317.09     .06       0  332.37      .1       0
Bank Sta=279.78,317.09
XS Rating Curve= 0 ,0
Exp/Cntr(USF)=0,0
Exp/Cntr=0.5,0.3

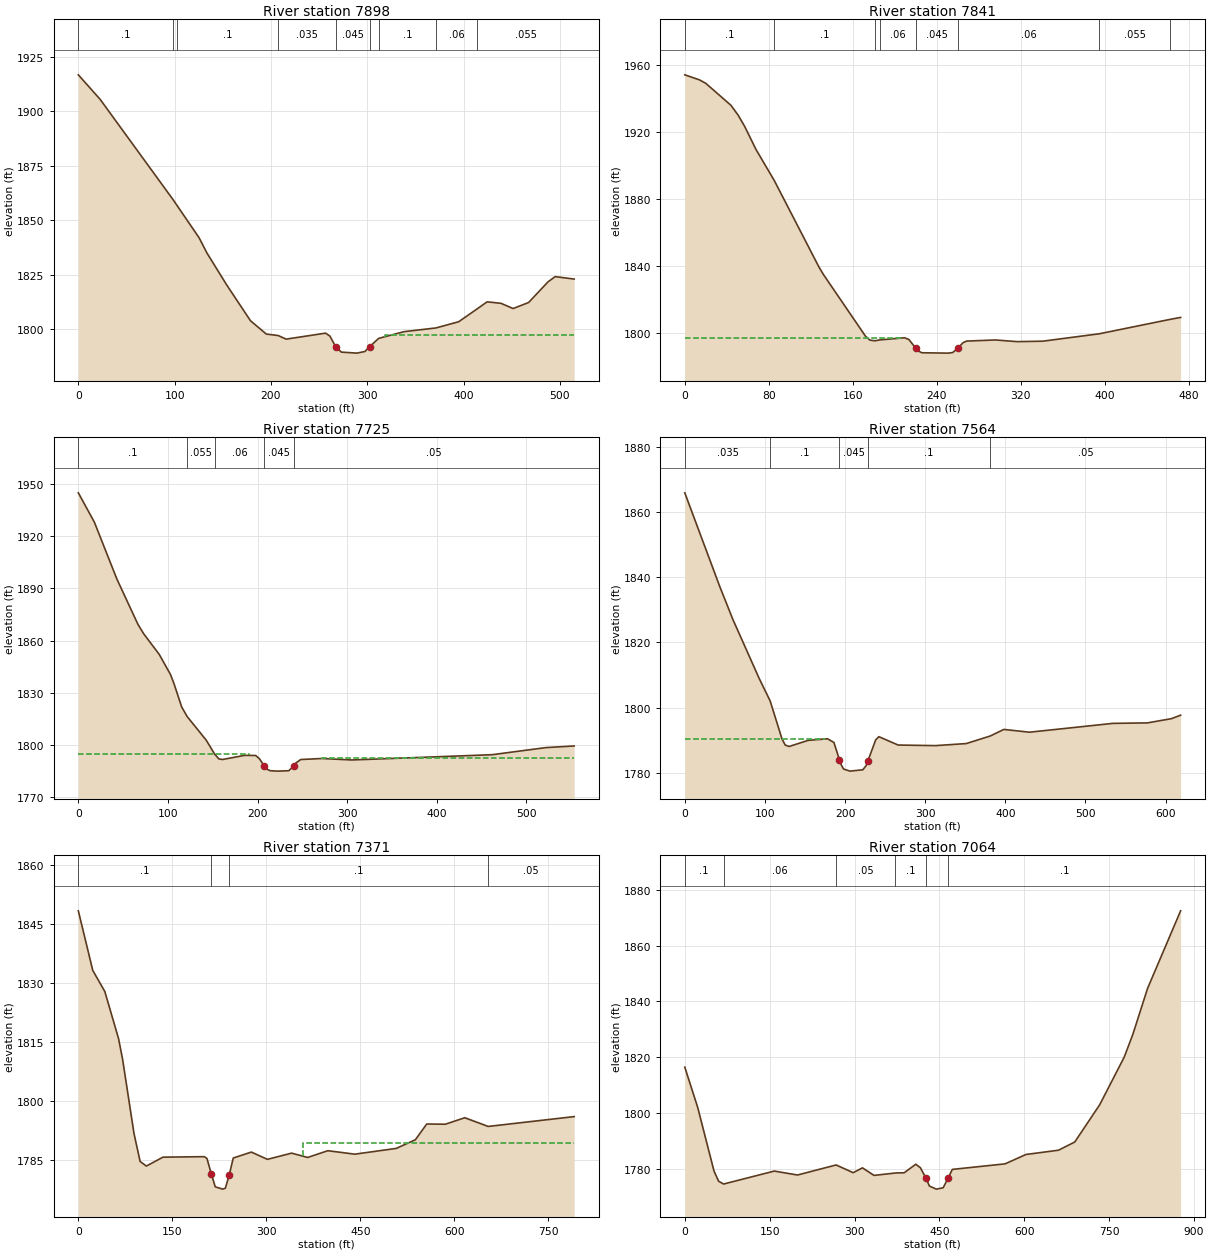
Type RM Length L Ch R = 1 ,7898    ,56.5,57.1,58.1
XS GIS Cut Line= 4
2454182.64150702613596.8944476162454127.26049181613831.449335565
2454104.45654437613943.840219374 2454084.9103037614101.838998062
#Sta/Elev= 30
       0 1916.78    22.6 1905.54    98.71859.213  102.241856.915   125.4  1841.9
   133.6 1834.86   154.1  1820.2   178.8 1803.75   195.2 1797.64  207.511796.955
   215.8  1795.3   256.8 1798.06   261.3 1796.68  267.151791.865   273.1 1789.34
   289.4 1788.87   297.6 1789.63  302.611791.864  311.911795.653   338.4 1798.75
  371.311800.438     395  1803.3   414.41809.283   424.5 1812.44   438.9 1811.76
   451.5 1809.36   467.6 1812.13   487.7 1821.61   495.2 1824.03   514.9 1822.91
#Mann= 9 ,-1 , 0
       0      .1       0    98.7      .1       0  102.24      .1       0
  207.51    .035       0  267.15    .045       0  302.61    .035       0
  311.91      .1       0  371.31     .06       0   414.4    .055       0
#XS Ineff= 2 , 0
             250  1797.3     318          1797.3
Permanent Ineff=
       F       F
Bank Sta=267.15,302.61
XS Rating Curve= 0 ,0
Exp/Cntr(USF)=0,0
Exp/Cntr=0.5,0.3

Type RM Length L Ch R = 1 ,7841    ,116,115.5,115.7
XS GIS Cut Line= 4
 2454084.9103037613622.9561018322454081.65259693613785.841440686
2454044.18896899613935.6959524322454019.75616816614088.808170954
#Sta/Elev= 30
       0 1954.15    13.8 1951.18    19.9 1949.12    43.9 1935.97    50.8 1930.08
      57 1923.36    67.9 1909.45   85.251890.967   127.6  1839.5     132 1834.84
   172.2 1797.86   176.4 1795.54  181.041795.129  185.751795.646   209.4 1796.93
   213.5 1795.92  219.871790.871   221.7 1789.31   225.8 1787.98   250.6 1787.76
   255.2 1788.09  260.371790.872   265.1    1794   268.4 1794.95   295.9 1795.63
   316.6 1794.63   340.9 1794.89  394.911799.323  462.491807.961   472.4 1809.11
#Mann= 8 ,-1 , 0
       0      .1       0   85.25      .1       0  181.04    .055       0
  185.75     .06       0  219.87    .045       0  260.37     .06       0
  394.91    .055       0  462.49     .05       0
#XS Ineff= 2 , 0
          207.66 1797.01
Permanent Ineff=
       F       F
Bank Sta=219.87,260.37
XS Rating Curve= 0 ,0
Exp/Cntr(USF)=0,0
Exp/Cntr=0.5,0.3

Type RM Length L Ch R = 1 ,7725    ,166.7,161.5,156.2
XS GIS Cut Line= 4
2454016.49846138613609.9252747242453972.51941989 613736.97583903
 2453928.5403784613935.6959524322453939.94235212614150.704599719
#Sta/Elev= 30
       0 1944.89    17.9 1928.04      43  1895.4    66.5 1869.38      73  1863.9
    90.2 1852.17   102.8 1840.59   106.8 1835.24   115.3 1821.95  121.481816.389
   142.7 1802.86  152.211794.758   156.9 1792.06     161 1791.75   185.6 1794.12
   197.9 1794.04     202 1792.23  207.471788.017   210.2 1786.19   214.2 1785.29
   222.4 1785.06   234.7 1785.28  240.731788.022   242.9 1789.78   248.2 1791.73
   271.7 1792.31   305.3 1791.47   461.7 1794.49   521.4 1798.55   553.3 1799.51
#Mann= 5 ,-1 , 0
       0      .1       0  121.48    .055       0  152.21     .06       0
  207.47    .045       0  240.73     .05       0
#XS Ineff= 2 , 0
          190.32 1794.64  272.08          1792.4
Permanent Ineff=
       F       F
Bank Sta=207.47,240.73
XS Rating Curve= 0 ,0
Exp/Cntr(USF)=0,0
Exp/Cntr=0.3,0.1

Type RM Length L Ch R = 1 ,7564    ,186,192.9,199.2
XS GIS Cut Line= 4
2453834.06688187613556.173112902 2453801.4898141613712.543038202
2453808.00522765613826.1028068452453928.67716971614149.622911559
#Sta/Elev= 30
       01865.824  43.6351837.124  59.9781827.058  92.6661809.056 106.5481802.066
 121.2671790.465 125.3531788.559 130.218 1788.13 153.8881789.995 178.1051790.487
 186.1191789.357  192.951784.086 194.1321783.015 198.1381781.221 206.1511780.577
 222.1781780.993 226.1841782.229   228.51783.706 238.2041790.141 242.2111791.125
  266.251788.569 312.7381788.389 351.1611789.016 381.0451791.322 398.1221793.349
 430.1071792.499 534.2961795.204 577.4281795.352 607.3121796.648 618.766 1797.72
#Mann= 5 ,-1 , 0
       0    .035       0 106.548      .1       0  192.95    .045       0
   228.5      .1       0 381.045     .05       0
#XS Ineff= 2 , 0
             175 1790.52  244.62         1790.52
Permanent Ineff=
       F       F
Bank Sta=192.95,228.5
XS Rating Curve= 0 ,0
Exp/Cntr(USF)=0,0
Exp/Cntr=0.3,0.1

Type RM Length L Ch R = 1 ,7371    ,309.7,307,304.8
XS GIS Cut Line= 5
2453679.32580996613484.503563807 2453645.1198888613626.213808609
2453609.28511425613740.2335458072453822.34108119613909.882921086
2453910.79608506614147.223229814
#Sta/Elev= 30
       01848.442   23.031833.289  42.2371827.937  64.1791815.953  70.6651810.649
  88.8681791.769  98.5881784.715 108.5321783.552  135.051785.816 200.998 1785.94
  205.191785.477  212.131781.558   218.41778.272 230.3481777.689 234.5411777.923
   240.71781.285 247.1191785.594 275.9861787.107 301.6721785.258   340.21786.839
 365.886 1785.74 397.9931787.456 441.0131786.575 507.1581788.041 537.6471790.241
 555.7981794.248 585.3911794.188 616.4891795.837 653.8071793.626 790.9351796.126
#Mann= 4 ,-1 , 0
       0      .1       0  212.13    .045       0   240.7      .1       0
 653.807     .05       0
#XS Ineff= 2 , 0
                          358.06         1789.39
Permanent Ineff=
       F       F
Bank Sta=212.13,240.7
XS Rating Curve= 0 ,0
Exp/Cntr(USF)=0,0
Exp/Cntr=0.3,0.1

Type RM Length L Ch R = 1 ,7064    ,187.2,193.6,199.3
XS GIS Cut Line= 4
2453412.19385424613264.6083563542453322.60691787613660.419729769
2453306.31838398613785.8414406862453229.76227472614121.385238725
#Sta/Elev= 30
       0 1816.42    22.8 1801.99    51.6 1779.21    59.8 1775.52   68.571774.516
   158.2 1779.16   199.2 1777.75  267.471781.351   297.6 1778.59   314.1 1780.31
   334.5 1777.61  372.361778.468   387.9 1778.56   408.3 1781.61   416.4 1780.38
   425.8 1776.83   432.5 1773.79   444.6 1772.69   456.7 1773.17   465.31776.554
   472.9 1779.76   566.2 1781.75   603.1 1785.11   660.6 1786.64   689.3 1789.57
   733.3 1802.88   776.7 1819.97   791.9 1828.08   818.1 1844.66   876.5 1872.45
#Mann= 6 ,-1 , 0
       0      .1       0   68.57     .06       0  267.47     .05       0
  372.36      .1       0   425.8    .045       0   465.3      .1       0
#XS Ineff= 2 , 0
          266.13 1781.14
Permanent Ineff=
       F       F
Bank Sta=425.8,465.3
XS Rating Curve= 0 ,0
Exp/Cntr(USF)=0,0
Exp/Cntr=0.3,0.1

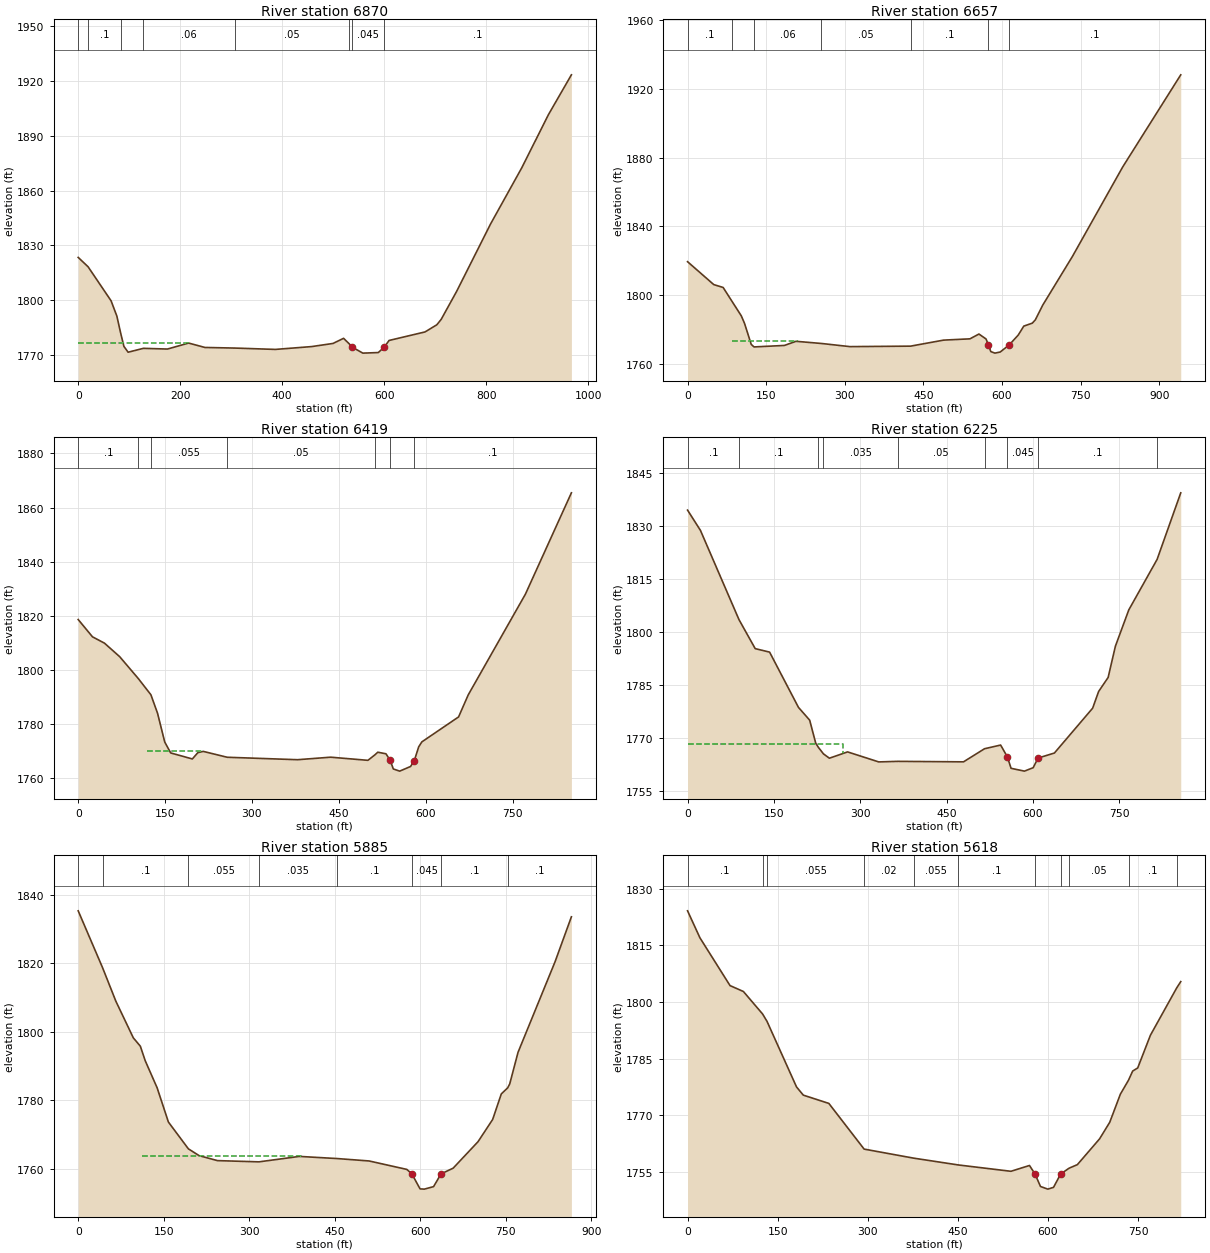
Type RM Length L Ch R = 1 ,6870    ,210.9,213.6,217.1
XS GIS Cut Line= 4
2453299.80297043613121.2692581632453145.06189852613624.584955221
2453081.53661636613800.501121183 2452977.2899995614031.798302355
#Sta/Elev= 30
       0  1823.4   19.441818.257    64.5 1799.65    75.8  1791.3   83.42 1781.84
    89.6 1774.74    97.9 1771.52  127.88 1773.64     175 1773.25   216.6 1776.52
   248.6 1774.12  307.581773.785   386.7 1773.05   457.8  1774.6   499.7 1776.31
   520.5 1779.12  531.281776.175   537.5 1774.28   558.3 1771.02   588.6 1771.33
   599.8 1774.19   609.8 1777.96   680.2 1782.61   703.4 1786.54   711.9 1789.48
   742.5 1804.96   808.6 1841.61   869.8 1872.35   922.4 1901.58   967.3 1923.31
#Mann= 8 ,-1 , 0
       0      .1       0   19.44      .1       0   83.42      .1       0
  127.88     .06       0  307.58     .05       0  531.28      .1       0
   537.5    .045       0   599.8      .1       0
#XS Ineff= 2 , 0
          216.34 1776.62
Permanent Ineff=
       F       F
Bank Sta=537.5,599.8
XS Rating Curve= 0 ,0
Exp/Cntr(USF)=0,0
Exp/Cntr=0.3,0.1

Type RM Length L Ch R = 1 ,6657    ,231.7,237.5,245.1
XS GIS Cut Line= 4
2453200.44291373613049.5997090672452978.91885289613494.276684138
2452881.18764957613683.2236772082452762.28135221 613881.94379061
#Sta/Elev= 30
       0 1819.41      50 1806.07    67.9 1804.39   85.131796.162   102.5  1787.9
   108.7 1783.48   121.5 1771.23   126.9 1769.75   184.7 1770.61     207 1773.02
  255.37 1771.77   309.8 1769.93   425.6 1770.21   488.4 1773.71   538.9 1774.47
     556 1777.26   569.5  1774.4     574 1771.05   578.6 1767.06   586.4 1766.14
   596.6 1766.79  613.941770.988     631 1776.66   641.6 1781.88   657.7 1783.59
   663.6 1785.51   677.6 1794.03   734.4 1822.47   830.3 1874.59   941.1 1928.28
#Mann= 7 ,-1 , 0
       0      .1       0   85.13      .1       0   126.9     .06       0
  255.37     .05       0   425.6      .1       0     574    .045       0
  613.94      .1       0
#XS Ineff= 1 ,-1
   85.22  210.77 1773.35
Permanent Ineff=
       F
Bank Sta=574,613.94
XS Rating Curve= 0 ,0
Exp/Cntr(USF)=0,0
Exp/Cntr=0.3,0.1

Type RM Length L Ch R = 1 ,6419    ,196.5,194.5,190.8
XS GIS Cut Line= 4
2453136.67631996612995.9480937512452861.17889499613327.751561786
2452706.33727657613472.5385296562452571.60495925613631.402008291
#Sta/Elev= 30
       0 1818.62    24.6 1812.24    45.4 1809.88    71.6  1804.9  103.931796.767
  125.551790.812     137 1783.99   149.4 1773.37   159.7 1769.32   197.1  1767.1
   206.6 1769.43   215.9 1769.89  257.321767.727   378.7 1766.82   435.9 1767.75
   500.3 1766.59  512.591768.668   517.3 1769.59   531.4 1769.01  538.84 1766.53
   544.1  1763.4   555.1  1762.6   573.9 1764.32  580.421766.526   587.9 1771.56
   593.4 1773.41   656.8 1782.63   673.5 1790.79   772.2 1827.99   851.6 1865.44
#Mann= 7 ,-1 , 0
       0      .1       0  103.93      .1       0  125.55    .055       0
  257.32     .05       0  512.59      .1       0  538.84    .045       0
  580.42      .1       0
#XS Ineff= 1 ,-1
  118.71  214.05 1769.94
Permanent Ineff=
       F
Bank Sta=538.84,580.42
XS Rating Curve= 0 ,0
Exp/Cntr(USF)=0,0
Exp/Cntr=0.3,0.1

Type RM Length L Ch R = 1 ,6225    ,342.6,339.8,336
XS GIS Cut Line= 4
2452977.81284133 612825.019034462452666.11867438613239.270636977
2452543.45193772613390.0903951752452444.91636236613494.658760859
#Sta/Elev= 30
       0  1834.5    22.4 1828.75   89.391803.436   117.5 1795.24   142.5 1794.25
   192.6 1778.59   212.1 1774.96   222.6 1768.43  227.071767.288  236.021765.411
   246.3 1764.18   277.9 1765.97     332 1763.13  364.74 1763.29   479.2 1763.15
  515.751766.867   543.7 1767.91   555.5 1764.52   561.8 1761.32     585 1760.52
   600.2 1761.49   608.7 1764.22   637.1 1765.65   703.5 1778.36   713.9  1783.1
   730.4 1787.07     743 1795.93   766.3 1806.23  815.44 1820.53   856.5  1839.4
#Mann= 9 ,-1 , 0
       0      .1       0   89.39      .1       0  227.07     .06       0
  236.02    .035       0  364.74     .05       0  515.75      .1       0
   555.5    .045       0   608.7      .1       0  815.44      .1       0
#XS Ineff= 2 , 0
          269.23 1768.31
Permanent Ineff=
       F       F
Bank Sta=555.5,608.7
XS Rating Curve= 0 ,0
Exp/Cntr(USF)=0,0
Exp/Cntr=0.3,0.1

Type RM Length L Ch R = 1 ,5885    ,261.9,266.4,269.4
XS GIS Cut Line= 4
2452706.33727657612601.8057923272452428.82892149612967.795072221
2452296.10753427613180.9536638072452207.62660946613307.642260693
#Sta/Elev= 30
       0 1835.33   42.64 1818.75    66.1  1808.9    96.7  1798.2     109 1795.76
   117.5 1791.54   138.4 1783.62   158.2  1773.6  193.221765.776   212.2 1763.77
   244.3 1762.33  317.011761.971   387.9 1763.56   454.21762.932   510.1 1762.23
   576.3 1759.76  585.181758.451   599.5 1754.07     607    1754   623.2 1754.73
  636.261758.451   657.6 1760.13   701.2 1767.87   726.8 1774.35     742 1781.83
  753.211783.609   756.7 1784.73   771.3 1793.97   836.3 1820.47   864.9 1833.58
#Mann= 8 ,-1 , 0
       0      .1       0   42.64      .1       0  193.22    .055       0
  317.01    .035       0   454.2      .1       0  585.18    .045       0
  636.26      .1       0  753.21      .1       0
#XS Ineff= 1 ,-1
  111.56  391.13  1763.7
Permanent Ineff=
       F
Bank Sta=585.18,636.26
XS Rating Curve= 0 ,0
Exp/Cntr(USF)=0,0
Exp/Cntr=0.3,0.1

Type RM Length L Ch R = 1 ,5618    ,91.4,83.2,76.9
XS GIS Cut Line= 4
2452565.57216892612489.1937062062452316.21683536612730.505319322
2452095.01452334612985.8934432042452050.77406094  613114.5929702
#Sta/Elev= 30
       0 1824.11    20.6 1816.97    70.7 1804.32      93 1802.75  124.871796.805
   132.31794.844   181.4 1777.49   192.7 1775.32   235.2 1773.13  293.941761.035
  376.251758.645  450.521756.844   538.3 1755.16   569.2  1756.7  578.381754.444
   587.5 1751.14   599.7 1750.44   609.2 1750.91  621.111754.445  635.141755.984
   648.9 1756.92   685.9 1763.75   702.8 1768.14   720.5 1775.58  734.131779.308
   740.9 1781.68   749.4 1782.53   770.5 1791.18  814.39 1803.74     821 1805.37
#Mann= 11 ,-1 , 0
       0      .1       0  124.87      .1       0   132.3    .055       0
  293.94     .02       0  376.25    .055       0  450.52      .1       0
  578.38    .045       0  621.11      .1       0  635.14     .05       0
  734.13      .1       0  814.39     .05       0
Bank Sta=578.38,621.11
XS Rating Curve= 0 ,0
Exp/Cntr(USF)=0,0
Exp/Cntr=0.5,0.3

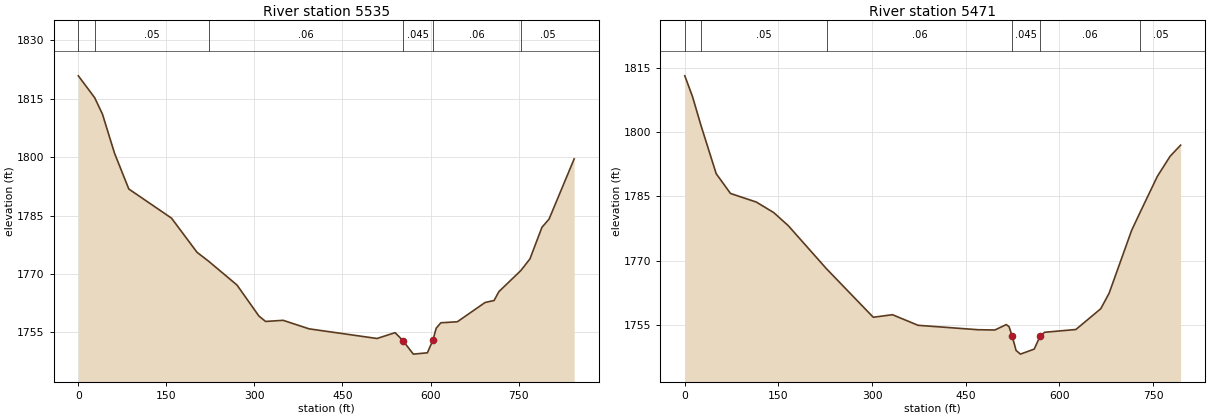
Type RM Length L Ch R = 1 ,5535    ,62.1,64.1,67.3
XS GIS Cut Line= 4
2452408.99594399612348.0191710162452201.28803205612650.234182892
2452075.62474532612918.1773892982452040.31440029613096.806193569
#Sta/Elev= 30
       0 1820.91    27.8  1815.3    41.1 1811.07    61.7    1801      86 1791.82
   158.8 1784.32   202.2 1775.55   221.9 1773.26   270.4 1767.12   307.6 1759.17
     319 1757.77   348.9 1758.06   393.2 1755.87   508.8 1753.39   539.7 1754.89
     553 1752.84   570.7 1749.37   594.7 1749.71   604.1 1752.99   609.7 1756.04
   617.6 1757.43   645.7 1757.69   692.9 1762.64   708.3 1763.16   716.4 1765.42
   753.9 1770.86   769.4 1773.86   789.8 1781.96     802  1784.1   844.7 1799.55
#Mann= 6 ,-1 , 0
       0      .1       0    27.8     .05       0   221.9     .06       0
     553    .045       0   604.1     .06       0   753.9     .05       0
#XS Ineff= 2 , 0
             535 1754.28     619         1754.28
Permanent Ineff=
       F       F
Bank Sta=553,604.1
XS Rating Curve= 0 ,0
Exp/Cntr(USF)=0,0
Exp/Cntr=0.5,0.3

Type RM Length L Ch R = 1 ,5471    ,235.9,238.5,241.1
XS GIS Cut Line= 4
2452344.36985689612320.2755770242452181.48451804612595.773001999
2452012.56638886612905.4562388322451936.15104471612999.969953969
#Sta/Elev= 30
       0 1813.15    12.3 1808.33   25.891801.587    50.3 1790.31    73.2 1785.69
   114.6 1783.68   142.4 1781.23   165.7 1778.18  227.031768.102   301.9 1756.79
   332.7 1757.38   373.7 1754.91   469.4 1753.88   496.7 1753.81     515 1755.08
   519.5 1754.57  524.631752.304   530.7 1749.04   537.7 1748.18   559.7 1749.35
  569.011752.301   576.4 1753.28   626.5 1753.93   666.4 1758.78   679.8 1762.42
   715.8 1777.07  729.63 1781.35     757 1789.68   777.5 1794.38   794.3 1796.96
#Mann= 6 ,-1 , 0
       0      .1       0   25.89     .05       0  227.03     .06       0
  524.63    .045       0  569.01     .06       0  729.63     .05       0
Bank Sta=524.63,569.01
XS Rating Curve= 0 ,0
Exp/Cntr(USF)=0,0
Exp/Cntr=0.5,0.3