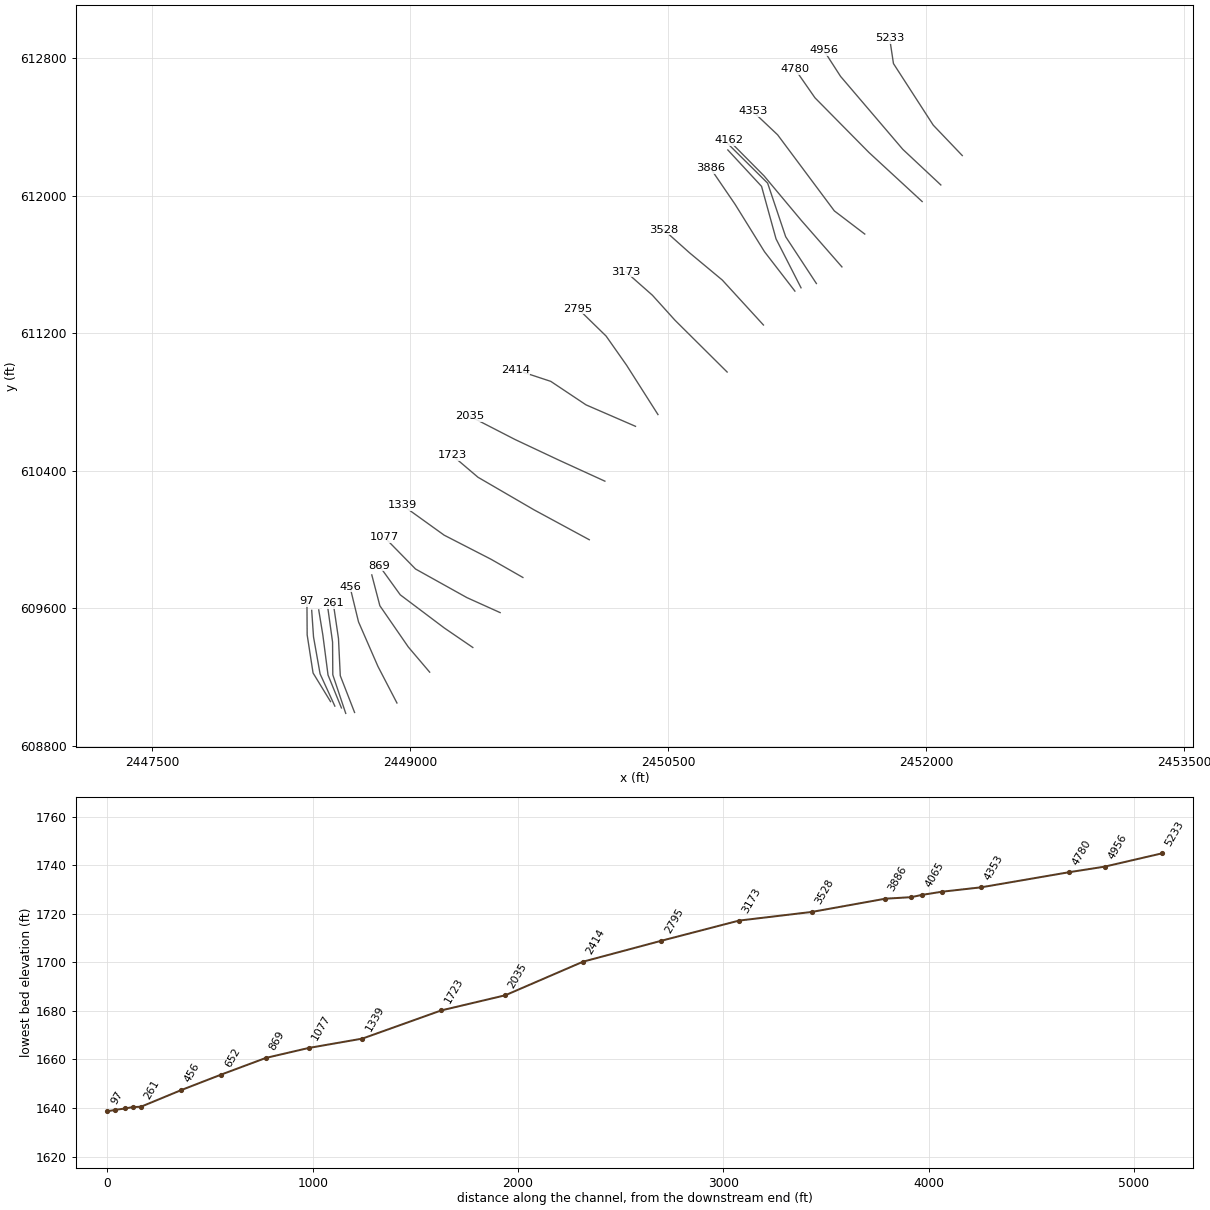
HEC-RAS study TROUTRN.prj: TROUTRN

--- TROUTRN.g01 (geometry) --- (continued)

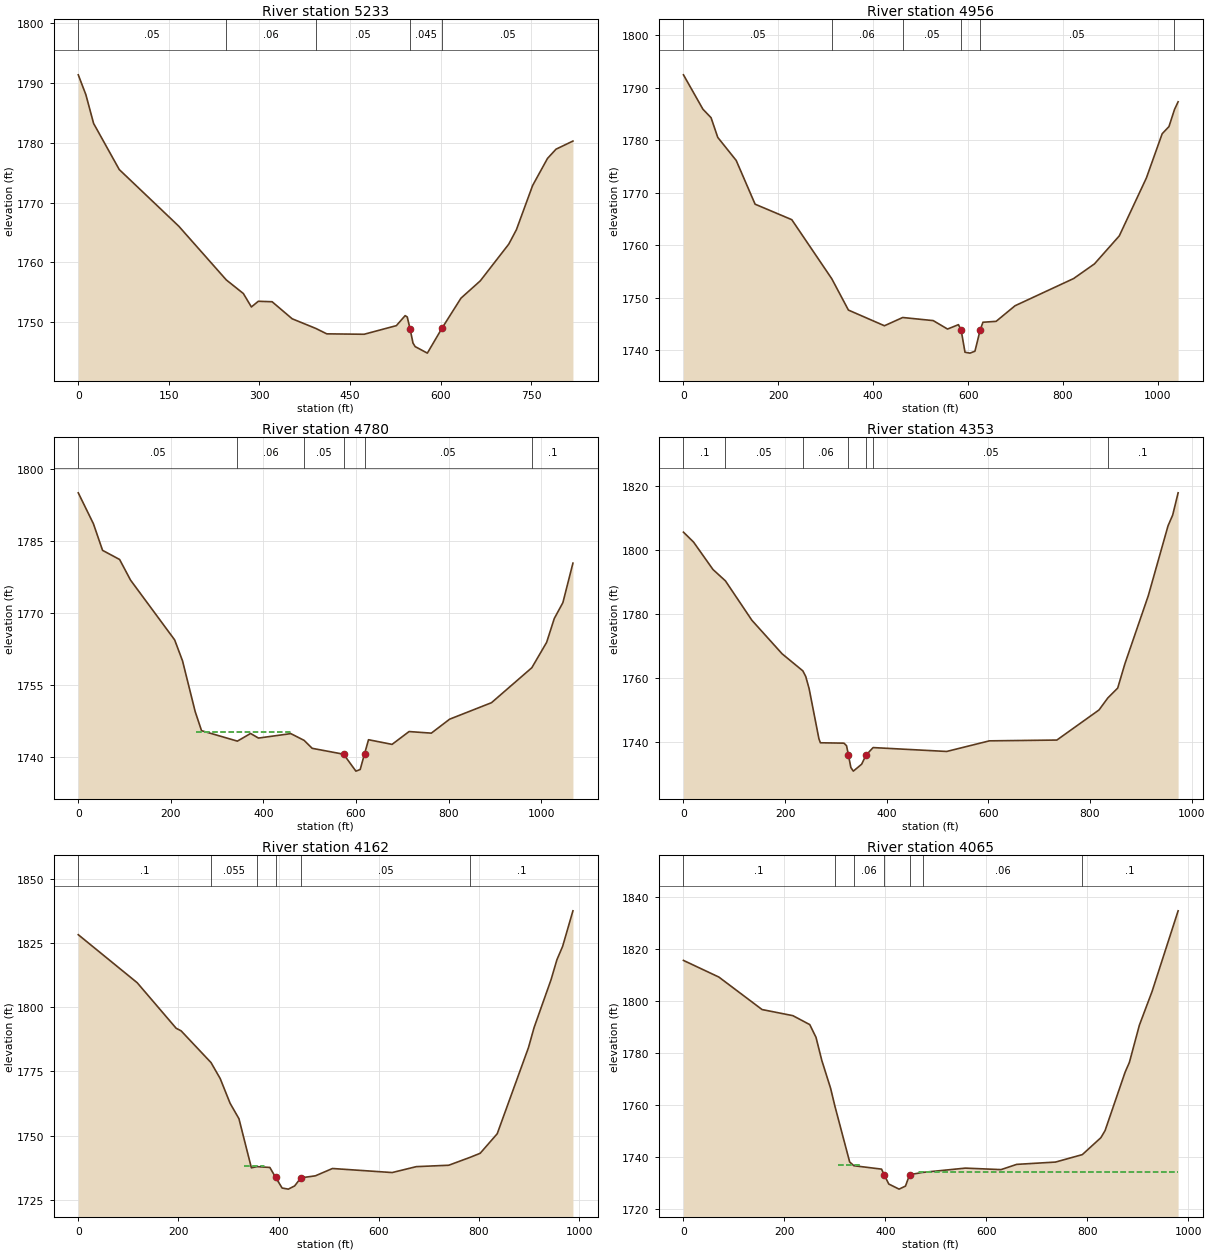
Type RM Length L Ch R = 1 ,5233    ,272.2,277.1,280.5
XS GIS Cut Line= 4
2452209.63753957612233.8055823242452040.71941039612410.767431943
2451809.46244782612768.7129913992451787.34221662612915.510889379
#Sta/Elev= 30
       0 1791.32    12.6    1788    25.4  1783.2    67.9  1775.5   166.4 1766.05
  245.091757.079   273.4  1754.8   286.7 1752.56   298.2 1753.51     321 1753.43
   354.3 1750.58   393.31748.978   411.5 1748.07   473.4    1748   526.8 1749.44
   541.3 1751.11   544.8 1750.89   549.6 1748.86   554.3 1746.54   557.9 1745.94
   578.1 1744.85  602.191748.987   633.8 1754.03   665.7 1756.91     713 1763.06
   725.6 1765.46   752.4 1772.83     777 1777.35   791.1  1778.9   819.2 1780.26
#Mann= 5 ,-1 , 0
       0     .05       0  245.09     .06       0   393.3     .05       0
   549.6    .045       0  602.19     .05       0
Bank Sta=549.6,602.19
XS Rating Curve= 0 ,0
Exp/Cntr(USF)=0,0
Exp/Cntr=0.3,0.1

Type RM Length L Ch R = 1 ,4956    ,187.5,175.5,176.8
XS GIS Cut Line= 4
2452084.95987279612062.8765230332451863.75756077612270.002324291
 2451501.7901411612694.3085773552451403.25456574612847.139265662
#Sta/Elev= 30
       0 1792.49      41 1785.94    58.2 1784.31    72.3 1780.56   111.2 1776.16
     151 1767.82   228.3 1764.87  312.581753.608   347.7 1747.63   423.6 1744.64
  462.131746.213   526.5 1745.62   556.6 1744.01   579.6 1744.85   585.41743.751
   593.4 1739.59   603.9 1739.42   614.4 1739.79  625.17 1743.75   631.2 1745.31
     659 1745.48   698.8 1748.45   822.3 1753.64   866.3 1756.44   918.6 1761.78
   975.7 1772.82    1009 1781.26  1023.3 1782.62 1034.931785.876  1042.6 1787.35
#Mann= 6 ,-1 , 0
       0     .05       0  312.58     .06       0  462.13     .05       0
   585.4    .045       0  625.17     .05       0 1034.93      .1       0
Bank Sta=585.4,625.17
XS Rating Curve= 0 ,0
Exp/Cntr(USF)=0,0
Exp/Cntr=0.3,0.1

Type RM Length L Ch R = 1 ,4780    ,387.3,426.9,417.8
XS GIS Cut Line= 4
2451976.36964689611966.3518777862451666.68641006612251.903953308
2451352.98131301612569.6309105782451238.35829678612734.527179541
#Sta/Elev= 30
       0 1795.04    32.7  1788.6    52.5 1783.06    89.3 1781.16   112.9 1776.87
   208.2 1764.42   225.2 1760.06   252.5 1749.51   266.3 1745.51  343.731743.337
   372.2 1744.93   389.3 1743.97   459.2  1744.9  487.851743.495   505.3 1741.84
   573.2 1740.61   599.7 1737.09     609 1737.42   618.5 1740.72     627 1743.63
   677.9 1742.66   714.6 1745.33   762.7    1745   802.3 1747.91   892.7 1751.34
  979.841758.625  1011.8 1763.91  1028.3 1768.87  1046.9 1772.18  1068.6  1780.4
#Mann= 6 ,-1 , 0
       0     .05       0  343.73     .06       0  487.85     .05       0
   573.2    .045       0   618.5     .05       0  979.84      .1       0
#XS Ineff= 1 ,-1
  253.39  457.99 1745.22
Permanent Ineff=
       F
Bank Sta=573.2,618.5
XS Rating Curve= 0 ,0
Exp/Cntr(USF)=0,0
Exp/Cntr=0.3,0.1

Type RM Length L Ch R = 1 ,4353    ,190.1,191.7,193.1
XS GIS Cut Line= 4
2451642.55524875611777.3244475112451465.59339913611912.056764835
 2451135.8008612612354.4613888822450991.01389333612491.204636315
#Sta/Elev= 30
       0 1805.49    19.9 1802.39    58.1 1793.83    82.61790.282   134.6    1778
   194.1 1767.52  234.93 1762.19   240.6 1760.44   247.3 1756.63   266.5 1741.04
   269.4 1739.74   315.8 1739.62   320.9 1738.83  324.711735.856   329.4 1732.02
   334.3 1730.89   350.7 1733.06  359.141735.853   373.21738.241     518 1737.03
     602 1740.34   734.8 1740.59   817.7 1749.98  835.071753.737   854.5 1756.82
   868.6 1764.37   914.7 1785.65   953.5 1807.45   962.7 1810.83   973.4 1817.77
#Mann= 7 ,-1 , 0
       0      .1       0    82.6     .05       0  234.93     .06       0
  324.71    .045       0  359.14     .06       0   373.2     .05       0
  835.07      .1       0
Bank Sta=324.71,359.14
XS Rating Curve= 0 ,0
Exp/Cntr(USF)=0,0
Exp/Cntr=0.3,0.1

Type RM Length L Ch R = 1 ,4162    ,104.6,96.6,85.9
XS GIS Cut Line= 4
2451509.83386153611586.2860871272451272.54410863611857.761651883
2451057.37458694612115.1607058752450852.25971579612322.286507133
#Sta/Elev= 30
       0 1828.37   117.7 1809.62   195.4 1791.86   205.3 1790.85  265.041778.461
   283.3 1772.25   303.1 1762.59   320.8 1756.55   345.6 1737.39     357 1737.85
   382.5 1737.53  393.941733.647     407  1729.5   419.4 1729.07     432 1730.32
   444.4 1733.47   473.4 1734.26   507.5 1737.12   626.7 1735.54     675 1737.85
   739.6 1738.39  782.791741.513   802.4 1743.06   836.4 1750.67   898.8  1784.3
   910.1 1792.17   943.8 1810.75   955.6 1818.59     967 1823.81   987.6 1837.69
#Mann= 6 ,-1 , 0
       0      .1       0  265.04    .055       0     357     .06       0
  393.94    .045       0   444.4     .05       0  782.79      .1       0
#XS Ineff= 1 ,-1
  330.41   370.3 1738.29
Permanent Ineff=
       F
Bank Sta=393.94,444.4
XS Rating Curve= 0 ,0
Exp/Cntr(USF)=0,0
Exp/Cntr=0.5,0.3

Type RM Length L Ch R = 1 ,4065    ,52.9,51.9,50.1
XS GIS Cut Line= 4
2451361.27307681611489.6852284862451182.64427254611761.782593131
2451077.75177701612073.3444610452450846.15745519612302.861703741
#Sta/Elev= 30
       0  1815.5    70.2 1809.11   155.8 1796.65   216.8 1794.31   250.3 1790.88
   262.7 1785.98   274.2 1777.12   291.6 1766.45   300.2 1759.54   329.4 1738.18
   337.7 1736.75   392.6 1735.44  397.46 1733.37   406.9 1729.73   427.3 1727.77
     440 1728.94  448.21  1733.3   473.8 1734.18   558.8 1735.83   629.4 1735.25
   660.3 1737.26   737.3 1738.15   790.4    1741   827.2  1747.5   835.6 1750.25
   875.2 1772.61   883.7 1776.37   903.5 1790.65   928.8 1803.66   980.3 1834.52
#Mann= 7 ,-1 , 0
       0      .1       0   300.2    .055       0   337.7     .06       0
  397.46    .045       0  448.21     .05       0   473.8     .06       0
   790.4      .1       0
#XS Ineff= 3 ,-1
  305.52  348.93 1737.21  360.74  381.661734.243  467.04  981.341734.241
Permanent Ineff=
       F       F       F
Bank Sta=397.46,448.21
XS Rating Curve= 0 ,0
Exp/Cntr(USF)=0,0
Exp/Cntr=0.5,0.3

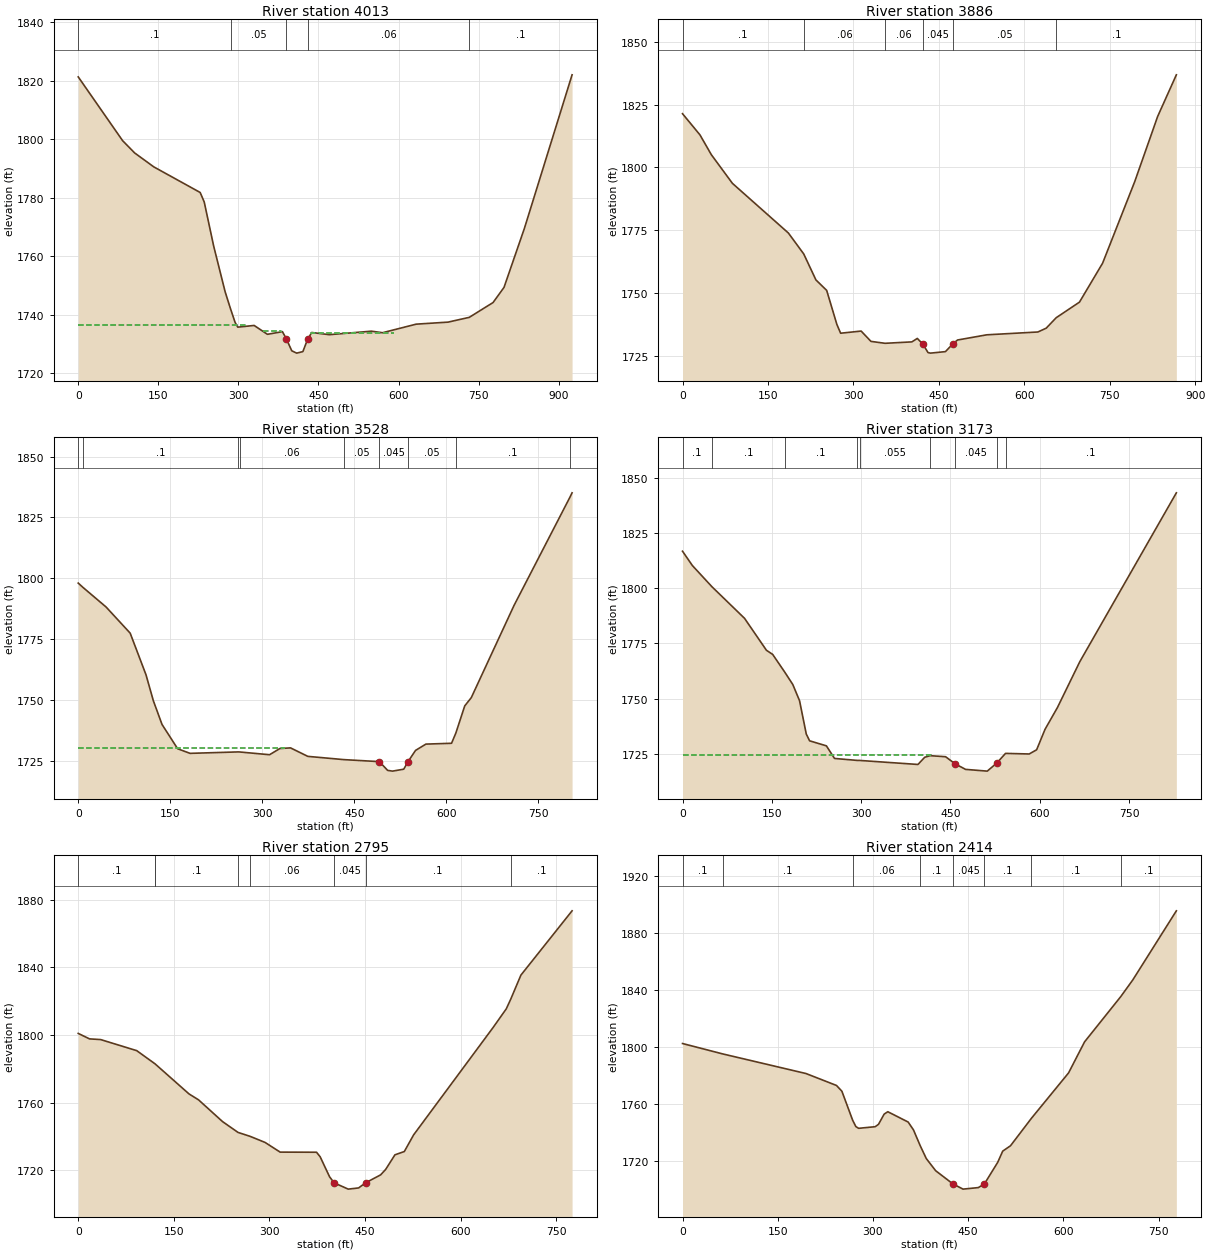
Type RM Length L Ch R = 1 ,4013    ,122.1,127.5,136.8
XS GIS Cut Line= 4
2451271.95867467611464.7602790532451126.56313631611749.320118414
2451042.44143198 612054.650748972450846.15745519612266.512819151
#Sta/Elev= 30
       0 1821.35    83.2 1799.52   105.7 1795.33   141.6 1790.56   228.4 1781.81
     236 1778.57   253.9 1763.32   275.2 1747.83   285.4 1741.94   293.8 1737.37
   298.9 1735.73   329.5 1736.31   354.4 1733.28   382.5 1734.19  390.05 1731.64
     400 1727.64   409.2 1726.84   420.8 1727.36  429.85 1731.64   437.4  1733.9
   470.3 1733.15   549.4 1734.35   570.1 1733.82     633 1736.75   692.8 1737.45
   732.5 1739.08   777.1 1744.15   797.6 1749.33   835.9 1769.58   925.1 1822.06
#Mann= 5 ,-1 , 0
       0      .1       0   285.4     .05       0  390.05    .045       0
  429.85     .06       0   732.5      .1       0
#XS Ineff= 3 ,-1
       0  316.46 1736.62  345.51  379.321734.317  436.19  591.891733.816
Permanent Ineff=
       F       F       F
Bank Sta=390.05,429.85
XS Rating Curve= 0 ,0
Exp/Cntr(USF)=0,0
Exp/Cntr=0.5,0.3

Type RM Length L Ch R = 1 ,3886    ,349.6,357.4,364.1
XS GIS Cut Line= 4
2451236.34736667611445.5209794762451059.38551705611674.767011937
2450888.45645776611950.264436912   2450745.68042612159.401168279
#Sta/Elev= 30
       0 1821.35    30.6 1812.94    50.6 1805.06    87.6 1793.67   185.9 1773.92
   212.81765.617   234.2 1755.29   253.1 1751.12     271 1737.59   277.6  1734.1
   313.6 1734.96   330.8 1730.86  355.511730.095   402.7 1730.66   412.2 1732.03
  422.131729.726     431 1726.41   435.4 1726.19   461.6 1726.79  474.071729.729
   482.7  1731.4   534.2 1733.47   623.9 1734.59   638.5 1736.11  656.041740.263
   696.9 1746.46   737.5 1761.93     794 1794.41   834.2 1820.28     867  1836.8
#Mann= 6 ,-1 , 0
       0      .1       0   212.8     .06       0  355.51     .06       0
  422.13    .045       0  474.07     .05       0  656.04      .1       0
#XS Ineff= 2 , 0
          412.02 1731.85  537.63         1733.49
Permanent Ineff=
       F       F
Bank Sta=422.13,474.07
XS Rating Curve= 0 ,0
Exp/Cntr(USF)=0,0
Exp/Cntr=0.3,0.1

Type RM Length L Ch R = 1 ,3528    ,357.6,354.8,345
XS GIS Cut Line= 4
2451053.35272672611248.4498287642450814.05204371611509.870742974
2450623.01368333611668.7342216092450472.19392513611803.466538932
#Sta/Elev= 30
       0    1798    7.931796.181    45.3  1788.2    84.7 1777.43   110.5 1760.32
   122.5 1749.64   136.6 1739.93   162.1 1729.94   182.3 1728.05  261.111728.644
  263.481728.607   311.9 1727.49   328.7 1730.03   346.1  1730.3   374.3 1726.81
  433.581725.469     491 1724.65   504.4 1721.06   512.4 1720.75   530.7 1721.55
   537.4 1724.55   549.9 1729.26   566.8 1731.85   608.6 1732.19  615.631736.393
   630.1 1747.55   640.8 1750.94   710.5 1788.83   801.61833.277   805.1 1835.08
#Mann= 9 ,-1 , 0
       0      .1       0    7.93      .1       0  261.11      .1       0
  263.48     .06       0  433.58     .05       0     491    .045       0
   537.4     .05       0  615.63      .1       0   801.6      .1       0
#XS Ineff= 2 , 0
          337.37 1730.17
Permanent Ineff=
       F       F
Bank Sta=491,537.4
XS Rating Curve= 0 ,0
Exp/Cntr(USF)=0,0
Exp/Cntr=0.3,0.1

Type RM Length L Ch R = 1 ,3173    ,379.5,378.1,373.5
XS GIS Cut Line= 4
2450842.20506524610974.9633338982450538.55461874611276.602850294
2450407.84416163611421.3898181642450253.00254322611558.133065597
#Sta/Elev= 30
       0 1816.81    16.5 1810.34   49.441800.715   104.2  1786.4     141 1771.93
   151.5 1770.04  171.591762.098   185.3  1756.4   196.6 1749.09   207.9 1733.98
   213.5 1730.91   241.7 1728.63   255.3 1722.93  293.731722.025  297.521722.023
   395.5  1720.2   406.9 1723.46  415.881724.176   441.9 1723.71     458 1720.48
   475.5 1717.97   511.9 1717.18  527.781720.793  542.651725.218   582.4 1724.95
   594.9 1726.86   608.9 1736.07   629.9 1746.03   667.4 1766.76   829.6 1843.26
#Mann= 9 ,-1 , 0
       0      .1       0   49.44      .1       0  171.59      .1       0
  293.73      .1       0  297.52    .055       0  415.88     .06       0
     458    .045       0  527.78     .05       0  542.65      .1       0
#XS Ineff= 2 , 0
          420.72 1724.32
Permanent Ineff=
       F       F
Bank Sta=458,527.78
XS Rating Curve= 0 ,0
Exp/Cntr(USF)=0,0
Exp/Cntr=0.3,0.1

Type RM Length L Ch R = 1 ,2795    ,371.1,381.5,389.6
XS GIS Cut Line= 4
2450440.01904338610727.6189304542450257.02440343611015.181936084
2450138.37952699611184.1000652662449975.49418813611342.963543901
#Sta/Elev= 30
       0 1800.98    17.8 1797.75    35.2 1797.34    91.8 1790.79  120.391783.018
  120.881782.865   173.7 1765.23   188.8 1761.68   226.4 1748.83  250.711742.428
  269.741740.091   293.1 1736.51   316.8 1730.77   373.9  1730.7   379.6 1727.99
   394.3 1716.21  401.391712.618   423.6 1708.88   439.9 1709.59  450.871712.619
   474.4 1717.31   482.3 1720.51   496.9 1729.18   511.6 1731.12   526.2 1740.97
   650.8 1804.43   671.6 1815.54  678.581821.252   694.5 1835.46   774.8  1873.5
#Mann= 8 ,-1 , 0
       0      .1       0  120.39      .1       0  120.88      .1       0
  250.71      .1       0  269.74     .06       0  401.39    .045       0
  450.87      .1       0  678.58      .1       0
Bank Sta=401.39,450.87
XS Rating Curve= 0 ,0
Exp/Cntr(USF)=0,0
Exp/Cntr=0.3,0.1

Type RM Length L Ch R = 1 ,2414    ,375,379,382.4
XS GIS Cut Line= 4
2450309.30858628610659.2473067372450021.74558065610783.924973514
 2449816.6307095610920.6682209472449609.50490824610989.039844664
#Sta/Elev= 30
       0  1802.3   63.231795.021   194.6 1781.26   242.6  1772.9   251.1 1768.88
  268.151748.456   273.1 1744.11   277.5 1742.87   303.6 1744.01   308.8 1745.68
   317.7 1752.83   323.5 1754.49   355.5 1747.27   363.9 1741.77  374.331730.872
   384.1 1721.67   398.8 1713.19  426.021703.925     442 1700.26   466.1 1701.34
  475.691703.926   496.6 1719.02   504.5 1726.88   516.8 1730.66   549.81749.927
   608.3 1781.72   633.5 1803.48   690.61835.234   709.4 1846.82   778.1 1895.28
#Mann= 8 ,-1 , 0
       0      .1       0   63.23      .1       0  268.15     .06       0
  374.33      .1       0  426.02    .045       0  475.69      .1       0
   549.8      .1       0   690.6      .1       0
Bank Sta=426.02,475.69
XS Rating Curve= 0 ,0
Exp/Cntr(USF)=0,0
Exp/Cntr=0.3,0.1

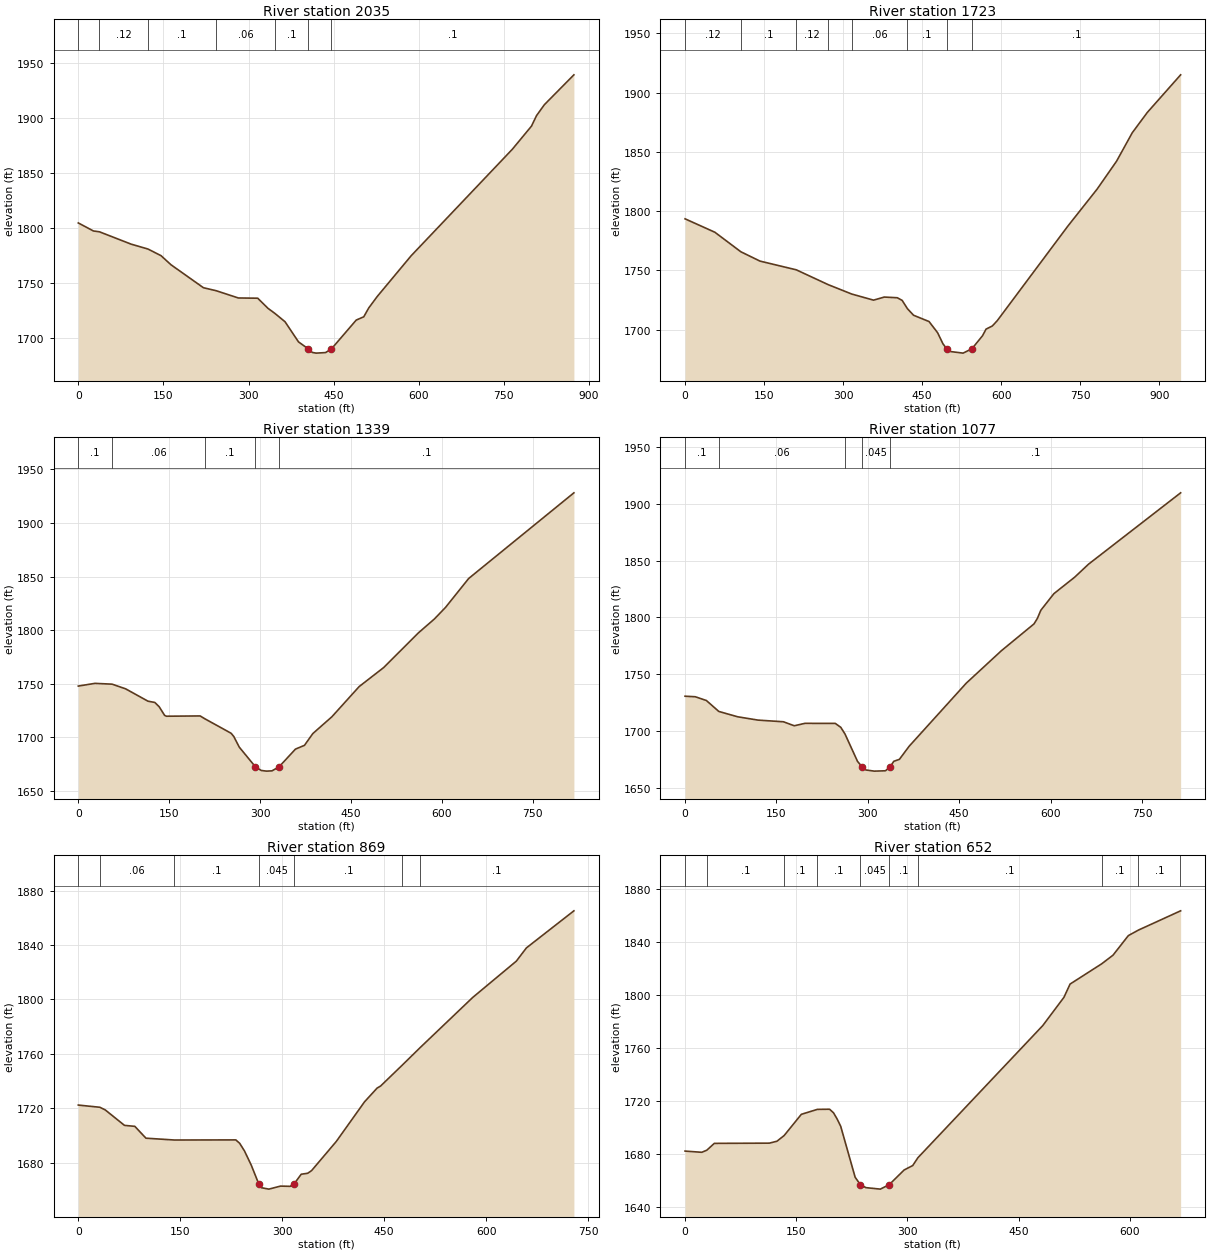
Type RM Length L Ch R = 1 ,2035    ,313.4,312.1,310
XS GIS Cut Line= 4
2450131.30246561610340.2612652972449866.42808134610461.346698107
2449609.12153662610582.4321309172449344.24715235610718.653242827
#Sta/Elev= 30
       0 1804.82    26.6 1797.52   37.281796.762      93 1785.56   122.8 1781.09
   145.8 1775.06   163.3 1766.81   220.5 1745.91  243.27 1743.14   282.1 1736.58
   316.2 1736.38   334.2 1727.21  346.431722.555   364.3 1714.99   388.1 1696.65
  405.321690.292   412.4 1687.07   419.1 1686.42   435.8 1686.91  446.181690.288
   489.8 1716.46   503.1 1719.47   511.9  1727.5   526.6 1737.77   586.6 1774.95
   764.9  1871.8   798.7 1892.87   807.7 1902.49   821.5  1912.4   873.5 1939.54
#Mann= 7 ,-1 , 0
       0      .1       0   37.28     .12       0   122.8      .1       0
  243.27     .06       0  346.43      .1       0  405.32    .045       0
  446.18      .1       0
Bank Sta=405.32,446.18
XS Rating Curve= 0 ,0
Exp/Cntr(USF)=0,0
Exp/Cntr=0.3,0.1

Type RM Length L Ch R = 1 ,1723    ,382.4,383.6,383.8
XS GIS Cut Line= 4
2450040.48839101 609999.708485522449718.85521011610173.768795184
2449393.43810943610362.9647839492449242.08131842610491.618056309
#Sta/Elev= 30
       0 1793.51    56.6 1782.19  106.031765.685   142.3 1757.83  211.211750.468
  271.891737.933  316.381730.049   357.8 1724.89   378.3  1727.5   402.9 1726.91
   412.1  1724.7  422.181717.679   433.9 1712.12   463.2 1706.83   479.4 1697.44
   489.5 1688.14   496.71683.861   504.6 1681.47   527.8 1680.18  544.591683.861
   564.8  1694.9   571.4 1700.42   583.3 1703.08   592.6 1707.51   726.7 1787.36
   782.4 1818.66   819.2 1842.14     849 1866.16   877.4 1883.19   940.8 1915.02
#Mann= 8 ,-1 , 0
       0     .12       0  106.03      .1       0  211.21     .12       0
  271.89      .1       0  316.38     .06       0  422.18      .1       0
   496.7    .045       0  544.59      .1       0
Bank Sta=496.7,544.59
XS Rating Curve= 0 ,0
Exp/Cntr(USF)=0,0
Exp/Cntr=0.3,0.1

Type RM Length L Ch R = 1 ,1339    ,262.4,262.3,261.8
XS GIS Cut Line= 4
2449654.52857393609780.2411385532449469.11650494609886.190892261
2449196.67428111610026.1959239472448954.50341549610200.256233611
#Sta/Elev= 30
       0 1747.91    27.4 1750.44   55.761749.697    78.1 1745.34   114.9 1733.85
   126.3 1732.63   133.4  1728.7   142.5 1720.56   145.4  1719.8   201.1 1720.06
   209.21717.305   252.2 1703.91   256.7 1700.84   265.7 1690.95  292.361672.589
     302  1669.2   310.7 1668.59   319.8 1668.86  331.361672.586   358.4  1689.1
   373.3 1692.63   387.1 1703.61   418.6 1719.29   463.6 1747.44     504 1765.15
   561.6 1797.63   587.7 1810.44     606 1821.17   644.4 1848.25   818.1 1928.14
#Mann= 5 ,-1 , 0
       0      .1       0   55.76     .06       0   209.2      .1       0
  292.36    .045       0  331.36      .1       0
Bank Sta=292.36,331.36
XS Rating Curve= 0 ,0
Exp/Cntr(USF)=0,0
Exp/Cntr=0.3,0.1

Type RM Length L Ch R = 1 ,1077    ,210.5,207.9,203.8
XS GIS Cut Line= 4
2449522.09138179609575.9094706862449329.11147325609662.939625518
  2449030.181811609829.4320956322448848.55366179610014.844164621
#Sta/Elev= 30
       0 1730.62    16.8 1730.15      35 1726.85   55.411717.223    86.4 1712.52
   119.7 1709.61   161.6 1708.13   179.2 1704.62   196.7 1706.75   246.5 1706.72
   255.6 1703.25  262.45 1697.47   283.1 1673.28  290.451668.578   296.8 1665.72
   310.6 1664.72   328.9 1665.02  336.581668.578   342.6 1673.36   351.8 1675.07
   367.8 1686.59   461.6 1742.13   519.2 1770.63   572.7 1794.22   578.3 1799.09
   583.9  1806.2   605.4 1820.85   639.4 1835.29   662.3  1846.8   813.4 1909.54
#Mann= 5 ,-1 , 0
       0      .1       0   55.41     .06       0  262.45      .1       0
  290.45    .045       0  336.58      .1       0
Bank Sta=290.45,336.58
XS Rating Curve= 0 ,0
Exp/Cntr(USF)=0,0
Exp/Cntr=0.3,0.1

Type RM Length L Ch R = 1 ,869     ,221.8,216.9,204.3
XS GIS Cut Line= 4
2449363.34081154609373.1367777682449197.83216057609486.234355932
2448941.29375156609679.3277820652448819.92074085609847.594910553
#Sta/Elev= 30
       0 1722.39   31.561720.787    39.5 1718.87    67.9 1707.48    83.1 1706.76
    99.5 1698.06  141.271696.715   231.7  1696.8   237.4 1694.27   244.4 1688.71
   254.4 1678.25  265.291664.658   269.4 1661.67   280.3 1660.63   297.4 1662.85
   311.7 1662.68  317.691664.656   327.9 1671.58   337.4 1672.28   343.1 1674.22
   379.5 1695.67     421 1724.77   439.6 1734.92   444.6 1736.36   476.61751.785
  503.051764.725   580.2 1801.49   644.3 1828.15   659.1 1837.87     729 1865.12
#Mann= 7 ,-1 , 0
       0      .1       0   31.56     .06       0  141.27      .1       0
  265.29    .045       0  317.69      .1       0   476.6      .1       0
  503.05      .1       0
Bank Sta=265.29,317.69
XS Rating Curve= 0 ,0
Exp/Cntr(USF)=0,0
Exp/Cntr=0.3,0.1

Type RM Length L Ch R = 1 ,652     ,199.9,195.5,193.4
XS GIS Cut Line= 4
2449112.31935756609229.6959469262448988.18786933609375.895255284
2448822.67921836609615.8827991932448775.78510059609795.183837745
#Sta/Elev= 30
       0 1682.43    22.6 1681.52   29.371683.108    39.5 1688.24   113.7 1688.41
     124 1689.86  133.651694.105   156.9 1710.11  178.521713.836     195 1713.95
   200.3 1711.27   205.1 1706.69     210 1701.13   229.5 1662.74   236.51657.173
     244 1654.91   263.5 1653.79   275.5 1657.17   295.6 1668.21   307.2 1671.55
  314.121677.404   482.6  1776.9   511.2  1798.2   519.5 1808.19  562.011823.383
   577.4 1829.93   598.1 1844.67  611.661848.816  668.351863.261668.6461 1863.33
#Mann= 10 ,-1 , 0
       0     .06       0   29.37      .1       0  133.65      .1       0
  178.52      .1       0   236.5    .045       0   275.5      .1       0
  314.12      .1       0  562.01      .1       0  611.66      .1       0
  668.35      .1       0
Bank Sta=236.5,275.5
XS Rating Curve= 0 ,0
Exp/Cntr(USF)=0,0
Exp/Cntr=0.3,0.1

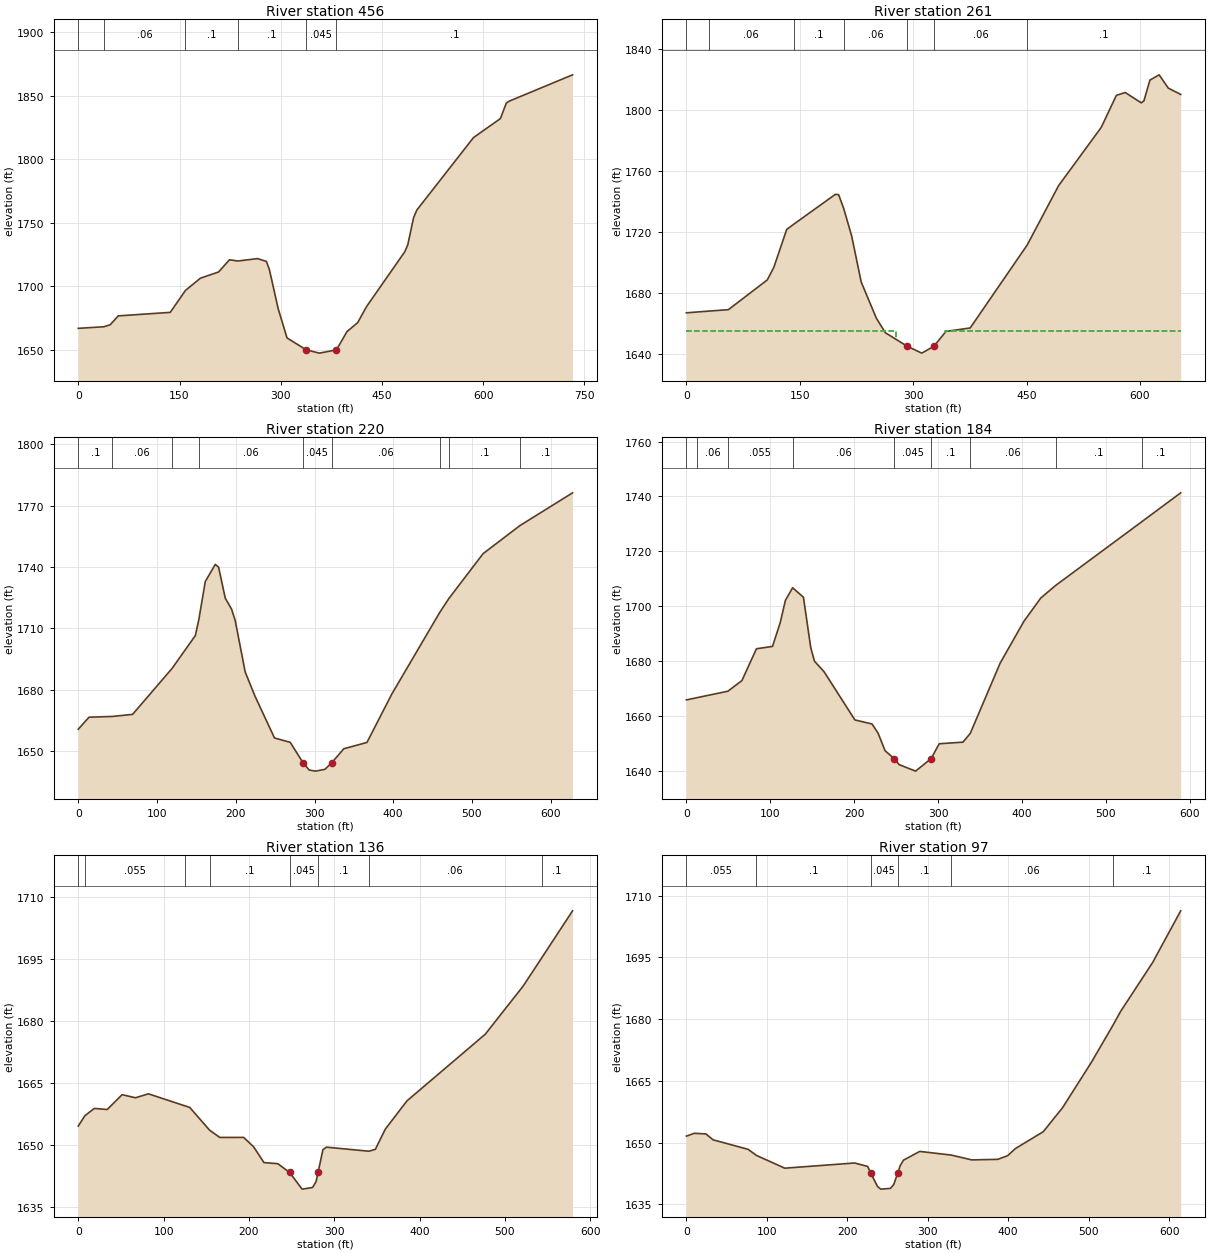
Type RM Length L Ch R = 1 ,456     ,200.9,195.7,189.1
XS GIS Cut Line= 4
2448921.98440895609050.394908373 2448811.6453083 609262.79767712
2448698.54773013609522.0945636422448648.89513484609726.221899841
#Sta/Elev= 30
       0 1666.88   37.881668.125    47.3 1669.68    59.2 1676.69   136.3 1679.45
  158.861696.724   180.9  1706.3   207.9 1711.23     224 1720.81  236.391719.861
   265.6 1721.75   278.7 1719.56   283.1 1713.26   296.2 1682.34   309.3 1659.34
  337.841649.944   357.3 1647.38  382.541649.944   398.1  1664.3     414 1671.39
   427.1 1683.99   483.8 1727.16   488.2 1732.66   496.9 1754.13   501.7 1760.01
   585.6 1816.99   625.4  1831.9   634.2  1844.1   638.3 1845.59732.3205 1866.34
#Mann= 6 ,-1 , 0
       0    .055       0   37.88     .06       0  158.86      .1       0
  236.39      .1       0  337.84    .045       0  382.54      .1       0
Bank Sta=337.84,382.54
XS Rating Curve= 0 ,0
Exp/Cntr(USF)=0,0
Exp/Cntr=0.5,0.3

Type RM Length L Ch R = 1 ,261     ,41.9,41.1,40.2
XS GIS Cut Line= 4
2448675.69480901608995.1942295262448592.57442059 609208.93237117
2448582.01945063609425.309255303  2448551.673912609631.131169479
#Sta/Elev= 30
       0 1667.01    29.31668.133    55.5 1669.07     107 1688.61   115.6 1696.78
   132.7 1721.75  142.011725.199   197.1 1744.84   201.4 1744.64  208.111735.594
   218.6  1717.6   231.3 1687.24   251.3 1663.51   263.3 1653.91  292.431644.998
   311.4 1640.54  327.44    1645   343.4 1654.79   375.5 1657.08  451.031711.648
   492.5 1750.57   548.9 1788.84   568.9 1809.85   580.6 1811.73   601.8 1804.94
   605.3 1806.15   613.3 1819.89   625.5 1823.34   637.6 1814.61654.0127 1810.46
#Mann= 7 ,-1 , 0
       0      .1       0    29.3     .06       0  142.01      .1       0
  208.11     .06       0  292.43    .045       0  327.44     .06       0
  451.03      .1       0
#XS Ineff= 2 , 0
             277    1655     342            1655
Permanent Ineff=
       F       F
Bank Sta=292.43,327.44
XS Rating Curve= 0 ,0
Exp/Cntr(USF)=0,0
Exp/Cntr=0.5,0.3

Type RM Length L Ch R = 1 ,220     ,33.9,36,38.2
XS GIS Cut Line= 4
2448624.23933046608989.9167445472448549.03516951609214.209856149
2448547.71579827609404.1993153882448520.00900213 609603.42437334
#Sta/Elev= 30
       0 1660.83    13.7 1666.69   43.311667.055      69 1668.07  119.321690.584
   148.7 1706.55  153.13 1714.37   161.3  1732.9     174 1741.29   178.2 1739.94
   186.7 1724.78   194.7 1719.46   199.3 1713.93     212 1688.75   224.6 1676.82
   249.2 1656.55   269.2 1654.41  285.241644.566   293.2 1640.91   301.2 1640.36
   313.2 1641.24   322.21644.569   337.2 1651.28   366.6 1654.36   398.4 1678.14
  458.891717.754  470.791724.709   514.1 1746.54  560.741760.191627.7017 1776.23
#Mann= 9 ,-1 , 0
       0      .1       0   43.31     .06       0  119.32    .055       0
  153.13     .06       0  285.24    .045       0   322.2     .06       0
  458.89      .1       0  470.79      .1       0  560.74      .1       0
Bank Sta=285.24,322.2
XS Rating Curve= 0 ,0
Exp/Cntr(USF)=0,0
Exp/Cntr=0.5,0.3

Type RM Length L Ch R = 1 ,184     ,48.7,47.8,48.5
XS GIS Cut Line= 4
2448599.17127681 609021.581654422448521.32837337609212.890484904
2448490.98283475609446.4191952192448467.23415234609591.550032138
#Sta/Elev= 30
       0 1665.79   12.861666.624   49.471668.964    66.2 1672.86    83.5 1684.45
   102.6 1685.29   111.8 1693.94     118 1702.08   126.6 1706.68   139.5 1703.22
   148.2 1684.86   152.6 1679.92     164 1676.11   200.8  1658.5   221.3 1657.01
   228.5 1653.64   236.8 1647.26  247.761644.378   253.5 1642.21   273.1 1639.83
  291.62 1644.38   301.3 1649.81   329.6 1650.39  338.321653.605   373.9 1679.19
   402.2 1694.43   422.3 1702.93   439.91707.489   542.51730.709589.0927 1741.29
#Mann= 9 ,-1 , 0
       0      .1       0   12.86     .06       0   49.47    .055       0
   126.6     .06       0  247.76    .045       0  291.62      .1       0
  338.32     .06       0   439.9      .1       0   542.5      .1       0
Bank Sta=247.76,291.62
XS Rating Curve= 0 ,0
Exp/Cntr(USF)=0,0
Exp/Cntr=0.3,0.1

Type RM Length L Ch R = 1 ,136     ,38.9,38.7,38.2
XS GIS Cut Line= 4
2448560.90951072609032.1366243782448475.15037981609219.487341128
2448436.88861371609434.5448540172448426.33364376609588.911289648
#Sta/Elev= 30
       0 1654.49    7.751656.984    18.8 1658.76    33.9 1658.49    51.4 1662.08
    67.1 1661.33    82.2 1662.29  124.61  1659.4   130.6 1659.01  153.851653.505
   165.8 1651.74   193.8 1651.75   205.4  1649.5   217.6 1645.66   233.9 1645.39
  247.68 1643.27   262.3 1639.24   274.5 1639.63   278.6 1641.02  280.981643.269
   286.7 1648.77   290.8 1649.39  340.39 1648.41   348.1 1648.85   359.8 1653.75
   385.2 1660.59   476.9  1676.7   521.1 1688.28  542.921695.115579.2075 1706.54
#Mann= 8 ,-1 , 0
       0      .1       0    7.75    .055       0  124.61     .06       0
  153.85      .1       0  247.68    .045       0  280.98      .1       0
  340.39     .06       0  542.92      .1       0
Bank Sta=247.68,280.98
XS Rating Curve= 0 ,0
Exp/Cntr(USF)=0,0
Exp/Cntr=0.3,0.1

Type RM Length L Ch R = 1 ,97      ,,,
XS GIS Cut Line= 4
2448535.84145707609058.5240492722448434.24987122609224.764826107
2448399.94621886609446.4191952192448398.62684762609641.686139437
#Sta/Elev= 30
       0 1651.56     9.8 1652.25    24.3 1652.09    33.2 1650.66    76.7 1648.35
   86.951646.882   122.3 1643.77   209.1 1645.03   225.3  1644.2  228.921642.678
   237.5 1639.34   241.5 1638.68   253.6 1638.86   257.7 1639.79  262.881642.678
   265.8  1644.4   269.8 1645.72   290.1 1647.85  329.291646.952   354.8 1645.78
   387.2 1645.92   399.4 1646.82   408.7 1648.51   443.6 1652.64   467.6 1658.48
   503.6 1669.57  530.01 1678.44   539.6 1681.83   579.5 1693.75614.3897 1706.31
#Mann= 6 ,-1 , 0
       0    .055       0   86.95      .1       0  228.92    .045       0
  262.88      .1       0  329.29     .06       0  530.01      .1       0
Bank Sta=228.92,262.88
XS Rating Curve= 0 ,0
Exp/Cntr(USF)=0,0
Exp/Cntr=0.3,0.1
LCMann Table=0

Chan Stop Cuts=-1
Use User Specified Reach Order=0
Composite Channel Slope=5